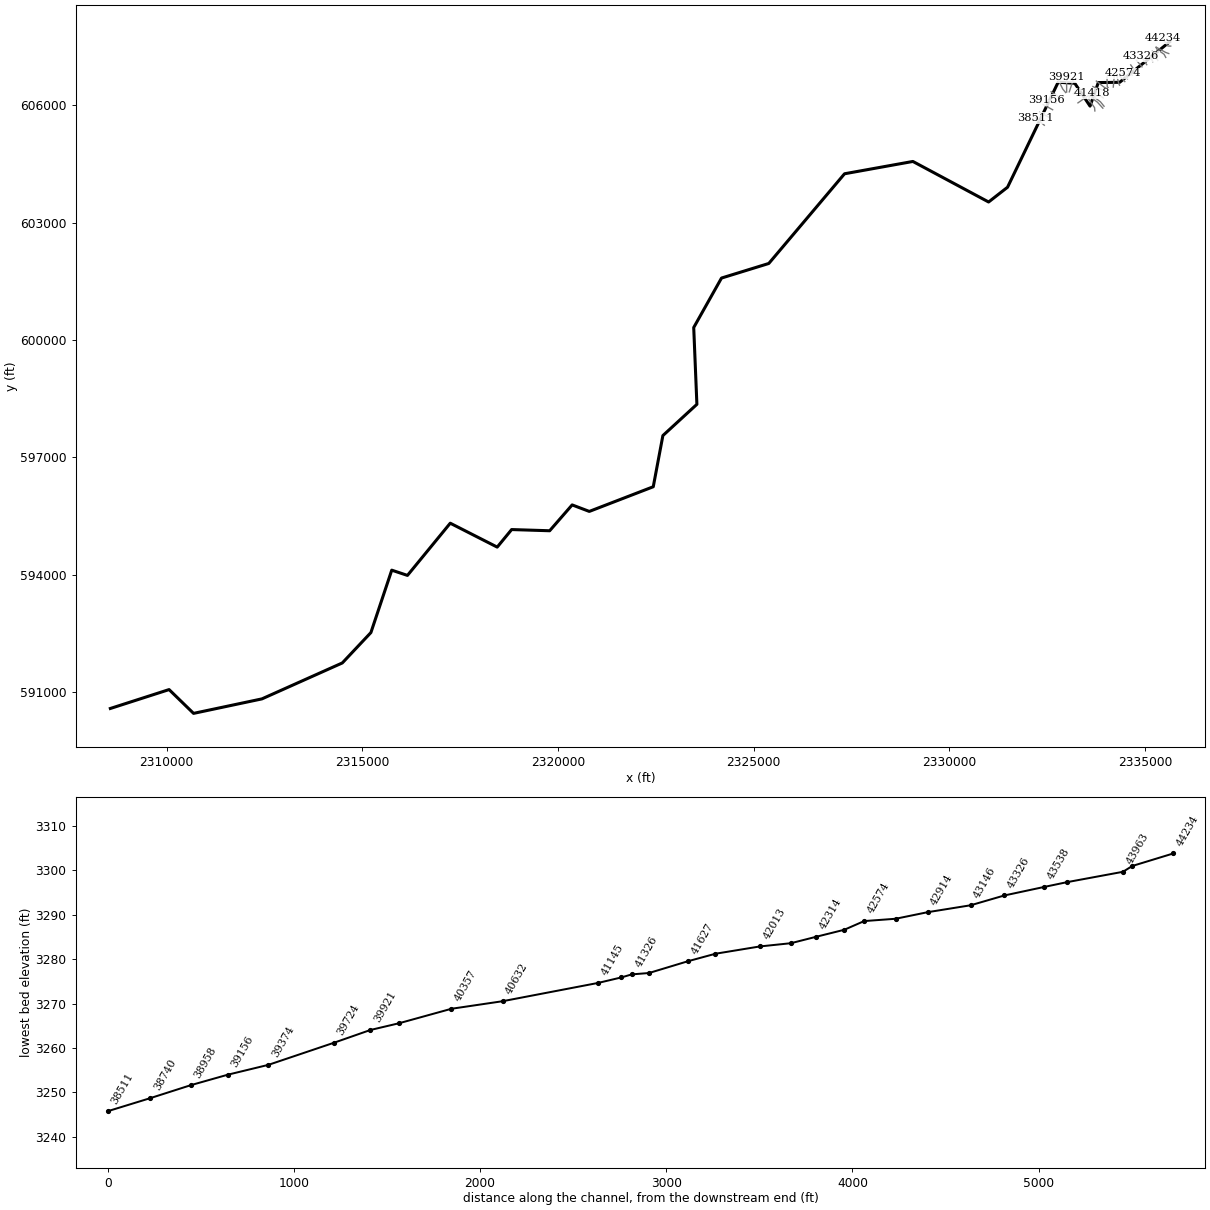
--- LTTLRV1.prj (project) ---

Proj Title=LTTLRV1
Current Plan=p01
Default Exp/Contr=0,0
English Units
Geom File=g01
Flow File=f01
Plan File=p01
BEGIN DESCRIPTION:
----------MODEL BY WOOD PLC 2021----------
Stream Name: Little River I
Flood Zone: Enhanced Approximate
Pocahontas County, WV
HEC-RAS Version: RAS 6.1
Vertical Datum: NAVD88
Projection: NAD 1983 StatePlane West Virginia S FIPS 4702 (US Feet)
Terrain: 1-meter LIDAR (FEMA Region III 3DEP collected 2016-2018)
Land Use: 2019 NLCD
Hydrologic Method:
WV SIR2010-5033 regression equations
Model notes:
Coincident peak with West Fork Greenbrier River
END DESCRIPTION:
DSS Export Rating Curves= 0
DSS Export Rating Curve Sorted= 0
DSS Export Volume Flow Curves= 0
DXF OffsetX= 0
DXF OffsetY= 0
DXF ScaleX= 0
DXF ScaleY= 0

--- LTTLRV1.p01 (plan) ---

Plan Title=Floodplain
Program Version=6.10
Short Identifier=Floodplain
Geom File=g01
Flow File=f01
Subcritical Flow
K Sum by GR= 0
Std Step Tol= 0.01
Critical Tol= 0.01
Num of Std Step Trials= 20
Max Error Tol= 0.3
Flow Tol Ratio= 0.001
Split Flow NTrial= 30
Split Flow Tol= 0.02
Split Flow Ratio= 0.02
Log Output Level= 0
Friction Slope Method= 1
Unsteady Friction Slope Method= 2
Unsteady Bridges Friction Slope Method= 1
Parabolic Critical Depth
Global Vel Dist= 0 , 0 , 0
Global Log Level= 0
CheckData=True
Encroach Param=-1 ,0,0, 0
Mapping Interval=1HOUR
Computation Time Step Use Courant=        0
Computation Time Step Use Time Series=    0
Computation Time Step Count To Double=0
Computation Time Step Max Doubling=0
Computation Time Step Max Halving=0
Computation Time Step Residence Courant=0
Run HTab= 0
Run UNet= 0
Run Sediment= 0
Run PostProcess= 0
Run WQNet= 0
Run RASMapper= 0
UNET Theta= 0
UNET Theta Warmup= 0
UNET ZTol= 0
UNET ZSATol= 0
UNET MxIter= 0
UNET Max Iter WO Improvement= 0
UNET MaxInSteps= 0
UNET DtIC= 0
UNET DtMin= 0
UNET MaxCRTS= 0
UNET WFStab= 0
UNET SFStab= 0
UNET WFX= 1
UNET SFX= 1
UNET Gravity=32.174
UNET 1D Methodology=Finite Difference
UNET DSS MLevel= 1
UNET Pardiso=0
UNET DZMax Abort= 0
UNET Use Existing IB Tables= 0
UNET Froude Reduction=False
UNET Froude Limit= 0
UNET Froude Power= 0
UNET D1 Cores= 0
UNET WindReference=Eulerian
UNET WindDragFormulation=Hsu (1988)
UNET D2 Coriolis=0
UNET D2 Cores= 0
UNET D2 Theta= 1
UNET D2 Theta Warmup= 1
UNET D2 Z Tol= 0.01
UNET D2 Volume Tol= 0.01
UNET D2 Max Iterations= 20
UNET D2 Equation= 0
UNET D2 RampUpFraction=0.1
UNET D2 TimeSlices= 1
UNET D2 Turbulence Formulation=Non-Conservative (original)
UNET D2 Eddy Viscosity=0.3
UNET D2 Transverse Eddy Viscosity=0.1
UNET D2 Smagorinsky Mixing=0
UNET D2 BCVolumeCheck=0
UNET D2 Cores=0
UNET D2 SolverType=PARDISO (Direct)
UNET D2 Minimum Iterations= 2147483647
UNET D2 Maximum Iterations= 2147483647
UNET D2 Restart Number= 10
UNET D2 Relaxation Coeff=1.3
UNET D2 SOR Precondition Iterations= 10
UNET D2 ILUT Maximum Fill= 8
UNET D2 ILUT Tolerance=1E-08
UNET D1D2 MaxIter= 0
UNET D1D2 ZTol=0.01
UNET D1D2 QTol=0.1
UNET D1D2 MinQTol=1
Write IC File= 0
Write IC File at Fixed DateTime=0
Write IC File at Sim End=0
Echo Input=False
Echo Parameters=False
Echo Output=False
Write Detailed= 0
HDF Write Warmup=0
HDF Write Time Slices=0
HDF Flush=0
HDF Compression= 1
HDF Chunk Size= 1
HDF Spatial Parts= 1
HDF Use Max Rows=0
HDF Fixed Rows= 1
Calibration Method= 0
Calibration Iterations= 20
Calibration Max Change=0.05
Calibration Tolerance=0.2
Calibration Maximum=1.5
Calibration Minimum=0.5
Calibration Optimization Method= 1
WQ AD Non Conservative
WQ ULTIMATE=-1
WQ Max Comp Step=1HOUR
WQ Output Interval=15MIN
WQ Output Selected Increments= 0
WQ Output face flow=0
WQ Output face velocity=0
WQ Output face area=0
WQ Output face dispersion=0
WQ Output cell volume=0
WQ Output cell surface area=0
WQ Output cell continuity=0
WQ Output cumulative cell continuity=0
WQ Output face conc=0
WQ Output face dconc_dx=0
WQ Output face courant=0
WQ Output face peclet=0
WQ Output face adv mass=0
WQ Output face disp mass=0
WQ Output cell mass=0
WQ Output cell source sink temp=0
WQ Output nsm pathways=0
WQ Output nsm derived pathways=0
WQ Create Restart=0
WQ Fixed Restart=0
WQ System Summary=0
WQ Write To DSS=0
Sorting and Armoring Iterations= 10
XS Update Threshold= 0.02
Bed Roughness Predictor= 0
Hydraulics Update Threshold= 0.02
Energy Slope Method= 1
Volume Change Method= 1
Sediment Retention Method= 0
Sediment TS Multiplier= 1
Warm Up Method= 0
XS Weighting Method= 0
Number of US Weighted Cross Sections= 1
Number of DS Weighted Cross Sections= 1
Upstream XS Weight=0
Main XS Weight=1
Downstream XS Weight=0
Number of DS XS's Weighted with US Boundary= 1
Upstream Boundary Weight= 1
Weight of XSs Associated with US Boundary= 0
Number of US XS's Weighted with DS Boundary= 1
Downstream Boundary Weight= 0.5
Weight of XSs Associated with DS Boundary= 0.5
Percentile Method= 0
Sediment Output Level= 3
Mass or Volume Output= 0
Output Increment Type= 1
Profile and TS Output Increment= 1
Transport Output Increment 1
XS Output Flag= 0
XS Output Increment= 10
Read HDF5 Sediment Hotstart= 0
Sediment Hotstart Type= 0
Write Gradation File= 0
Read Gradation Hotstart= 0
Write HDF5 File= 1
Write Binary Output= 1
Write DSS Sediment File= 0
DSS Sediment Output Type= 1
SV Curve= 0
Specific Gage Flag= 0
Subcell Erosion Methods= 0
Subcell Deposition Methods= 0
Advection Scheme= 1
Matrix Solver= 0
Implicit Weighting Factor= 1
Maximum Outer Loop Convergence Iterations= 5
Convergence Maximum Absolute= 0.001
Convergence RMSE= 0.0001
Grain Fractions Max Abs Error= 0.001
Max Subgrid Regions= 1
Max Subgrid Length Scale= 3.402823E+38
Initial Layer Thickness= 3.402823E+38
Min Layer Thickness= 3.402823E+38
Max Layer Thickness= 3.402823E+38
Number of Layers= 5

--- LTTLRV1.f01 (steady flow) ---

Flow Title=Flow
Program Version=6.10
Number of Profiles= 6
Profile Names=01pct,10pct,04pct,02pct,0_2pct,01plus
River Rch & RM=LTTLRV1,Main            ,44234
     906     487     642     770    1250    1340
River Rch & RM=LTTLRV1,Main            ,39724
    1130     611     803     959    1550    1670
River Rch & RM=LTTLRV1,Main            ,35262
    1630     895    1170    1390    2230    2410
River Rch & RM=LTTLRV1,Main            ,34557
    1820    1010    1310    1560    2490    2690
River Rch & RM=LTTLRV1,Main            ,30560
    2030    1130    1460    1740    2770    3000
River Rch & RM=LTTLRV1,Main            ,20259
    2650    1480    1920    2270    3590    3910
River Rch & RM=LTTLRV1,Main            ,13310
    3190    1800    2320    2740    4310    4720
Boundary for River Rch & Prof#=LTTLRV1,Main            , 1
Up Type= 0
Dn Type= 1
Dn Known WS=2912.6
Boundary for River Rch & Prof#=LTTLRV1,Main            , 2
Up Type= 0
Dn Type= 1
Dn Known WS=2910.73
Boundary for River Rch & Prof#=LTTLRV1,Main            , 3
Up Type= 0
Dn Type= 1
Dn Known WS=2911.47
Boundary for River Rch & Prof#=LTTLRV1,Main            , 4
Up Type= 0
Dn Type= 1
Dn Known WS=2912.04
Boundary for River Rch & Prof#=LTTLRV1,Main            , 5
Up Type= 0
Dn Type= 1
Dn Known WS=2913.9
Boundary for River Rch & Prof#=LTTLRV1,Main            , 6
Up Type= 0
Dn Type= 1
Dn Known WS=2914.41
DSS Import GetInterval= 0
DSS Import GetPeak= 0
DSS Import FillOption= 0

--- LTTLRV1.g01 (geometry) ---

Geom Title=Geometry
Program Version=6.10

River Reach=LTTLRV1         ,Main
Reach XY= 30
2335623.85097222607617.5899445562334349.42996463 606583.87810123
2333803.63512447606577.9650553172333592.47314522605975.523018733
2333203.28593147606558.6678498092332778.21197847 606586.74390915
2331484.80216372603902.4139759842331000.98193714603524.820899144
2329066.57504481604561.1869366472327320.48503305604246.329954803
2325385.08896947601953.4670864792324177.21408863601580.761138976
2323467.29588905600316.2551378162323548.37085813598352.992003977
2322679.59700514597554.6448473932322433.81796914596246.556912392
2320799.64473635595615.7147706122320361.43489984 595782.22738891
 2319787.2411823 595121.616270962318815.77894539595152.103064567
2318447.11498456594703.5029118962317247.40084855595314.751033232
2316153.94699872593980.2520618142315752.85298464594114.208158731
2315220.20509981592519.2051151392314489.97591722591742.761129975
2312435.95804363590823.8689388932310689.54290131590453.662986398
2310064.37715688591061.8960218882308563.75647047590578.747381896

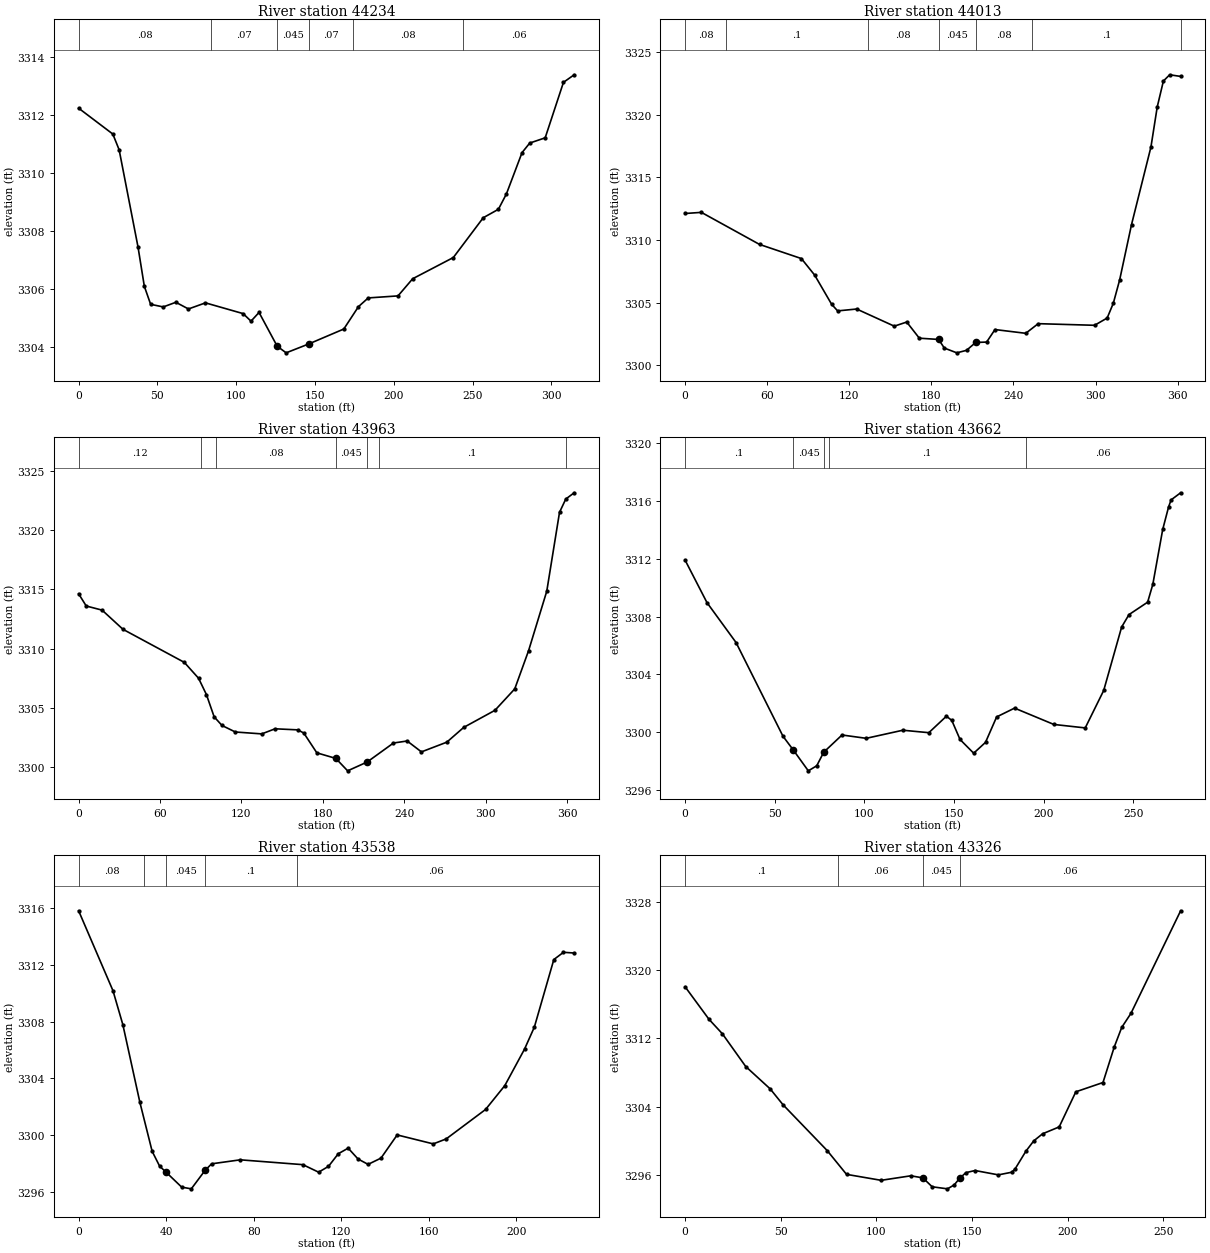
Type RM Length L Ch R = 1 ,44234   ,213,221,230.9
XS GIS Cut Line= 3
2335653.85597627607509.6745024862335580.01542713607512.311664956
2335440.24581625607708.120978313
#Sta/Elev= 30
       0 3312.23    21.7 3311.34    25.7  3310.8    37.7 3307.45    41.7  3306.1
    45.7 3305.48    53.7 3305.39    61.7 3305.55    69.7 3305.32    80.5 3305.53
   104.4 3305.16   109.4  3304.9   114.5  3305.2     126 3304.04   131.7 3303.81
   146.13304.117   168.3 3304.63   177.6  3305.4   183.8  3305.7   202.7 3305.77
     212 3306.36   237.8 3307.09   256.8 3308.46   266.4 3308.75   271.5 3309.28
   281.4  3310.7   286.3 3311.03   296.1 3311.21   307.7 3313.12   314.5 3313.38
#Mann= 6 ,-1,0
       0     .08       0   83.89     .07       0     126    .045       0
   146.1     .07       0  173.89     .08       0  243.89     .06       0
Bank Sta=126,146.1
XS Rating Curve= 0 ,0
Exp/Cntr(USF)=0,0
Exp/Cntr=0.3,0.1

Type RM Length L Ch R = 1 ,44013   ,52.6,50.2,47.8
XS GIS Cut Line= 3
2335603.31180186607319.2275185412335524.56876616607347.861349705
2335281.18120126607483.076663536
#Sta/Elev= 30
       0 3312.11    11.9  3312.2    54.4 3309.64      85 3308.51    94.7 3307.19
   107.1 3304.86   111.5 3304.33   125.4 3304.48   152.9 3303.11     162 3303.44
   171.2 3302.15   185.3 3302.05   189.5 3301.36   198.6 3300.98   205.7 3301.18
   212.4 3301.81   220.4 3301.84   226.5 3302.84     249 3302.54   258.1 3303.31
   299.3 3303.18   308.5 3303.76     313 3304.94   317.6 3306.79   326.3 3311.22
   340.5 3317.42   345.1 3320.62   349.6 3322.69   354.2 3323.19   362.2 3323.06
#Mann= 7 ,-1,0
       0     .08       0      30      .1       0  133.79     .08       0
   185.3    .045       0   212.4     .08       0  253.79      .1       0
  362.21     .06       0
Bank Sta=185.3,212.4
XS Rating Curve= 0 ,0
Exp/Cntr(USF)=0,0
Exp/Cntr=0.3,0.1

Type RM Length L Ch R = 1 ,43963   ,307,301.5,293.1
XS GIS Cut Line= 4
2335526.56855812607220.2338587292335484.02495007607301.066714022
2335305.34179627607425.2940495252335278.11388712607474.644634861
#Sta/Elev= 30
       0 3314.62     5.6 3313.59    17.3 3313.24    32.7 3311.62    77.9 3308.83
    88.4 3307.49    94.2 3306.11    99.9 3304.23   105.7  3303.5   115.5 3302.95
     135 3302.79   144.8 3303.22   161.6 3303.13     166 3302.86   175.6 3301.19
   189.6 3300.72   198.3 3299.67   212.73300.415   232.1 3302.02   242.2 3302.19
   252.7 3301.27   271.4 3302.09   283.9 3303.34   306.9 3304.78   321.5 3306.59
   331.7 3309.82   345.1 3314.84   354.5  3321.5   359.1 3322.62   365.3 3323.15
#Mann= 7 ,-1,0
       0     .12       0      90      .1       0  101.35     .08       0
   189.6    .045       0   212.7     .08       0  221.35      .1       0
  358.97     .06       0
Bank Sta=189.6,212.7
XS Rating Curve= 0 ,0
Exp/Cntr(USF)=0,0
Exp/Cntr=0.3,0.1

Type RM Length L Ch R = 1 ,43662   ,125.6,123.9,122.4
XS GIS Cut Line= 2
2335324.91185597 607142.804492082335179.41271644 607377.64520851
#Sta/Elev= 30
       0 3311.91    12.2 3308.97    28.4 3306.21    54.6 3299.72    60.4 3298.76
    68.7 3297.33    73.4 3297.68    77.3 3298.62    87.5 3299.81     101 3299.58
   121.4 3300.14   135.9 3299.97   145.7 3301.11   148.7 3300.82   153.3  3299.5
   160.9 3298.55   167.5  3299.3   173.7 3301.06   183.7 3301.67   205.6 3300.54
   223.1  3300.3   233.4 3302.89   243.4 3307.28   247.5 3308.14   257.9    3309
   260.8 3310.24   266.3 3314.03   269.6  3315.6     271 3316.08   276.3 3316.57
#Mann= 5 ,-1,0
       0      .1       0    60.4    .045       0    77.3     .08       0
      80      .1       0     190     .06       0
Bank Sta=60.4,77.3
XS Rating Curve= 0 ,0
Exp/Cntr(USF)=0,0
Exp/Cntr=0.3,0.1

Type RM Length L Ch R = 1 ,43538   ,209.7,211.9,213.6
XS GIS Cut Line= 2
2335195.76665965607111.1470582392335093.97338986607313.445075414
#Sta/Elev= 30
       0 3315.79    15.7 3310.17    20.2 3307.79      28 3302.32    33.6 3298.88
      37 3297.84    39.9 3297.42    47.1 3296.36    51.5 3296.24    57.8 3297.54
    60.8    3298    73.9 3298.28   102.5 3297.94   109.7 3297.41   114.2 3297.82
   118.7 3298.71   123.2  3299.1   127.7 3298.34   132.3 3297.96   138.2  3298.4
   145.6 3300.03   162.1  3299.4     168 3299.75     186 3301.82   194.8  3303.5
   203.8 3306.06   208.3 3307.61   217.2 3312.36   221.6 3312.87   226.5 3312.82
#Mann= 5 ,-1,0
       0     .08       0      30      .1       0    39.9    .045       0
    57.8      .1       0     100     .06       0
Bank Sta=39.9,57.8
XS Rating Curve= 0 ,0
Exp/Cntr(USF)=0,0
Exp/Cntr=0.3,0.1

Type RM Length L Ch R = 1 ,43326   ,171.2,180.4,180.4
XS GIS Cut Line= 2
 2335040.7205542607034.7437276362334897.77403116607250.865256525
#Sta/Elev= 30
       0 3318.06    12.5 3314.24    19.5 3312.54    31.7  3308.7    44.5 3306.07
    51.2 3304.21    74.3 3298.83    84.4 3296.04   102.5 3295.34     118 3295.87
   124.3 3295.63   129.2 3294.58   137.2 3294.34   140.7  3294.8  143.54 3295.57
   146.8 3296.24   151.6 3296.49   163.8 3295.98   170.8 3296.29   172.5 3296.66
   178.2 3298.76   182.3 3299.97   186.9  3300.8   195.6 3301.61   204.3 3305.73
   218.5 3306.82   224.4    3311   228.3 3313.29   233.1 3314.93   259.1 3326.98
#Mann= 4 ,-1,0
       0      .1       0      80     .06       0   124.3    .045       0
  143.54     .06       0
Bank Sta=124.3,143.54
XS Rating Curve= 0 ,0
Exp/Cntr(USF)=0,0
Exp/Cntr=0.3,0.1

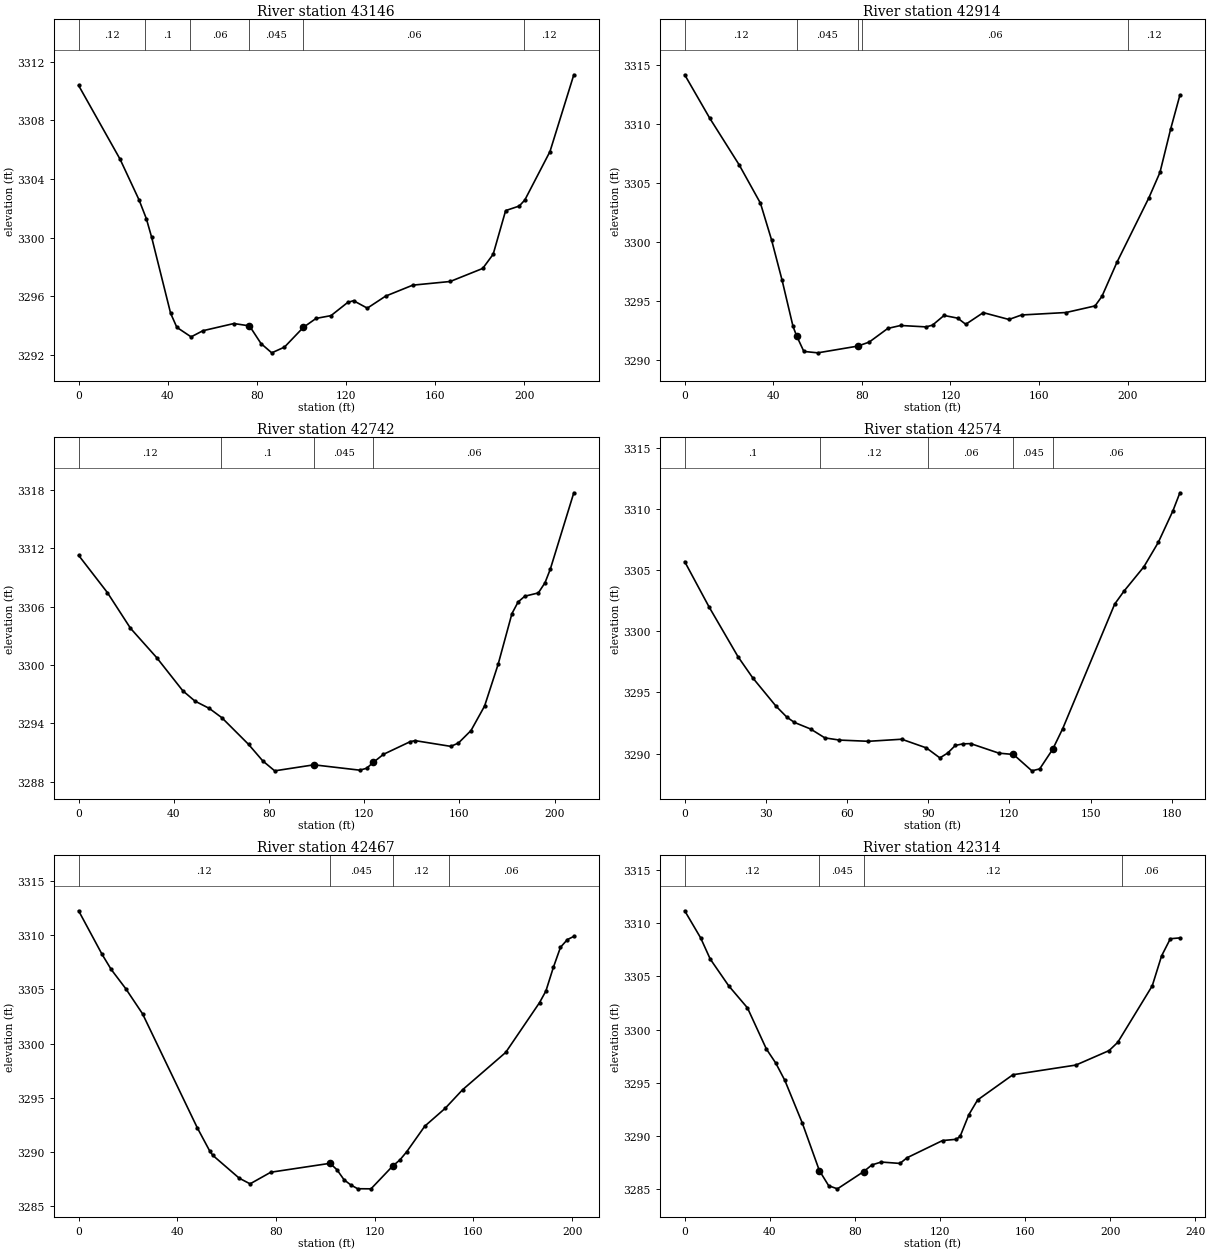
Type RM Length L Ch R = 1 ,43146   ,227.4,231.2,228.2
XS GIS Cut Line= 2
2334919.75729854606978.5598970662334776.39175156607148.438250681
#Sta/Elev= 30
       0 3310.39    18.6 3305.36    27.1 3302.59    30.4  3301.3    32.8 3300.02
    41.3 3294.84    44.1 3293.88    50.5 3293.23    55.8 3293.65    69.7 3294.14
    76.7 3293.98    81.9 3292.77    86.7 3292.14    92.4 3292.53   100.9 3293.88
   106.6 3294.49   113.3 3294.68   120.8 3295.58   123.4  3295.7   129.6 3295.19
   137.8 3296.01     150 3296.76   166.8 3297.01   181.4  3297.9   186.1 3298.87
   191.7 3301.85   197.8 3302.16   200.3 3302.57   211.6 3305.88   222.3 3311.12
#Mann= 6 ,-1,0
       0     .12       0      30      .1       0      50     .06       0
    76.7    .045       0   100.9     .06       0     200     .12       0
Bank Sta=76.7,100.9
XS Rating Curve= 0 ,0
Exp/Cntr(USF)=0,0
Exp/Cntr=0.3,0.1

Type RM Length L Ch R = 1 ,42914   ,152.1,172,171.6
XS GIS Cut Line= 2
2334759.69850294606845.0139080972334632.04424877 607028.63964293
#Sta/Elev= 30
       0 3314.16    11.3 3310.48    24.6 3306.52    34.2 3303.27    39.2 3300.17
      44 3296.72    48.9 3292.83    50.5 3292.03    53.8  3290.7    60.1 3290.58
    78.1 3291.15    83.3 3291.49    91.7 3292.65    97.5  3292.9     109 3292.78
   111.9 3292.93   117.1 3293.75   123.3 3293.52   126.9    3293   134.8 3293.99
   146.4 3293.41   152.1 3293.79   172.2    3294   185.3 3294.56   188.4 3295.37
   195.2 3298.27   209.6 3303.73   214.6 3305.88   219.4 3309.54   223.6 3312.43
#Mann= 5 ,-1,0
       0     .12       0    50.5    .045       0    78.1     .12       0
      80     .06       0     200     .12       0
Bank Sta=50.5,78.1
XS Rating Curve= 0 ,0
Exp/Cntr(USF)=0,0
Exp/Cntr=0.3,0.1

Type RM Length L Ch R = 1 ,42742   ,169.8,168.8,168.4
XS GIS Cut Line= 2
2334669.44144006  606765.36475732334526.27228424606916.408216691
#Sta/Elev= 30
       0 3311.29    12.1 3307.45    21.8 3303.78    32.8 3300.76    43.8 3297.34
    48.9 3296.28    54.9 3295.53    60.2 3294.57    71.4 3291.83    77.4 3290.12
    82.4  3289.1    98.9 3289.72   118.1 3289.17     121 3289.36   123.9 3289.98
   128.1  3290.8   139.4 3292.11   141.4 3292.21   156.4 3291.62   159.6 3291.96
   164.9 3293.25   170.6 3295.77   176.3 3300.07   182.1 3305.29   184.7 3306.49
   187.5 3307.08   193.2 3307.42     196 3308.47   198.2 3309.85   208.1 3317.73
#Mann= 4 ,-1,0
       0     .12       0      60      .1       0    98.9    .045       0
   123.9     .06       0
Bank Sta=98.9,123.9
XS Rating Curve= 0 ,0
Exp/Cntr(USF)=0,0
Exp/Cntr=0.3,0.1

Type RM Length L Ch R = 1 ,42574   ,108.6,107.1,105.7
XS GIS Cut Line= 2
2334550.61104073606674.4523433542334428.91725828606811.178887163
#Sta/Elev= 30
       0 3305.72       9 3302.01    19.7 3297.93    25.1 3296.21    33.7 3293.89
    37.7 3292.99    40.5 3292.55    46.5 3292.01    51.8 3291.28    57.2  3291.1
    67.9    3291    80.2 3291.17    89.3 3290.46    94.3 3289.64    97.2 3290.04
     100 3290.66   102.8 3290.79   105.7 3290.81   116.1 3290.03   121.5 3289.92
   128.3 3288.58   131.2 3288.74     136 3290.35   139.7 3292.04   158.9 3302.24
   162.3 3303.29   169.7  3305.3     175 3307.29   180.4 3309.87     183 3311.36
#Mann= 5 ,-1,0
       0      .1       0      50     .12       0      90     .06       0
   121.5    .045       0     136     .06       0
Bank Sta=121.5,136
XS Rating Curve= 0 ,0
Exp/Cntr(USF)=0,0
Exp/Cntr=0.3,0.1

Type RM Length L Ch R = 1 ,42467   ,159.3,152.3,139.6
XS GIS Cut Line= 2
2334481.13417639606602.2001446042334344.75142622606749.493514791
#Sta/Elev= 30
       0 3312.22     9.5 3308.21    13.2 3306.82    19.1 3305.05    25.9 3302.74
    48.1 3292.24    53.1 3290.12    54.4  3289.7    65.1  3287.6    69.5 3287.08
    77.9 3288.15   101.9 3288.97   104.7 3288.38   107.6 3287.45   110.3 3286.98
   113.1 3286.63   118.5 3286.62   127.3 3288.72   130.2 3289.28     133 3290.04
   140.3 3292.39   148.6 3294.04   155.6 3295.74   173.1 3299.18   186.8 3303.76
   189.4 3304.84   192.4    3307   195.3 3308.86   198.1 3309.57   200.7 3309.86
#Mann= 4 ,-1,0
       0     .12       0   101.9    .045       0   127.3     .12       0
     150     .06       0
Bank Sta=101.9,127.3
XS Rating Curve= 0 ,0
Exp/Cntr(USF)=0,0
Exp/Cntr=0.3,0.1

Type RM Length L Ch R = 1 ,42314   ,140.4,134,128
XS GIS Cut Line= 3
2334345.26175202 606510.400046352334325.98221393606551.798535451
2334281.36436036606733.562314985
#Sta/Elev= 30
       0 3311.18     7.5 3308.63      12 3306.64    20.7 3304.12    29.5 3302.05
    38.4 3298.18    42.8 3296.86    47.1 3295.22    55.3 3291.21    63.3 3286.75
    67.7 3285.32    71.8 3285.03    84.2 3286.66      88 3287.28    92.4 3287.55
   101.2 3287.42   104.5 3287.95   121.2 3289.57   127.7 3289.69   129.5 3289.97
   133.6 3292.01   137.7 3293.39   154.3 3295.76   183.9 3296.67   199.5 3298.03
   203.6 3298.81   219.8 3304.12   224.2 3306.94   228.3 3308.55   232.8 3308.63
#Mann= 4 ,-1,0
       0     .12       0    63.3    .045       0    84.2     .12       0
  205.67     .06       0
Bank Sta=63.3,84.2
XS Rating Curve= 0 ,0
Exp/Cntr=0.3,0.1

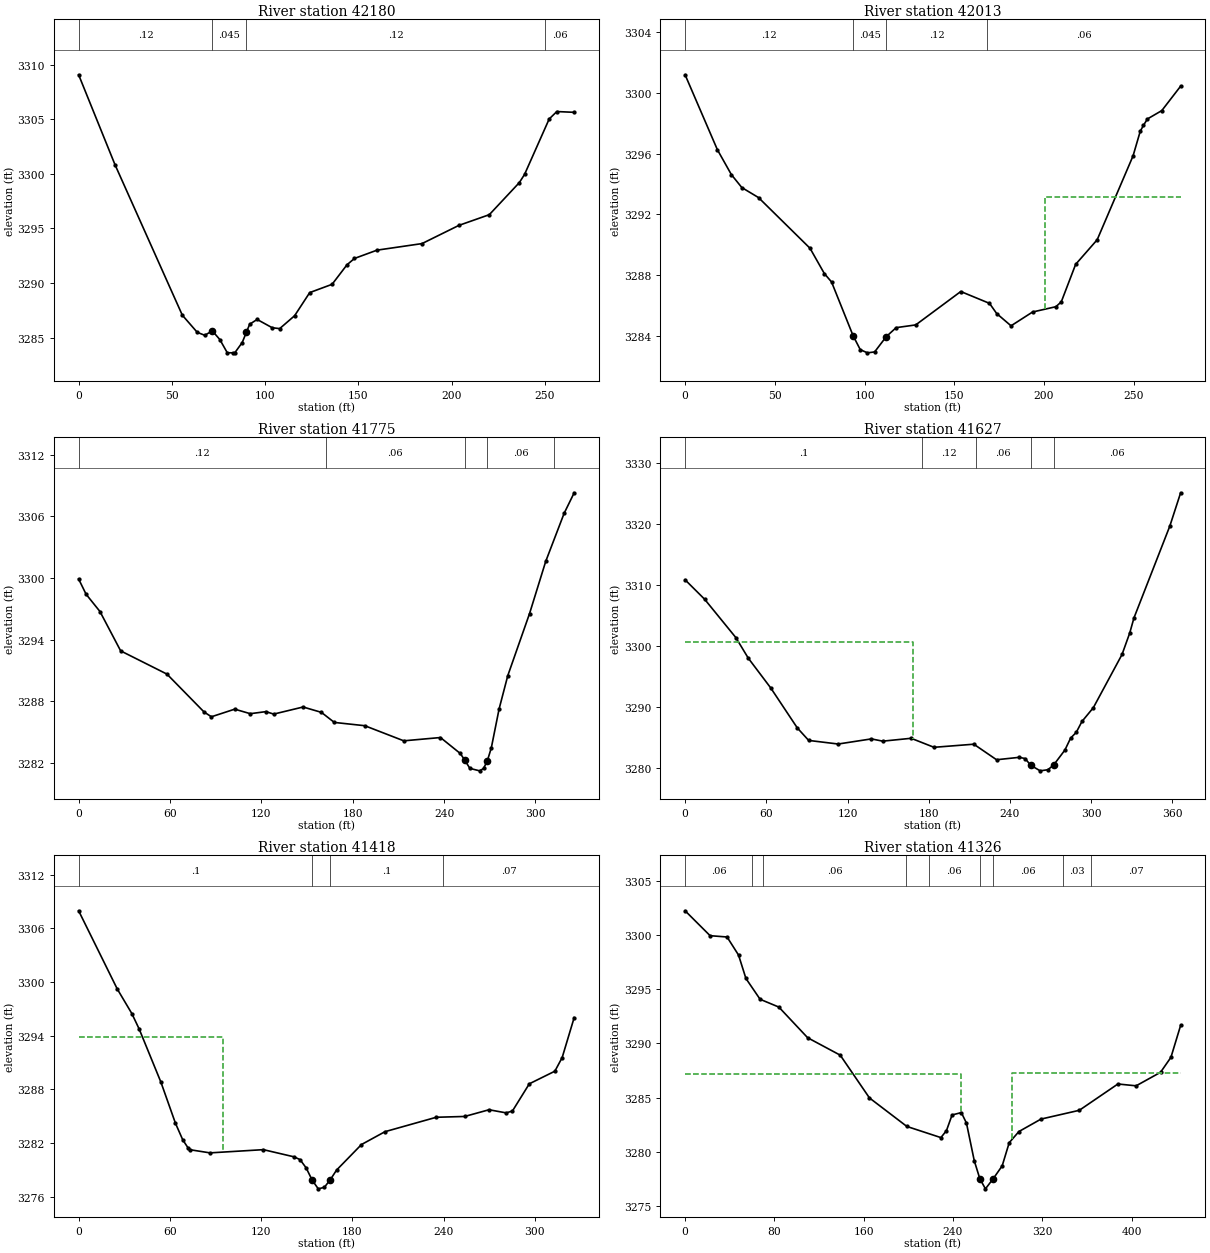
Type RM Length L Ch R = 1 ,42180   ,164.2,166.9,168.7
XS GIS Cut Line= 2
 2334186.0457548606461.8015879872334209.27981101606726.467447727
#Sta/Elev= 30
       0 3309.08    19.5 3300.84    55.6 3287.05    63.6 3285.48    67.6 3285.21
    71.7 3285.61    75.7 3284.82    79.7 3283.61    82.6  3283.6    83.7  3283.6
    87.7 3284.54    89.93285.464    91.7 3286.22    95.7 3286.66   103.8  3285.9
   107.8 3285.82   115.8    3287   123.9 3289.12   135.9 3289.88   143.9 3291.67
   147.9 3292.25     160 3293.01   184.1 3293.61   203.9 3295.28   220.2 3296.26
   236.3  3299.2   239.1 3299.95   252.3 3305.03   256.4 3305.71   265.7 3305.64
#Mann= 4 ,-1,0
       0     .12       0    71.7    .045       0    89.9     .12       0
     250     .06       0
Bank Sta=71.7,89.9
XS Rating Curve= 0 ,0
Exp/Cntr(USF)=0,0
Exp/Cntr=0.3,0.1

Type RM Length L Ch R = 1 ,42013   ,212.4,238.2,251.6
XS GIS Cut Line= 3
2334053.14598112606446.2509431362334031.60379548 606477.95849235
2334025.41747393 606715.68999183
#Sta/Elev= 30
       0 3301.19      18 3296.25    25.8 3294.61    31.6 3293.76    40.9  3293.1
    69.6 3289.76    77.6 3288.09    81.6 3287.54    93.6    3284    97.6 3283.08
   101.6 3282.87   105.6 3282.93   112.1 3283.94   117.6 3284.53   128.5 3284.71
   153.6 3286.91   169.6 3286.13   173.6 3285.46   181.6 3284.65   193.6 3285.56
   206.6 3285.91   209.6 3286.23   217.6  3288.7   229.6 3290.32   249.6 3295.85
   253.6 3297.47   255.4 3297.86   257.6 3298.28   265.6 3298.83   276.1 3300.44
#Mann= 4 ,-1,0
       0     .12       0    93.6    .045       0   112.1     .12       0
  168.33     .06       0
#XS Ineff= 2 , 0
                          200.58         3293.17
Permanent Ineff=
       F       F
Bank Sta=93.6,112.1
XS Rating Curve= 0 ,0
Exp/Cntr(USF)=0,0
Exp/Cntr=0.3,0.1

Type RM Length L Ch R = 1 ,41775   ,144.6,148.2,153.2
XS GIS Cut Line= 3
2334016.45588667606425.6335407812333943.94679737606464.791974223
2333753.56717054606615.733015624
#Sta/Elev= 30
       0 3299.89     4.9 3298.41      14 3296.73    27.6  3292.9      58 3290.64
    82.4 3286.95    87.2 3286.49   102.5 3287.23   112.7 3286.79     123 3286.99
   128.1 3286.75   147.4 3287.44   159.4 3286.92   167.9 3285.94   187.9 3285.62
   213.5 3284.15   237.6 3284.47   250.6 3282.92   253.4 3282.31   256.9 3281.47
   263.3 3281.23   265.9 3281.46  268.43 3282.23     271 3283.47   276.1 3287.25
   281.8 3290.49   296.1 3296.53   306.7  3301.6   318.8 3306.28   325.4 3308.28
#Mann= 5 ,-1,0
       0     .12       0  162.41     .06       0   253.4    .045       0
  268.43     .06       0  312.41     .12       0
Bank Sta=253.4,268.43
XS Rating Curve= 0 ,0
Exp/Cntr(USF)=0,0
Exp/Cntr=0.3,0.1

Type RM Length L Ch R = 1 ,41627   ,201.1,209,215.6
XS GIS Cut Line= 4
 2334004.5956886 606343.106123782333939.95762348606380.627906719
2333706.94502698606456.4088492362333664.96466272606475.913199603
#Sta/Elev= 30
       0 3310.88    14.4  3307.7    37.5  3301.4    46.7 3298.02    63.3 3293.13
    82.9 3286.58    91.3 3284.53   113.1 3283.94   137.6 3284.78     146 3284.41
     167 3284.88   183.9  3283.4   213.3 3283.91   230.1 3281.36     247 3281.76
   251.2 3281.55   255.4 3280.45   262.3 3279.54     268 3279.72   272.2 3280.48
   280.6 3282.95   284.8  3284.9     289 3285.86   293.2 3287.64   301.6  3289.9
   322.8 3298.63   328.5 3302.16   331.6 3304.62   358.1 3319.69   366.1 3325.16
#Mann= 5 ,-1,0
       0      .1       0  174.74     .12       0  214.74     .06       0
   255.4    .045       0   272.2     .06       0
#XS Ineff= 2 , 0
          168.12 3300.63
Permanent Ineff=
       F       F
Bank Sta=255.4,272.2
XS Rating Curve= 0 ,0
Exp/Cntr=0.3,0.1

Type RM Length L Ch R = 1 ,41418   ,105.7,92.5,77
XS GIS Cut Line= 4
2333929.43939045606185.8175998492333846.31351909606240.315253888
2333716.24275138606236.2025376342333647.02092884606303.242236163
#Sta/Elev= 30
       0 3307.97    25.4 3299.23      35 3296.48    39.8 3294.76    54.1 3288.82
    63.7 3284.21    68.5 3282.36    71.8 3281.51    73.3 3281.26    86.4 3280.91
   121.5 3281.27   141.6 3280.47   145.6 3280.16   149.6 3279.24   153.6 3277.86
   157.6 3276.89   161.6 3277.06   165.6 3277.93   169.6 3278.98     186 3281.84
   201.5 3283.28   235.2 3284.89   253.9 3284.98   269.9 3285.73   281.2 3285.38
   285.3 3285.59   296.4 3288.63   313.2 3290.04     318 3291.56   325.9 3296.03
#Mann= 4 ,-1,0
       0      .1       0   153.6    .045       0   165.6      .1       0
  239.53     .07       0
#XS Ineff= 2 , 0
           95.02 3293.88
Permanent Ineff=
       F       F
Bank Sta=153.6,165.6
XS Rating Curve= 0 ,0
Exp/Cntr(USF)=0,0
Exp/Cntr=0.5,0.3

Type RM Length L Ch R = 1 ,41326   ,55.3,55.6,56.1
XS GIS Cut Line= 4
2333950.61475591605972.061225294 2333856.9836976606087.005715857
2333700.73089993606203.8027711682333626.95517565606272.276330313
#Sta/Elev= 30
       0 3302.25    22.4 3299.95    37.6 3299.83    47.9 3298.16    54.5    3296
    67.2 3294.08      84 3293.36   109.8 3290.53     139 3288.92   165.2 3284.97
   198.7 3282.34   229.2 3281.31   234.2 3281.96   239.2  3283.4   247.5 3283.62
   252.1 3282.65   259.1 3279.17   264.1 3277.51   269.1 3276.58   276.1 3277.52
   284.1  3278.7   290.4 3280.84   299.1 3281.87   318.9 3283.02   353.2 3283.83
   387.8 3286.26   404.1 3286.09     426 3287.34   435.3 3288.72     444 3291.67
#Mann= 9 ,-1,0
       0     .06       0      60      .1       0      70     .06       0
  198.25      .1       0  218.25     .06       0   264.1    .045       0
   276.1     .06       0  338.25     .03       0  363.33     .07       0
#XS Ineff= 2 , 0
          246.86  3287.2  293.24          3287.3
Permanent Ineff=
       F       F
Bank Sta=264.1,276.1
XS Rating Curve= 0 ,0
Exp/Cntr=0.5,0.3

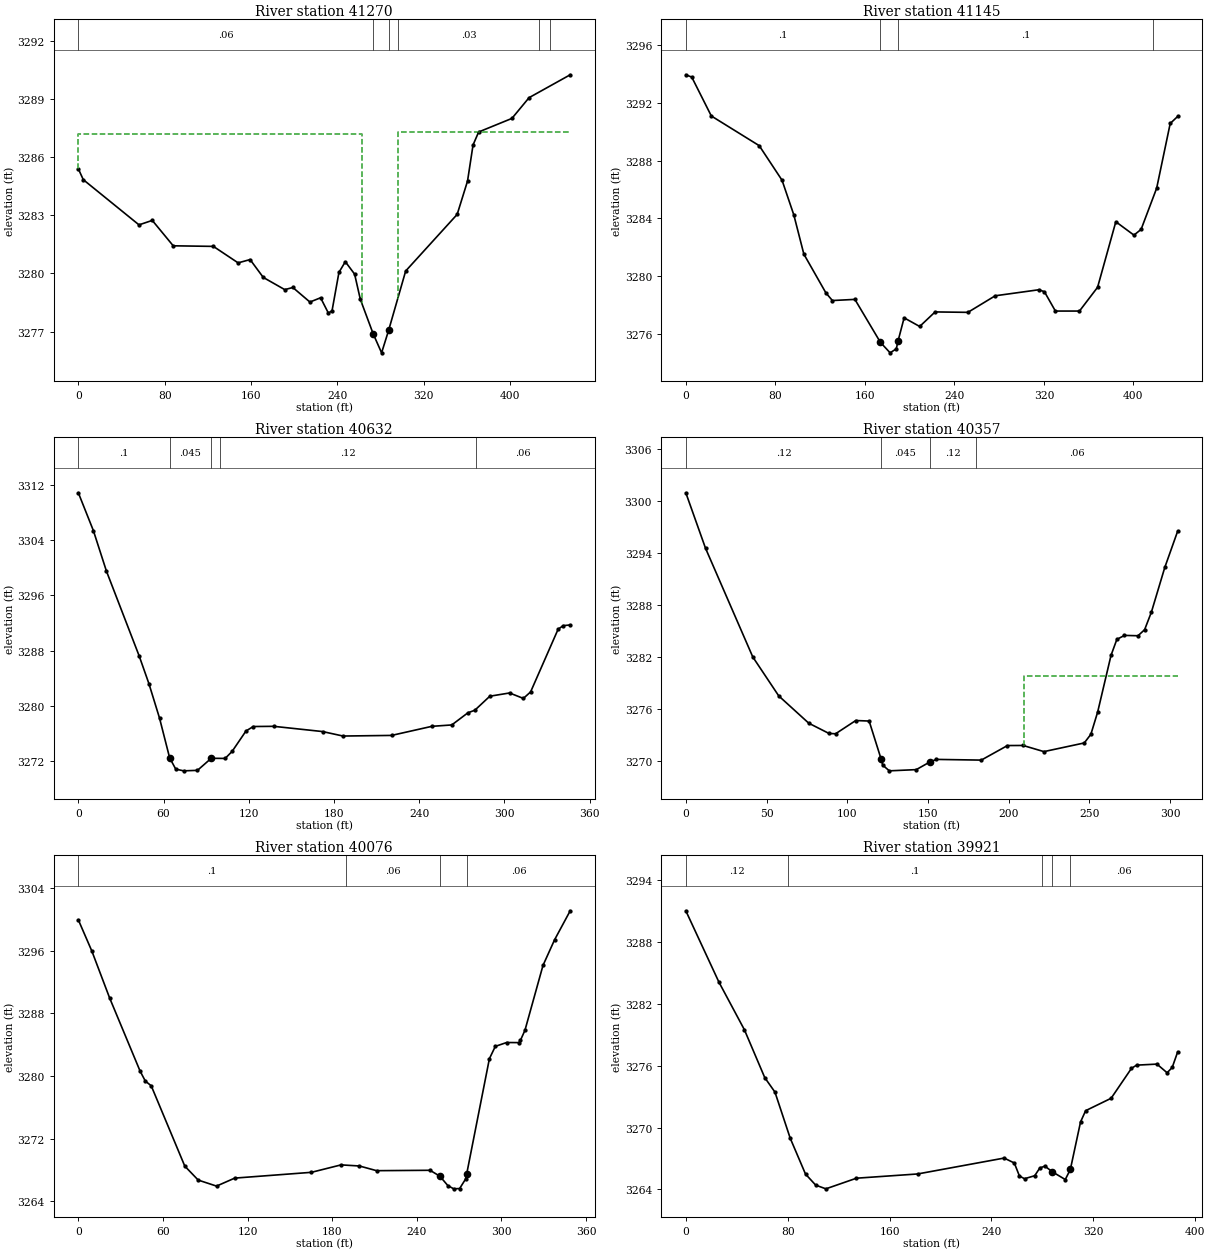
Type RM Length L Ch R = 1 ,41270   ,134.8,125,117.6
XS GIS Cut Line= 4
 2333919.2340515605923.5323541672333780.53909849606076.434752873
2333666.58373391606158.8705485332333597.48314048606242.518635306
#Sta/Elev= 30
       0 3285.39     4.6 3284.83    56.2  3282.5    68.5 3282.73    87.9 3281.42
   125.1 3281.39     148 3280.54   159.1 3280.71   171.3 3279.79   191.2 3279.16
   198.7 3279.27   214.5 3278.52   224.4 3278.74   231.6 3277.95     235 3278.07
   241.4 3280.05   247.3  3280.6   255.9 3279.96   261.2 3278.66   273.1 3276.88
   280.9  3275.9   287.4 3277.06   303.2 3280.12   350.9 3283.04   360.5 3284.76
   365.6 3286.62   370.8 3287.29   401.6 3287.99   417.5 3289.06   455.6 3290.24
#Mann= 6 ,-1,0
       0     .06       0   273.1    .045       0   287.4     .06       0
  296.44     .03       0  427.08     .07       0  437.08     .06       0
#XS Ineff= 2 , 0
           262.8  3287.2  295.65          3287.3
Permanent Ineff=
       F       F
Bank Sta=273.1,287.4
XS Rating Curve= 0 ,0
Exp/Cntr(USF)=0,0
Exp/Cntr=0.5,0.3

Type RM Length L Ch R = 1 ,41145   ,536.1,513.4,461.8
XS GIS Cut Line= 4
2333715.65727814605851.8820700792333707.80163173605935.808983807
2333562.32669822606143.1107640692333579.29877379606243.730926418
#Sta/Elev= 30
       0 3293.96     5.3  3293.8    22.8  3291.1    65.6 3289.04      86 3286.64
    96.5 3284.24   105.5 3281.51   125.2 3278.82     131 3278.29   151.1 3278.37
   173.9 3275.39   182.6 3274.66   188.1 3274.94   189.7 3275.49   195.1 3277.09
     209 3276.49   222.8  3277.5   252.1 3277.47   276.5 3278.62   315.6 3279.04
   320.5  3278.9   330.3 3277.56   351.8 3277.56     368 3279.21   384.3 3283.76
   400.5 3282.83   406.9 3283.23   420.8 3286.09   432.9 3290.58   439.6 3291.07
#Mann= 4 ,-1,0
       0      .1       0   173.9    .045       0   189.7      .1       0
  417.55     .06       0
Bank Sta=173.9,189.7
XS Rating Curve= 0 ,0
Exp/Cntr(USF)=0,0
Exp/Cntr=0.3,0.1

Type RM Length L Ch R = 1 ,40632   ,281.2,274.6,264.6
XS GIS Cut Line= 2
2333283.49974231606058.2503861842333567.17586267606257.066128657
#Sta/Elev= 30
       0 3310.89    10.6  3305.4    19.8 3299.52    42.8 3287.24    49.7  3283.2
    57.2 3278.18    64.3 3272.43    68.6 3270.79    74.1 3270.54    83.9 3270.61
    93.6 3272.36   103.4 3272.34   108.3 3273.36   118.1 3276.33   123.2 3276.97
   137.6    3277     172 3276.24   186.4 3275.59   220.6 3275.68     249    3277
     263  3277.2   274.4 3278.97   279.2 3279.33   289.8 3281.37   303.7 3281.84
   313.4 3281.05   318.5 3281.99   337.9  3291.1   341.5 3291.61   346.4 3291.71
#Mann= 5 ,-1,0
       0      .1       0    64.3    .045       0    93.6      .1       0
     100     .12       0     280     .06       0
Bank Sta=64.3,93.6
XS Rating Curve= 0 ,0
Exp/Cntr(USF)=0,0
Exp/Cntr=0.3,0.1

Type RM Length L Ch R = 1 ,40357   ,260.5,280.7,301
XS GIS Cut Line= 3
2333175.68821542 606291.471430562333218.22324338606347.026920571
2333443.86504688606412.168202239
#Sta/Elev= 30
       0 3300.95    12.2 3294.55    41.5 3281.99    57.6 3277.49    76.2 3274.34
    88.7 3273.16    92.8 3273.12   105.3 3274.65   113.6 3274.59     121 3270.21
     122  3269.5   126.1 3268.84   142.8 3268.98   151.1 3269.85   155.3 3270.16
   183.1 3270.08   199.3 3271.76     209 3271.77   221.9 3271.06   246.9 3272.06
     251 3273.06   255.2 3275.63   263.5 3282.19   267.1 3284.02   271.8 3284.48
   280.2 3284.44   284.3 3285.14   288.5 3287.17   296.8 3292.33   304.8 3296.53
#Mann= 4 ,-1,0
       0     .12       0     121    .045       0   151.1     .12       0
  179.97     .06       0
#XS Ineff= 2 , 0
                          209.32         3279.84
Permanent Ineff=
       F       F
Bank Sta=121,151.1
XS Rating Curve= 0 ,0
Exp/Cntr=0.3,0.1

Type RM Length L Ch R = 1 ,40076   ,150.2,154.9,161.5
XS GIS Cut Line= 2
2333062.13252022606340.0388652032333170.14765836606671.721713622
#Sta/Elev= 30
       0 3299.95     9.6 3295.96    22.2 3289.97    43.8 3280.63    47.5 3279.36
    51.7 3278.75    75.5 3268.49      85 3266.71      98 3265.94   110.9 3266.96
   165.3  3267.7   186.3 3268.65   199.3 3268.51   211.5 3267.91   249.4 3267.96
   256.4  3267.2     262 3266.01   266.2 3265.59   270.4 3265.63   274.6 3266.84
   275.4  3267.5   291.5 3282.22   295.7 3283.79   303.7 3284.28   312.5 3284.27
   313.5 3284.56   316.7 3285.84   329.5 3294.13   337.7  3297.4   348.8 3301.11
#Mann= 4 ,-1,0
       0      .1       0     190     .06       0   256.4    .045       0
   275.4     .06       0
Bank Sta=256.4,275.4
XS Rating Curve= 0 ,0
Exp/Cntr(USF)=0,0
Exp/Cntr=0.3,0.1

Type RM Length L Ch R = 1 ,39921   ,186.3,197.6,208.6
XS GIS Cut Line= 2
2332994.66129982606335.1680752182332993.49412264606721.503720325
#Sta/Elev= 30
       0 3290.99      26 3284.08      46 3279.47      62 3274.83      70 3273.43
      82 3268.96      94 3265.49     102 3264.42     110 3264.06     134 3265.09
     182  3265.5     250 3267.04     258 3266.56     262  3265.3     266 3265.04
     274 3265.33     278 3266.08     282 3266.26   287.6 3265.73     298 3264.96
     302 3265.94     310 3270.54     314 3271.63     334 3272.83     350 3275.73
     354 3276.04     370 3276.14     378  3275.3     382 3275.82   386.3 3277.33
#Mann= 5 ,-1,0
       0     .12       0      80      .1       0     280     .06       0
   287.6    .045       0     302     .06       0
Bank Sta=287.6,302
XS Rating Curve= 0 ,0
Exp/Cntr(USF)=0,0
Exp/Cntr=0.3,0.1

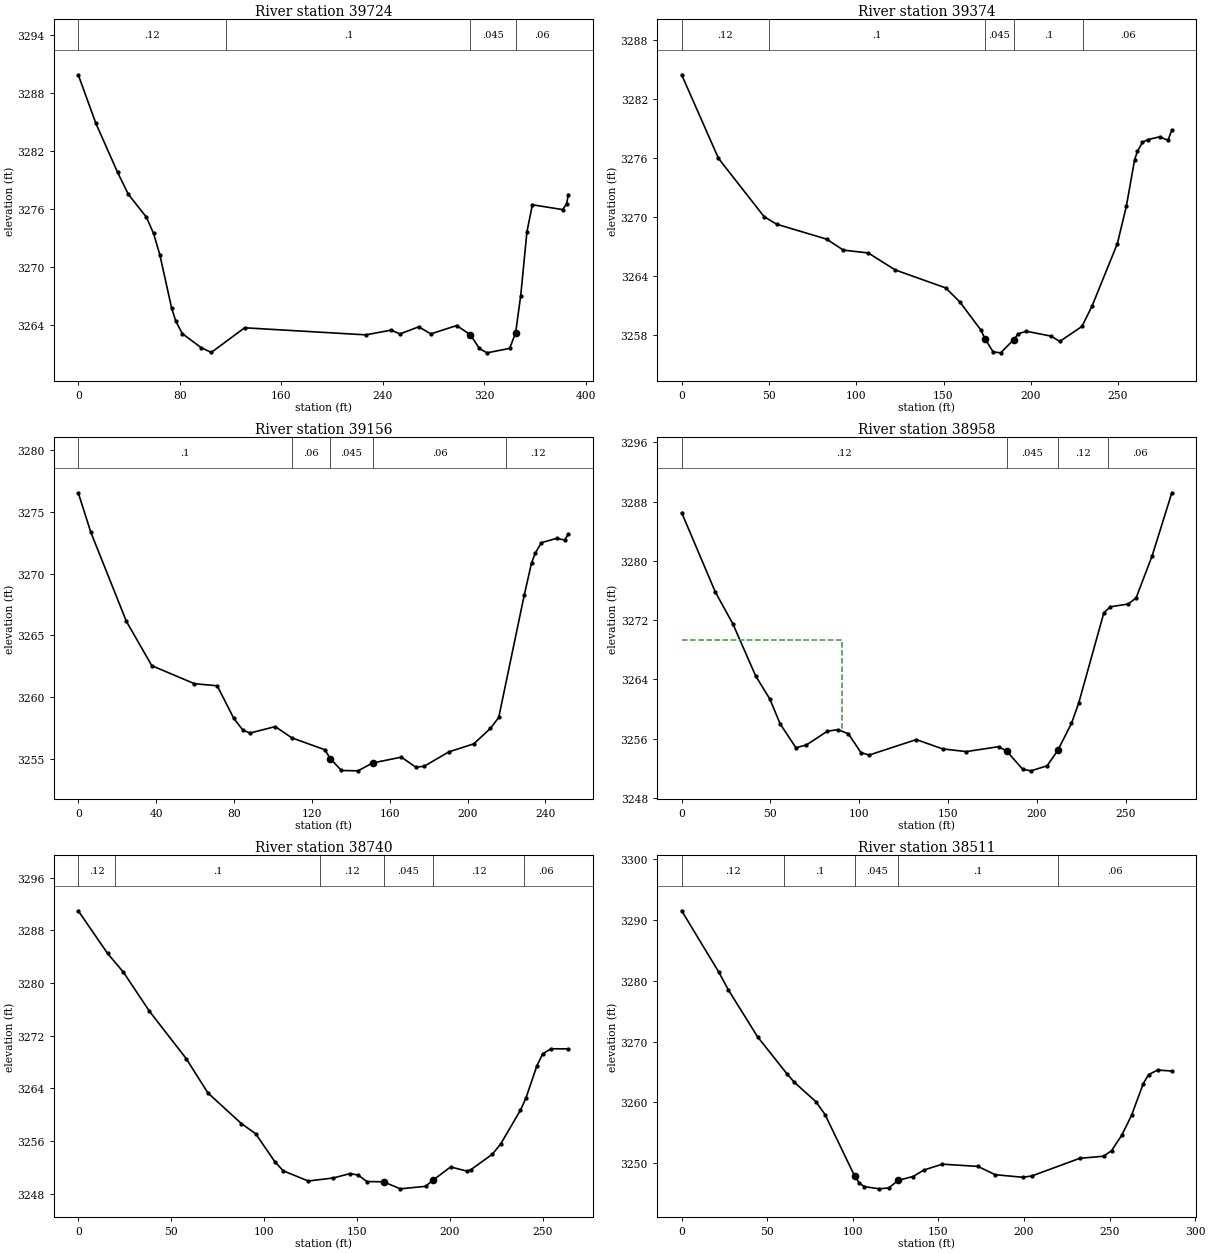
Type RM Length L Ch R = 1 ,39724   ,330.1,349.5,364.7
XS GIS Cut Line= 3
2332968.97506998606322.366124692     2332894.906606412.580723727
2332775.51085389606654.501725549
#Sta/Elev= 30
       0 3289.91    13.9 3284.89      31 3279.83    39.5 3277.55    53.7  3275.2
    59.4  3273.5    64.3 3271.32    73.6 3265.81    76.9 3264.44    82.1 3263.14
    96.8 3261.71   104.9  3261.2   131.2 3263.75   226.7 3263.02   246.8 3263.51
   253.6 3263.11   268.5 3263.85     278 3263.12   298.4 3263.98   309.2 3263.03
   316.3 3261.61   322.3 3261.16   340.2 3261.62   344.9 3263.25   348.9 3267.08
   353.8 3273.67   358.1 3276.47     382 3275.97   385.1 3276.58   386.5 3277.53
#Mann= 4 ,-1,0
       0     .12       0  116.73      .1       0   309.2    .045       0
   344.9     .06       0
Bank Sta=309.2,344.9
XS Rating Curve= 0 ,0
Exp/Cntr=0.3,0.1

Type RM Length L Ch R = 1 ,39374   ,213.5,218.5,222.3
XS GIS Cut Line= 2
2332833.82574633606189.5846585652332598.30995577606342.556681519
#Sta/Elev= 30
       0 3284.45    21.1 3275.96    47.2 3270.05    54.4 3269.28    83.1 3267.76
    92.6 3266.65   106.9 3266.36   122.3 3264.64   151.3 3262.81   159.4 3261.38
   171.5 3258.51   173.7 3257.67   178.4 3256.32   182.8 3256.22   190.2 3257.56
   192.8 3258.15   197.5 3258.41   211.8 3257.91   216.6 3257.38   229.3  3258.9
   235.1 3260.97   249.6 3267.31   254.8 3271.15   259.5 3275.84   261.1 3276.68
     264 3277.59   266.9 3277.86   273.8 3278.15   278.6  3277.8   280.8 3278.84
#Mann= 5 ,-1,0
       0     .12       0      50      .1       0   173.7    .045       0
   190.2      .1       0     230     .06       0
Bank Sta=173.7,190.2
XS Rating Curve= 0 ,0
Exp/Cntr=0.3,0.1

Type RM Length L Ch R = 1 ,39156   ,198,198.1,195.4
XS GIS Cut Line= 2
2332727.37772662606048.0424900322332490.44075998606133.246423848
#Sta/Elev= 30
       0 3276.56     6.5 3273.34    24.7 3266.14    37.8 3262.53    59.7 3261.07
    71.4  3260.9    79.9 3258.26    84.7 3257.28    88.4 3257.07   101.2 3257.59
   109.7 3256.68   126.7 3255.71   129.5 3254.99   135.2 3254.03   143.7    3254
   151.23254.638     166 3255.11   173.4  3254.3   177.7 3254.37   190.4 3255.54
   203.2 3256.19   211.7 3257.44     216 3258.33   229.1 3268.25   232.9 3270.89
   234.8 3271.67   237.9 3272.51   245.7 3272.86   249.9 3272.73   251.8 3273.23
#Mann= 5 ,-1,0
       0      .1       0     110     .06       0   129.5    .045       0
   151.2     .06       0     220     .12       0
Bank Sta=129.5,151.2
XS Rating Curve= 0 ,0
Exp/Cntr(USF)=0,0
Exp/Cntr=0.3,0.1

Type RM Length L Ch R = 1 ,38958   ,217.2,217.7,218.3
XS GIS Cut Line= 2
2332636.79644171605882.5770722082332394.58067741606014.595574375
#Sta/Elev= 30
       0 3286.51    18.9 3275.82    28.9 3271.45    41.7 3264.44    49.6 3261.36
    55.4 3258.01    64.3 3254.77    70.2 3255.14      82    3257    87.9 3257.21
    93.8 3256.66   100.9 3254.12   105.5 3253.78   132.1 3255.87   146.9 3254.61
   160.2 3254.25   178.4 3254.91   182.9 3254.33     192 3251.85   196.6 3251.65
   205.7 3252.33   211.7 3254.41   219.4 3258.05   223.5 3260.81   237.6 3272.96
   241.2 3273.79   251.3 3274.17   255.8    3275   264.8 3280.66   275.9 3289.19
#Mann= 4 ,-1,0
       0     .12       0   182.9    .045       0   211.7     .12       0
     240     .06       0
#XS Ineff= 2 , 0
           90.14 3269.26
Permanent Ineff=
       F       F
Bank Sta=182.9,211.7
XS Rating Curve= 0 ,0
Exp/Cntr(USF)=0,0
Exp/Cntr=0.3,0.1

Type RM Length L Ch R = 1 ,38740   ,233.1,229.2,223.1
XS GIS Cut Line= 2
2332538.23319763605694.5542701172332303.79379188605815.495379986
#Sta/Elev= 30
       0 3290.96    15.8 3284.48    24.3 3281.64    38.3 3275.71    58.1 3268.51
    69.8 3263.29    87.8 3258.64    95.5  3257.1   105.8 3252.85   110.3 3251.47
   123.8 3249.92   137.3 3250.38   146.3 3251.05   150.8 3250.81   155.3 3249.84
   164.3  3249.8   173.3 3248.73   186.9 3249.11   190.93250.042   200.4 3252.05
   209.4 3251.41   211.3 3251.64   222.9 3253.99   227.4 3255.57     238 3260.68
   240.9 3262.49   246.9 3267.45   249.9 3269.22   254.4    3270   263.8 3269.99
#Mann= 6 ,-1,0
       0     .12       0      20      .1       0     130     .12       0
   164.3    .045       0   190.9     .12       0     240     .06       0
Bank Sta=164.3,190.9
XS Rating Curve= 0 ,0
Exp/Cntr=0.3,0.1

Type RM Length L Ch R = 1 ,38511   ,217.3,214.2,210.7
XS GIS Cut Line= 2
2332424.03935144605486.5215657082332205.82695117605672.002105942
#Sta/Elev= 30
       0 3291.53    21.7 3281.44    27.3 3278.51    44.4 3270.78    61.4 3264.75
    65.9 3263.29    78.4 3260.13    83.8 3257.99   101.1 3247.87   103.9 3246.69
   106.8 3246.15   115.3 3245.78     121 3245.93   126.6 3247.18   135.2 3247.81
   141.6 3248.88   152.3 3249.84   173.1 3249.47   183.2 3248.11   199.3 3247.68
   204.6  3247.9   232.6  3250.8   246.6 3251.15   251.2 3252.07   257.2 3254.63
   262.9  3257.9   269.7 3263.09   272.8 3264.57   278.1 3265.32   286.4 3265.17
#Mann= 5 ,-1,0
       0     .12       0      60      .1       0   101.1    .045       0
   126.6      .1       0     220     .06       0
Bank Sta=101.1,126.6
XS Rating Curve= 0 ,0
Exp/Cntr(USF)=0,0
Exp/Cntr=0.3,0.1