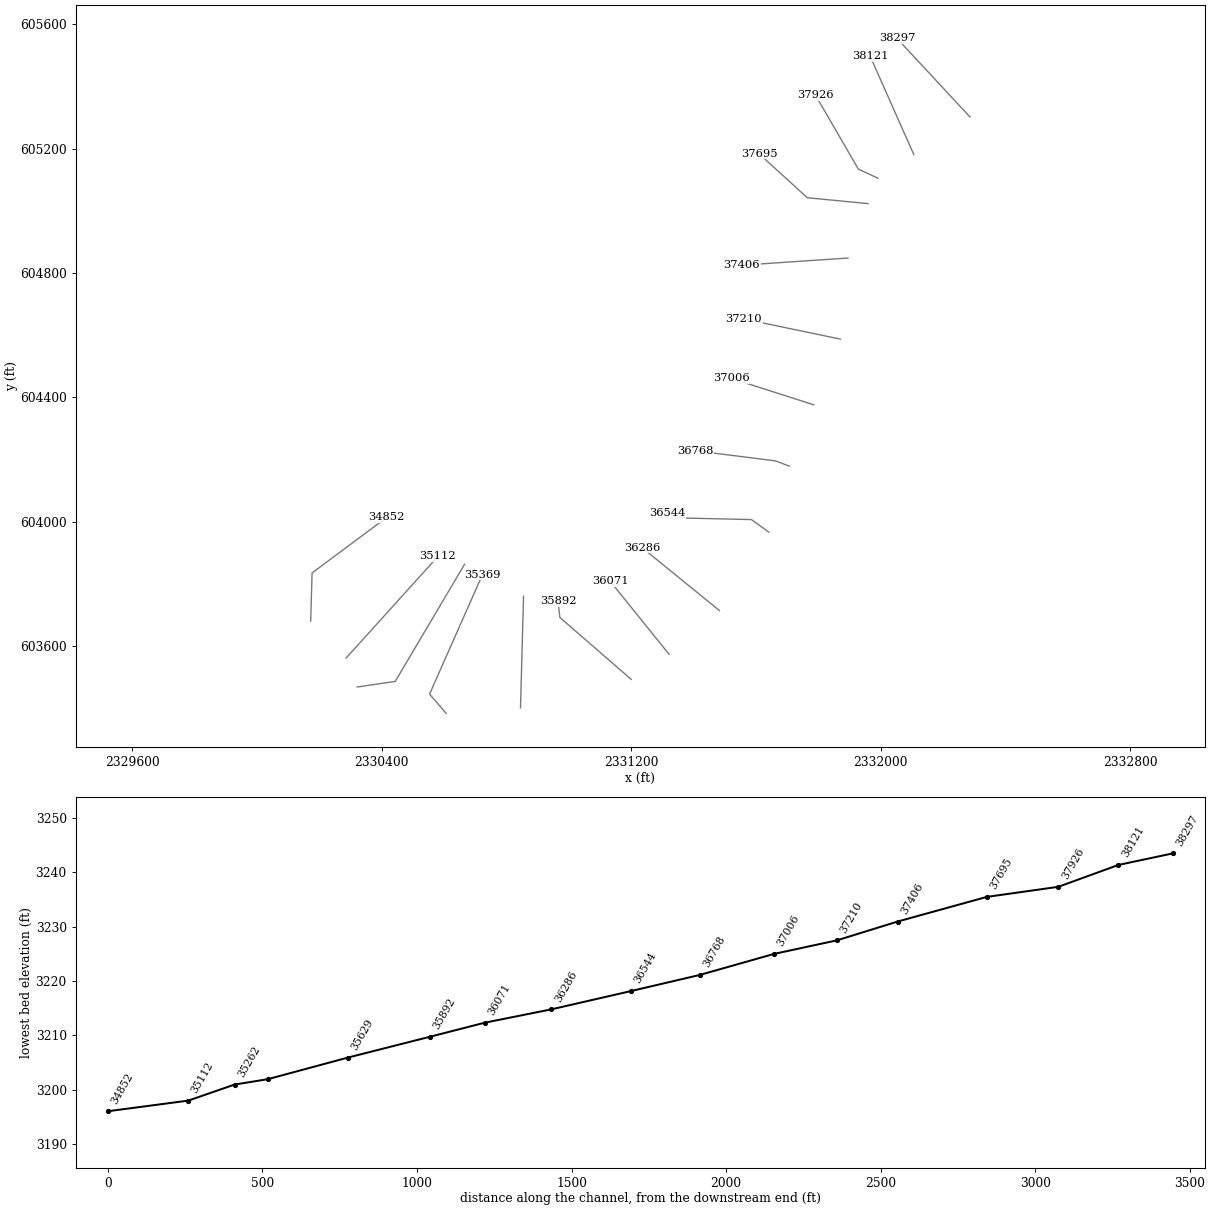
HEC-RAS study LTTLRV1.prj: LTTLRV1

--- LTTLRV1.g01 (geometry) --- (continued)

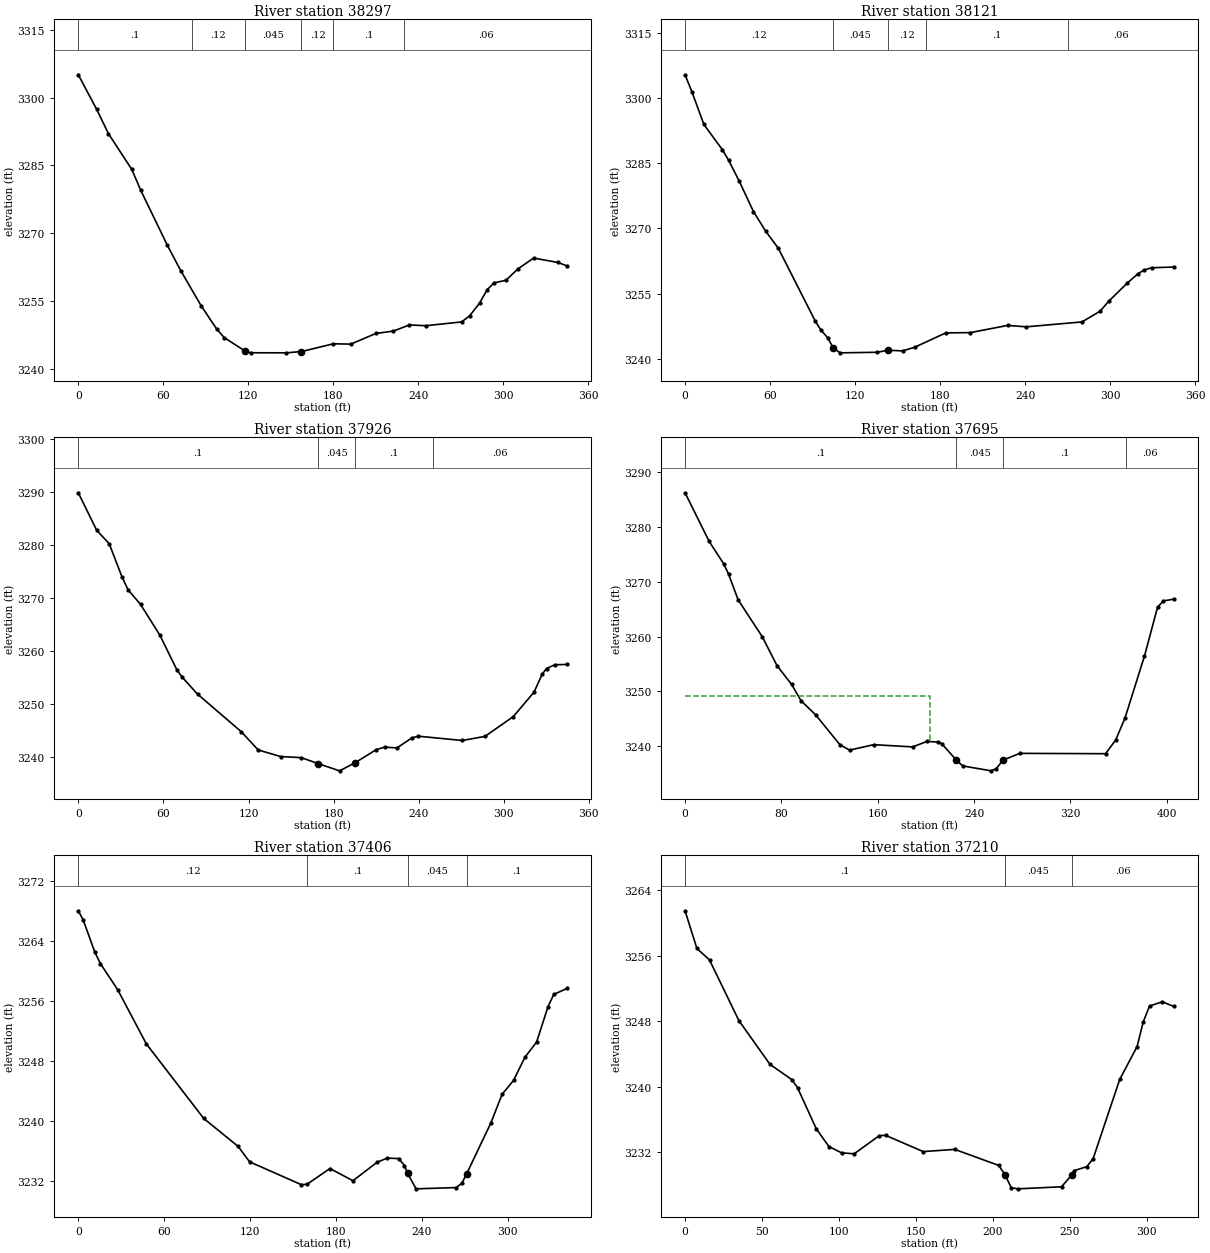
Type RM Length L Ch R = 1 ,38297   ,185.3,175.7,165.9
XS GIS Cut Line= 2
2332286.86684773605301.5544542992332052.51535423605554.404831774
#Sta/Elev= 30
       0 3305.03      13 3297.38    21.3 3291.99    37.7 3284.12    44.1 3279.45
    62.8 3267.33    72.4 3261.63    86.7 3253.92    97.7 3248.75   103.1 3246.85
   117.7 3243.91   121.6 3243.53   146.7 3243.51   157.53243.797     180 3245.51
   192.3 3245.44   209.9 3247.79   222.4 3248.33   233.7 3249.69   245.1 3249.51
   270.5 3250.35   276.2 3251.72   283.1 3254.49   288.5 3257.46   293.2 3258.97
   301.7 3259.57   310.4 3262.12   321.3 3264.48   338.5  3263.5   344.8 3262.75
#Mann= 6 ,-1,0
       0      .1       0      80     .12       0   117.7    .045       0
   157.5     .12       0     180      .1       0     230     .06       0
Bank Sta=117.7,157.5
XS Rating Curve= 0 ,0
Exp/Cntr=0.3,0.1

Type RM Length L Ch R = 1 ,38121   ,192.8,194.6,196.6
XS GIS Cut Line= 2
2332106.54030904605181.0242053222331966.88437287 605496.34112372
#Sta/Elev= 30
       0 3305.33     4.9 3301.37    13.3  3293.9    26.4 3288.08    30.8 3285.65
    38.3 3280.83    48.3 3273.86      57 3269.32    65.8 3265.45      92 3248.63
    95.9 3246.63   100.8 3244.81   104.6 3242.48   109.5 3241.39   135.8 3241.52
     1433241.993   153.5 3241.84     162 3242.67   184.1 3245.98   201.4 3246.04
   227.7  3247.7   240.8 3247.37   280.2  3248.5     293 3250.98     299 3253.25
     312 3257.39   319.5 3259.53   323.9 3260.43   329.4 3260.96   344.9 3261.12
#Mann= 5 ,-1,0
       0     .12       0   104.6    .045       0     143     .12       0
     170      .1       0     270     .06       0
Bank Sta=104.6,143
XS Rating Curve= 0 ,0
Exp/Cntr(USF)=0,0
Exp/Cntr=0.3,0.1

Type RM Length L Ch R = 1 ,37926   ,220.7,231,235.7
XS GIS Cut Line= 3
 2331991.9787989605104.6498652262331928.69720282605134.108539263
2331791.22339064605371.960055563
#Sta/Elev= 30
       0 3289.86      13 3282.76    21.8 3280.25    30.7 3274.05    35.1 3271.54
    43.9 3268.78    57.5 3262.99    69.5 3256.43    73.3 3255.02    84.1 3251.84
   114.9 3244.75   126.8 3241.31   142.6 3240.06   157.3 3239.85   169.1 3238.72
   184.2 3237.36   195.4 3238.92     210 3241.36   215.9 3241.84   224.7 3241.69
   235.1 3243.57   239.7  3243.9   270.7 3243.09   286.7 3243.86   306.7 3247.61
   321.3 3252.22   327.2 3255.68   330.1 3256.68   335.9 3257.39   344.5 3257.45
#Mann= 4 ,-1,0
       0      .1       0   169.1    .045       0   195.4      .1       0
   249.8     .06       0
Bank Sta=169.1,195.4
XS Rating Curve= 0 ,0
Exp/Cntr(USF)=0,0
Exp/Cntr=0.3,0.1

Type RM Length L Ch R = 1 ,37695   ,260.7,288.8,309.4
XS GIS Cut Line= 3
2331960.11946634605023.094515002 2331764.9753022605041.935764707
2331610.23797131605183.412575233
#Sta/Elev= 30
       0 3286.28      20 3277.41    32.1  3273.3    36.1 3271.44    44.1 3266.73
    64.2 3259.96    76.3 3254.74    88.4  3251.3    96.4 3248.29   108.4 3245.74
   128.5  3240.3   136.6 3239.29   156.7 3240.29   188.9 3239.88   200.9 3240.88
   210.2 3240.77   213.1 3240.48     2253237.523   230.5 3236.41   254.2 3235.51
   258.4 3235.91     264 3237.47   277.9  3238.7   349.1 3238.64   357.5 3241.13
   365.2 3245.11   381.4 3256.45   392.3 3265.39   397.1 3266.54   405.7 3266.85
#Mann= 4 ,-1,0
       0      .1       0     225    .045       0     264      .1       0
  366.05     .06       0
#XS Ineff= 2 , 0
          203.16 3249.09
Permanent Ineff=
       F       F
Bank Sta=225,264
XS Rating Curve= 0 ,0
Exp/Cntr=0.3,0.1

Type RM Length L Ch R = 1 ,37406   ,205.9,196.3,188.8
XS GIS Cut Line= 2
2331895.60165544604848.1290657912331554.94785279 604825.09553465
#Sta/Elev= 30
       0 3268.04     3.4 3266.83    11.5 3262.56    15.5 3260.98    27.5 3257.53
    47.5 3250.31    87.6 3240.36   111.7 3236.62   119.7 3234.57   155.8 3231.53
   159.8 3231.57   175.8 3233.68   191.9 3232.05   208.8 3234.52   215.9 3235.07
   223.9    3235   227.9 3234.07   230.1 3233.02     236 3230.97     264 3231.14
     268 3231.71   271.4 3233.01   288.1 3239.69   296.1 3243.57   304.1 3245.43
   312.1 3248.53   320.2 3250.54   328.2 3255.27   332.2 3256.89   341.4 3257.68
#Mann= 4 ,-1,0
       0     .12       0     160      .1       0   230.1    .045       0
   271.4      .1       0
Bank Sta=230.1,271.4
XS Rating Curve= 0 ,0
Exp/Cntr(USF)=0,0
Exp/Cntr=0.3,0.1

Type RM Length L Ch R = 1 ,37210   ,207.7,204.5,202.2
XS GIS Cut Line= 2
2331871.71791771604587.3528618642331560.87055461 604652.34933285
#Sta/Elev= 30
       0 3261.48     7.7 3256.88    15.9 3255.47      35 3248.06    55.2 3242.72
    69.4 3240.85    73.1 3239.87    85.3 3234.84    93.5 3232.68   101.7 3231.91
   109.9 3231.79   126.2    3234   130.3 3234.05   154.8 3232.06   175.3 3232.33
   203.9 3230.37   207.9 3229.24     212 3227.66   216.1 3227.51   244.7 3227.76
   251.3  3229.2   252.9 3229.73   261.1 3230.22   265.2 3231.18   282.5 3240.87
   293.8 3244.89   297.8 3247.91   301.9 3249.84   310.1 3250.36   317.6  3249.8
#Mann= 3 ,-1,0
       0      .1       0   207.9    .045       0   251.3     .06       0
Bank Sta=207.9,251.3
XS Rating Curve= 0 ,0
Exp/Cntr=0.3,0.1

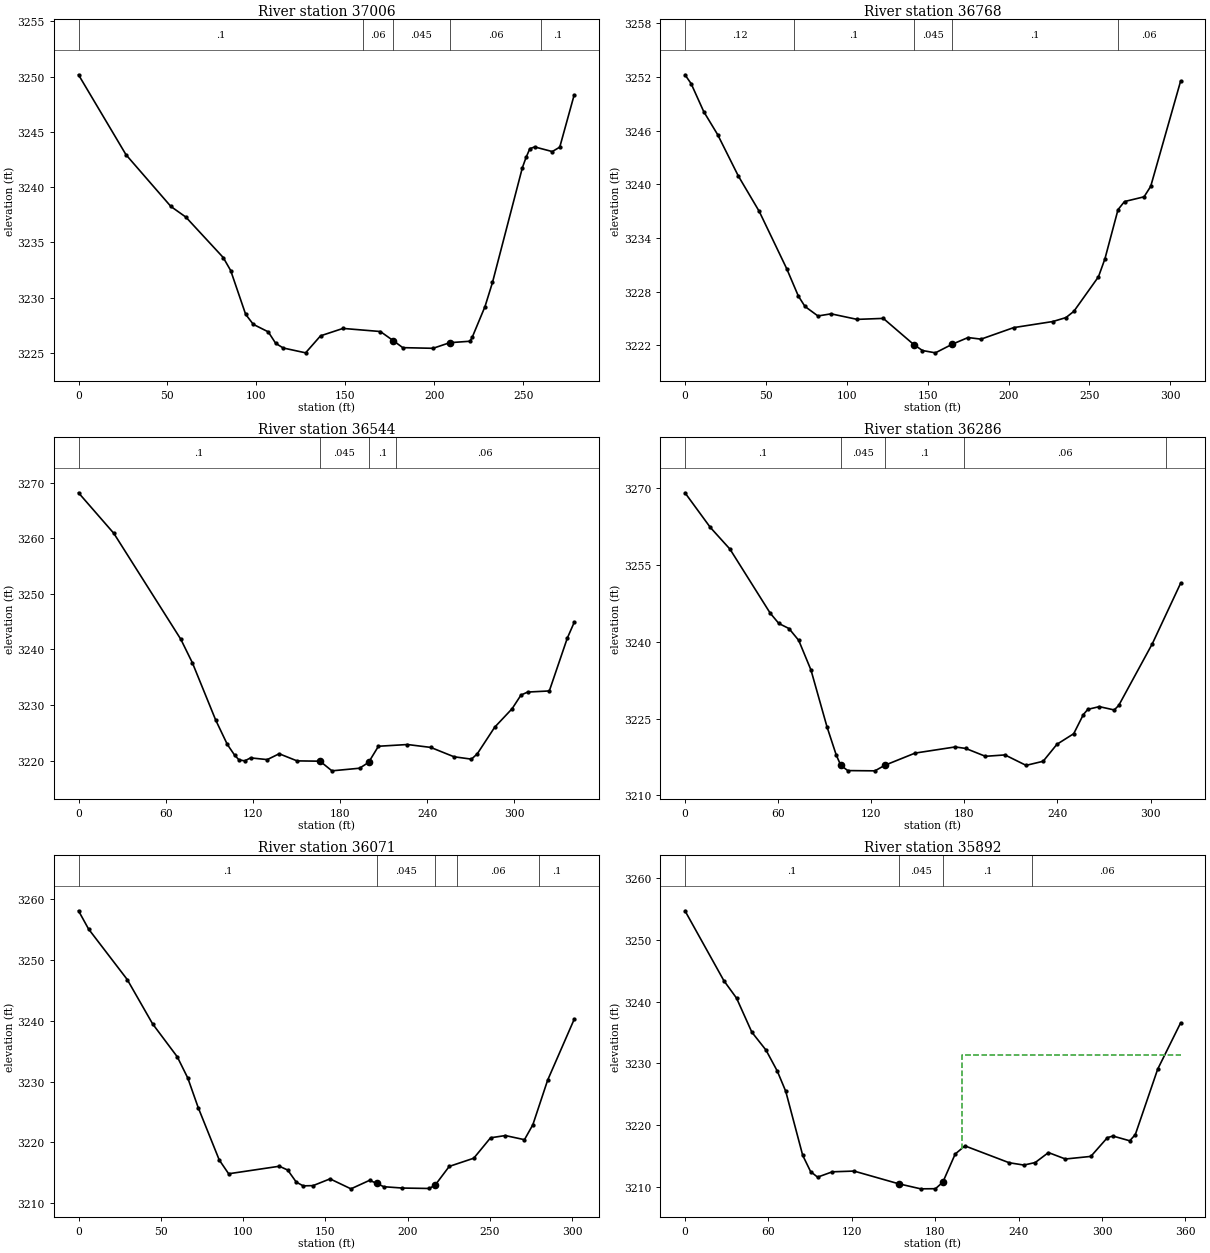
Type RM Length L Ch R = 1 ,37006   ,232,237.9,241.1
XS GIS Cut Line= 2
 2331785.6293269604376.3106465012331520.50126056604461.413482609
#Sta/Elev= 30
       0 3250.17    26.7 3242.93    51.9 3238.25    60.3 3237.29    81.3 3233.63
    85.5 3232.45    93.9 3228.49    98.2 3227.58   106.6  3226.9   110.8 3225.86
     115 3225.44   127.6    3225     136 3226.54   148.6 3227.21   169.6 3226.93
   176.8 3226.11   182.2 3225.47   199.2 3225.41   208.6 3225.92     220 3226.05
   221.3 3226.44   228.4 3229.19   232.6 3231.37   249.4 3241.76   251.5  3242.7
   253.6 3243.48   256.3 3243.64   266.2 3243.22   270.4 3243.62   278.5 3248.34
#Mann= 5 ,-1,0
       0      .1       0     160     .06       0   176.8    .045       0
   208.6     .06       0     260      .1       0
Bank Sta=176.8,208.6
XS Rating Curve= 0 ,0
Exp/Cntr(USF)=0,0
Exp/Cntr=0.3,0.1

Type RM Length L Ch R = 1 ,36768   ,220,223.5,228.2
XS GIS Cut Line= 3
2331707.06370281604179.2099384132331662.48494802604196.066837627
2331405.74803326604228.535017004
#Sta/Elev= 30
       0 3252.24     3.8 3251.25    11.6 3248.12    20.2 3245.55      33 3240.92
    45.9 3236.97    62.9 3230.56    70.1  3227.5    74.2 3226.34    82.2 3225.28
    90.3 3225.52   106.4  3224.9   122.6 3225.01   141.4 3222.09   146.8 3221.42
   154.8 3221.16   165.3 3222.13     175 3222.87     183 3222.69   203.2 3223.98
   227.4 3224.66   235.5  3225.1   240.4  3225.8   255.6 3229.66   259.6 3231.67
   267.7 3237.17   271.7 3238.07   283.8  3238.6   287.9 3239.77   306.4 3251.54
#Mann= 5 ,-1,0
       0     .12       0   67.66      .1       0   141.4    .045       0
   165.3      .1       0  267.66     .06       0
Bank Sta=141.4,165.3
XS Rating Curve= 0 ,0
Exp/Cntr=0.3,0.1

Type RM Length L Ch R = 1 ,36544   ,272.9,257.9,239.1
XS GIS Cut Line= 4
2331641.45909219603966.9212869072331585.81493012604007.290580958
2331351.23659983604012.7458909652331316.32261578604026.929696983
#Sta/Elev= 30
       0 3268.16    24.3 3260.87    70.4 3241.83    78.4 3237.58    94.4 3227.31
   102.4 3222.93   107.4 3221.01   110.4 3220.16   114.4 3219.97   118.4 3220.51
   129.9  3220.2   138.1 3221.25   150.4 3219.97   166.23219.915   174.4 3218.18
   193.4 3218.65   199.6 3219.69   206.4  3222.6   226.4 3222.91   242.4 3222.39
   258.4 3220.71   270.4 3220.28   274.4 3221.23   286.4 3226.02   298.4 3229.35
   304.5  3231.8   309.1 3232.34     324 3232.54   336.4 3242.05   341.1 3244.85
#Mann= 4 ,-1,0
       0      .1       0   166.2    .045       0   199.6      .1       0
  218.75     .06       0
Bank Sta=166.2,199.6
XS Rating Curve= 0 ,0
Exp/Cntr(USF)=0,0
Exp/Cntr=0.3,0.1

Type RM Length L Ch R = 1 ,36286   ,214.6,214.9,207.5
XS GIS Cut Line= 2
2331483.07523569603714.8637722842331235.49733827603916.725669704
#Sta/Elev= 30
       0 3269.16    16.3  3262.4      29 3258.14    54.9 3245.64    60.5 3243.61
      67 3242.63    73.3 3240.31    81.2 3234.51    91.5 3223.43    97.5 3217.88
   100.4 3215.89   104.9 3214.86   122.4 3214.81   128.8  3215.9   148.3 3218.28
   174.1 3219.48   180.9 3219.19   193.6 3217.65   206.2 3217.92   219.8 3215.88
   230.8 3216.68   239.7    3220   250.5 3222.07   256.7  3225.8   259.6 3226.83
     267 3227.36   276.6 3226.71   279.5 3227.59   301.2 3239.68   319.4 3251.48
#Mann= 5 ,-1,0
       0      .1       0   100.4    .045       0   128.8      .1       0
     180     .06       0     310     .12       0
Bank Sta=100.4,128.8
XS Rating Curve= 0 ,0
Exp/Cntr=0.3,0.1

Type RM Length L Ch R = 1 ,36071   ,174,179.1,183.2
XS GIS Cut Line= 2
2331321.77792579603574.1389664112331133.02419955603808.717296708
#Sta/Elev= 30
       0 3258.13     6.1 3255.13    29.6 3246.81      45 3239.52      60 3234.09
    66.4 3230.59    72.7 3225.74    85.5 3217.11    91.2 3214.84     122 3216.08
   127.1 3215.45   132.3 3213.46   136.5 3212.85   142.5 3212.89   152.8    3214
   165.5 3212.36   176.8 3213.76   181.2 3213.26   185.4 3212.71   196.8 3212.49
   213.1 3212.42   216.7 3212.99   225.2 3216.05   240.1  3217.4   250.3 3220.76
   259.3 3221.13   270.9 3220.45     276 3222.91     285 3230.26   301.1 3240.26
#Mann= 5 ,-1,0
       0      .1       0   181.2    .045       0   216.7      .1       0
     230     .06       0     280      .1       0
Bank Sta=181.2,216.7
XS Rating Curve= 0 ,0
Exp/Cntr(USF)=0,0
Exp/Cntr=0.3,0.1

Type RM Length L Ch R = 1 ,35892   ,287.9,263.7,240.7
XS GIS Cut Line= 3
2331200.18512719603493.6428365322330971.30456512603692.579808116
2330965.36433867603745.556929739
#Sta/Elev= 30
       0 3254.67      28 3243.37    37.1 3240.56    48.1 3235.06    58.3 3232.16
    66.4 3228.78    72.5  3225.5    84.7 3215.16    90.4 3212.53    95.4 3211.64
     106  3212.5   121.6 3212.62   153.7 3210.57   169.6 3209.75   180.2 3209.77
   185.5 3210.82   194.4 3215.37   201.4 3216.69   233.2 3213.97   243.8 3213.59
     252    3214   261.5 3215.61   273.7 3214.57     292 3214.99   303.9 3218.02
   307.9 3218.28     320 3217.51     324 3218.52   340.1 3229.09   356.6 3236.56
#Mann= 4 ,-1,0
       0      .1       0   153.7    .045       0   185.5      .1       0
     250     .06       0
#XS Ineff= 2 , 0
                          199.03         3231.31
Permanent Ineff=
       F       F
Bank Sta=153.7,185.5
XS Rating Curve= 0 ,0
Exp/Cntr(USF)=0,0
Exp/Cntr=0.3,0.1

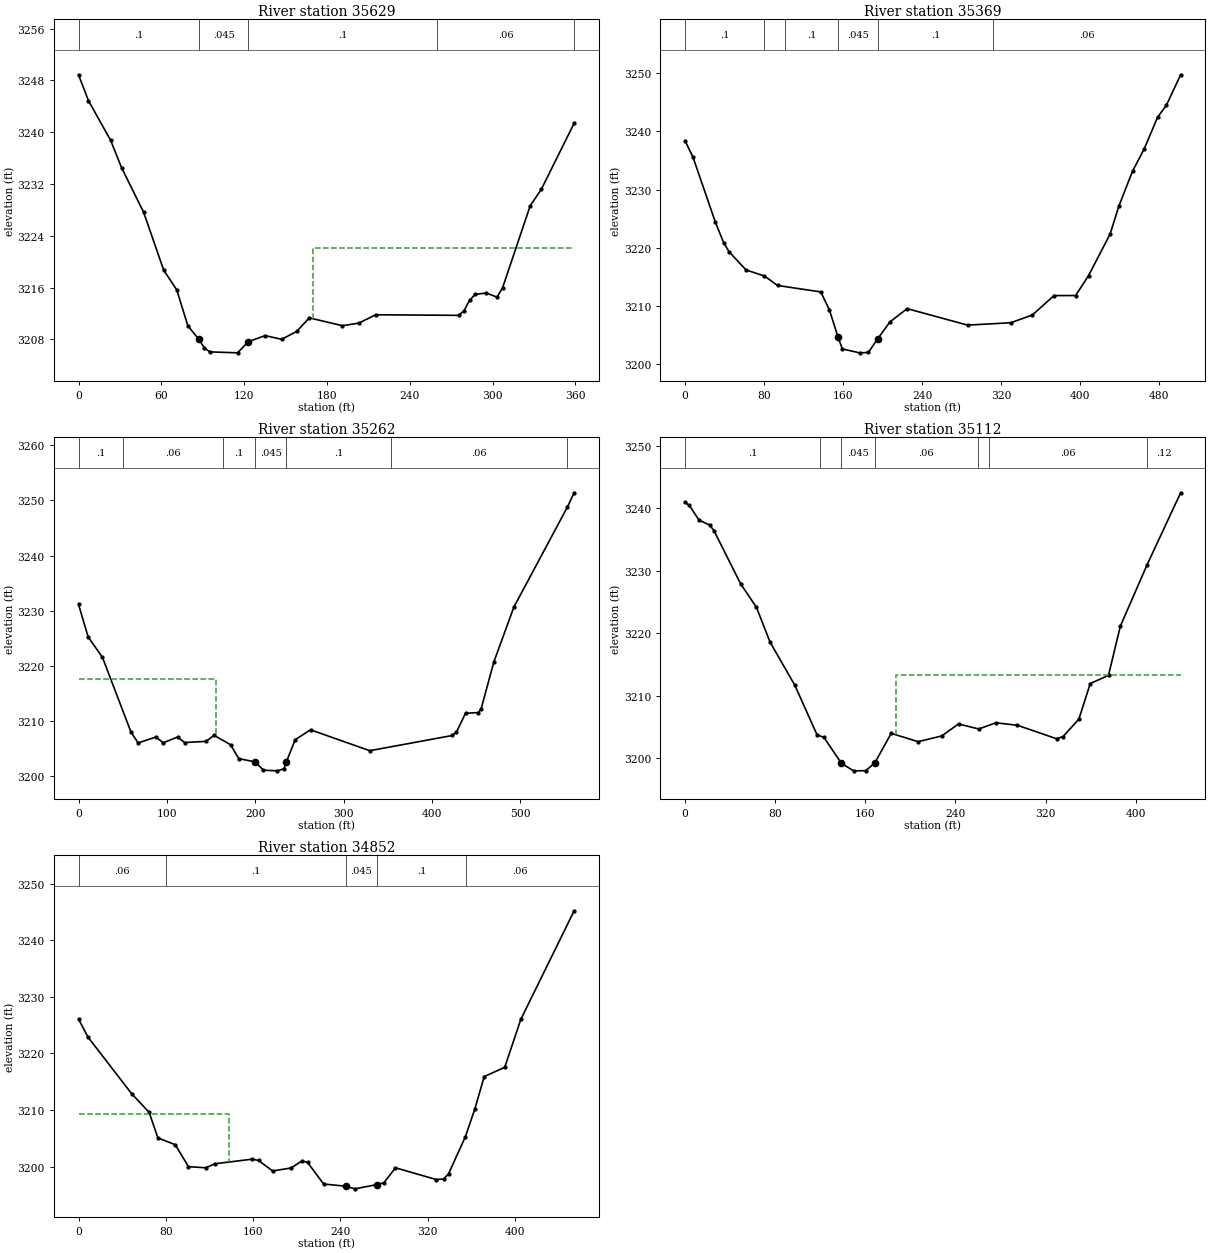
Type RM Length L Ch R = 1 ,35629   ,270,259.5,247
XS GIS Cut Line= 2
2330845.01799091603402.0064331732330854.84454444603760.972424079
#Sta/Elev= 30
       0 3248.88     7.2 3244.88    23.2 3238.79    31.2 3234.53    47.2 3227.64
    61.7 3218.72    71.2 3215.65    79.2 3210.13    87.2 3208.03    91.2 3206.69
    95.2 3206.09   115.2 3205.94     123 3207.66   135.2  3208.6   147.2 3208.03
   158.1 3209.25   167.2 3211.34   191.2 3210.13   203.2 3210.54   215.3 3211.82
   275.3 3211.73   279.3 3212.42   283.3 3214.05   287.3 3214.95   295.3 3215.18
   303.3 3214.54   307.3 3216.03   327.3 3228.68   335.3 3231.19   359.1  3241.4
#Mann= 5 ,-1,0
       0      .1       0    87.2    .045       0     123      .1       0
     260     .06       0   359.1      .1       0
#XS Ineff= 2 , 0
                          169.66         3222.09
Permanent Ineff=
       F       F
Bank Sta=87.2,123
XS Rating Curve= 0 ,0
Exp/Cntr=0.3,0.1

Type RM Length L Ch R = 1 ,35369   ,110.2,107.3,104
XS GIS Cut Line= 3
2330606.65678976603384.304012367 2330553.3159808603446.130859111
2330723.03673657603830.427141818
#Sta/Elev= 30
       0 3238.41     8.1 3235.56    30.7 3224.43    39.2 3220.85    44.9 3219.26
    61.9 3216.19    80.4 3215.16    93.7 3213.53   137.5 3212.42   146.2 3209.34
     155 3204.63   159.3 3202.63   176.8 3201.96   185.6 3202.02   195.3 3204.42
   207.5 3207.27   224.9 3209.55   286.1 3206.72   329.9 3207.13   351.7 3208.46
   373.6 3211.79   395.5  3211.8   408.6 3215.23   430.4 3222.36   439.2 3227.12
   453.1 3233.16     465 3237.01   478.5 3242.44   487.3 3244.45   501.8 3249.71
#Mann= 6 ,-1,0
       0      .1       0      80     .06       0  101.66      .1       0
     155    .045       0   195.3      .1       0  311.66     .06       0
Bank Sta=155,195.3
XS Rating Curve= 0 ,0
Exp/Cntr(USF)=0,0
Exp/Cntr=0.3,0.1

Type RM Length L Ch R = 1 ,35262   ,156.3,150.3,144.7
XS GIS Cut Line= 3
2330321.39592442603469.1432715122330443.09324213603486.967279917
2330665.82102659603863.839421978
#Sta/Elev= 30
       0 3231.16    10.9 3225.25    27.1 3221.54    59.4 3207.98    67.5 3206.03
    87.7 3207.11    95.8 3206.05     112  3207.1     120  3206.1   144.2 3206.31
   153.4 3207.41     172 3205.71   181.3 3203.19   199.9 3202.59   209.2 3201.09
   224.7 3200.97   232.4 3201.33   235.2  3202.6   245.1 3206.61   262.5 3208.41
   329.5 3204.62   422.9 3207.38   427.6 3207.99   437.9 3211.41   452.5 3211.53
   455.5 3212.21     470 3220.75   492.6 3230.67     553 3248.76   560.8 3251.39
#Mann= 7 ,-1,0
       0      .1       0      50     .06       0     163      .1       0
   199.9    .045       0   235.2      .1       0     353     .06       0
     553      .1       0
#XS Ineff= 2 , 0
          155.36 3217.62
Permanent Ineff=
       F       F
Bank Sta=199.9,235.2
XS Rating Curve= 0 ,0
Exp/Cntr=0.3,0.1

Type RM Length L Ch R = 1 ,35112   ,261.6,259.7,251.8
XS GIS Cut Line= 2
2330285.58948915603562.1140216032330580.18564868603888.731502827
#Sta/Elev= 30
       0  3240.9     3.9 3240.43    12.5 3238.07    21.8  3237.3    25.7 3236.41
    49.3 3227.92    63.4 3224.15    75.5 3218.58    97.5 3211.68   117.2 3203.76
   123.3 3203.36   138.8 3199.21   149.6 3198.01   160.3 3198.03   168.3 3199.24
     183    3204   206.9 3202.67   227.7 3203.58   242.7  3205.5   260.7  3204.7
   275.9 3205.69     295 3205.29   329.7 3203.14   335.4 3203.48   349.5 3206.27
   359.6 3211.96   375.8 3213.27   386.3 3221.13     410 3230.93   439.8 3242.45
#Mann= 7 ,-1,0
       0      .1       0     120     .06       0   138.8    .045       0
   168.3     .06       0     260      .1       0     270     .06       0
     410     .12       0
#XS Ineff= 2 , 0
                          187.25         3213.37
Permanent Ineff=
       F       F
Bank Sta=138.8,168.3
XS Rating Curve= 0 ,0
Exp/Cntr(USF)=0,0
Exp/Cntr=0.3,0.1

Type RM Length L Ch R = 1 ,34852   ,276.5,295.3,315.8
XS GIS Cut Line= 3
2330171.94710423603680.4789130352330176.51858787603835.720730432
2330416.00112506604014.475923081
#Sta/Elev= 30
       0 3226.07     8.7 3222.87    48.7 3212.87    64.7 3209.58    72.7 3205.07
    88.7 3203.85   100.7 3199.98   116.8 3199.78   124.8 3200.49     159  3201.3
   164.9 3201.08   177.8 3199.22   194.8 3199.75   204.8    3201   209.8 3200.74
   224.6 3196.91   244.7 3196.53   253.3 3196.06   273.3 3196.81   279.7 3197.12
   290.4 3199.78   327.6 3197.71   334.6 3197.79     339 3198.71   354.5  3205.3
     363 3210.12   371.7  3215.9   390.5 3217.54   405.2    3226   454.1  3245.2
#Mann= 5 ,-1,0
       0     .06       0      80      .1       0   244.7    .045       0
   273.3      .1       0  355.31     .06       0
#XS Ineff= 2 , 0
          137.55  3209.3
Permanent Ineff=
       F       F
Bank Sta=244.7,273.3
XS Rating Curve= 0 ,0
Exp/Cntr=0.3,0.1