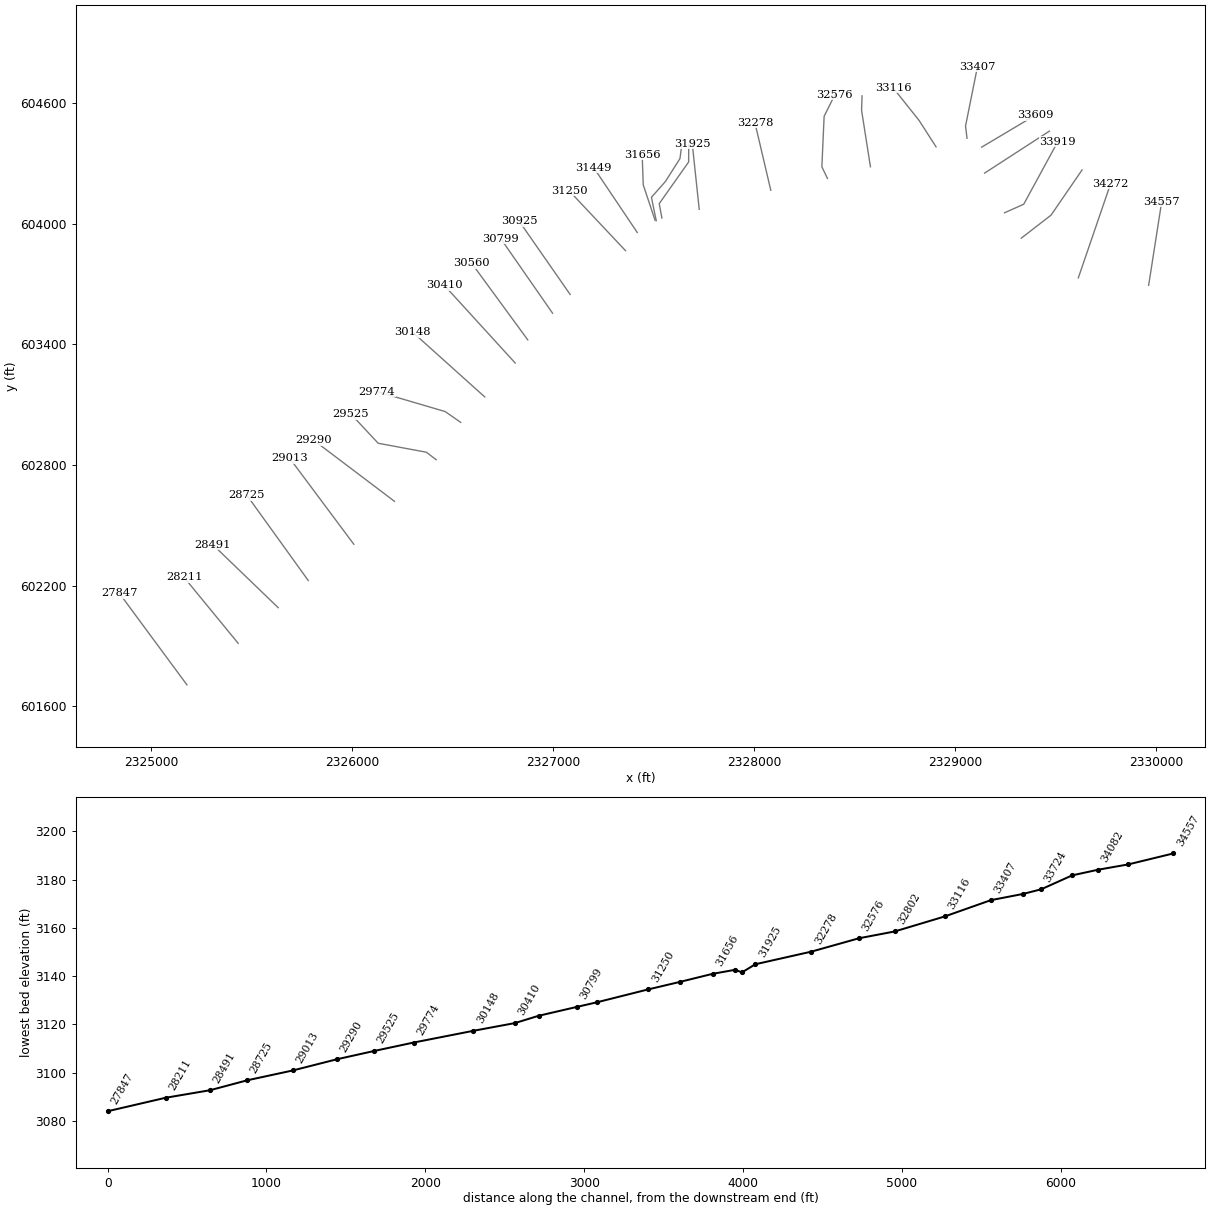
HEC-RAS study LTTLRV1.prj: LTTLRV1

--- LTTLRV1.g01 (geometry) --- (continued)

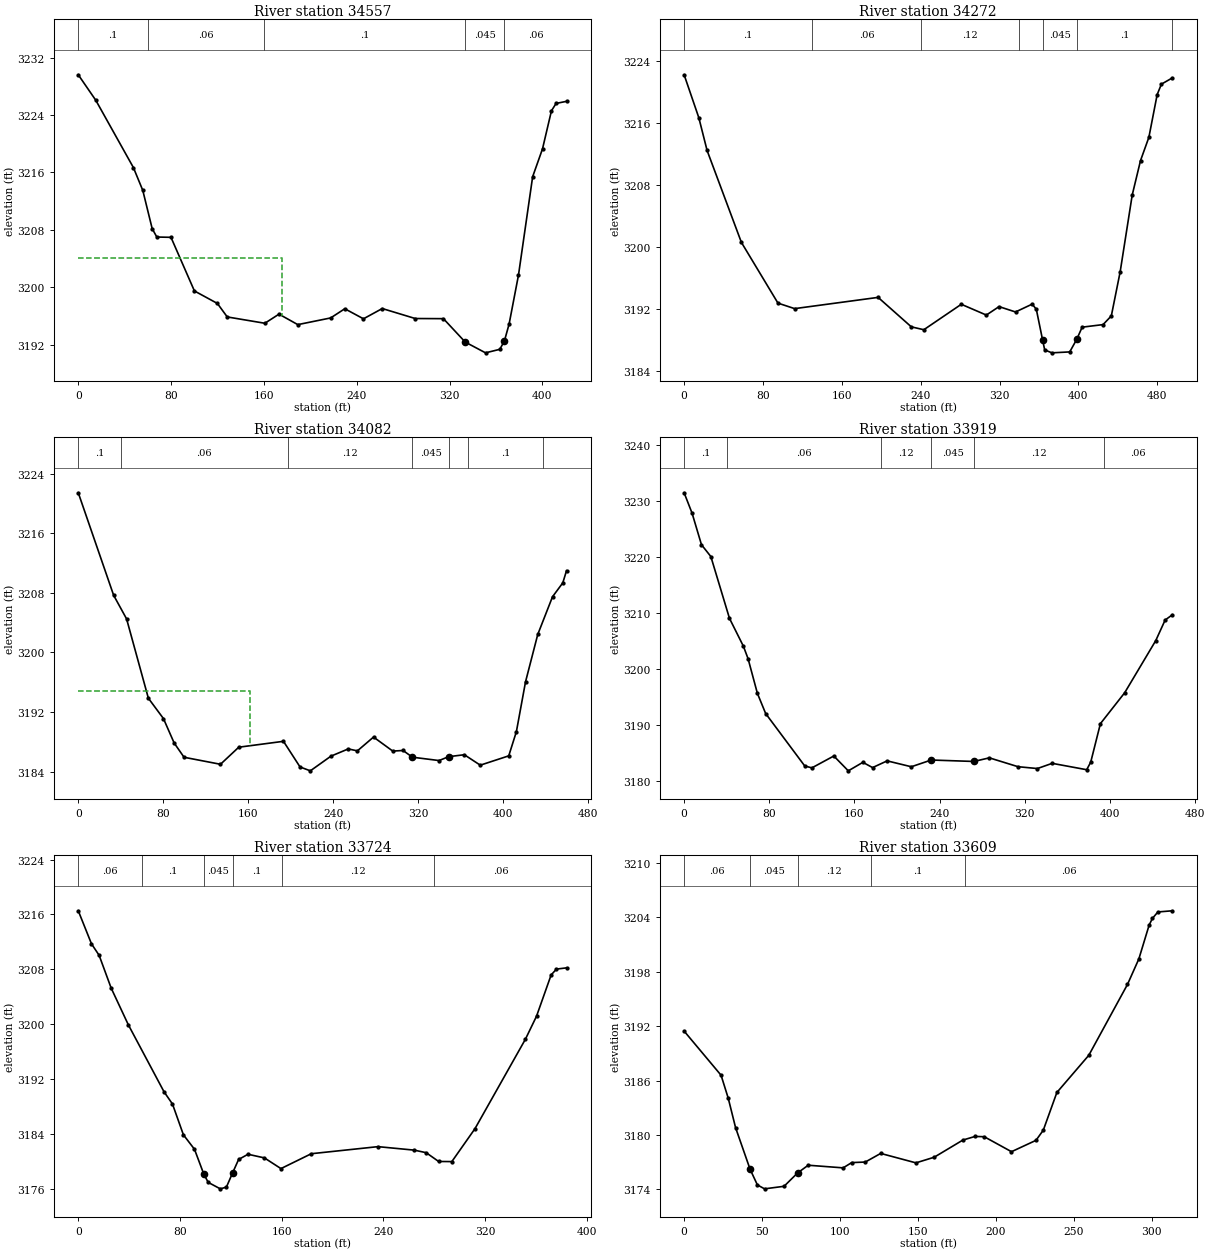
Type RM Length L Ch R = 1 ,34557   ,289.9,284.5,280.4
XS GIS Cut Line= 2
2329962.15194798603694.2680585252330027.00702808604110.005751474
#Sta/Elev= 30
       0 3229.61    15.1 3226.06    47.5 3216.69    55.6 3213.51    63.7 3208.18
    67.7 3207.01    79.9 3206.97   100.1  3199.5   119.9 3197.76   128.4 3195.88
   160.8    3195     173 3196.27   189.2 3194.81   217.5 3195.74   229.7 3197.02
   245.8 3195.62     262 3197.05   290.4 3195.66   314.7 3195.64   333.5 3192.38
     351 3190.88   363.3 3191.37   367.3 3192.55   371.3 3194.88   379.4 3201.71
   391.6 3215.41   400.1 3219.29   407.8 3224.59   411.8 3225.62   420.8 3225.91
#Mann= 5 ,-1,0
       0      .1       0      60     .06       0     160      .1       0
   333.5    .045       0   367.3     .06       0
#XS Ineff= 2 , 0
           175.7 3204.07
Permanent Ineff=
       F       F
Bank Sta=333.5,367.3
XS Rating Curve= 0 ,0
Exp/Cntr(USF)=0,0
Exp/Cntr=0.3,0.1

Type RM Length L Ch R = 1 ,34272   ,198.4,189.8,183.8
XS GIS Cut Line= 2
2329612.40878765603731.1206370462329772.87315061604199.750747184
#Sta/Elev= 30
       0 3222.17    14.9 3216.64    23.3 3212.41    58.1 3200.56    95.2 3192.73
   112.1 3192.02   196.8 3193.47   230.5 3189.67   243.2  3189.3   281.2 3192.58
   306.6 3191.19   319.5 3192.28   336.2 3191.59   353.1  3192.6   357.3 3191.94
   363.6 3188.02   365.8  3186.7   373.1 3186.32   391.2 3186.44   398.3 3188.06
   403.8 3189.63     425 3189.96   433.4 3191.08   442.4 3196.79   454.6 3206.67
     463  3211.1   471.5 3214.11   479.9 3219.61   484.2 3220.96   495.3 3221.77
#Mann= 7 ,-1,0
       0      .1       0     130     .06       0     240     .12       0
     340      .1       0   363.6    .045       0   398.3      .1       0
  495.34     .06       0
Bank Sta=363.6,398.3
XS Rating Curve= 0 ,0
Exp/Cntr=0.3,0.1

Type RM Length L Ch R = 1 ,34082   ,159.8,163.2,164.8
XS GIS Cut Line= 3
2329328.79620404603928.7640574412329476.78226136604043.343412059
2329630.95662039604268.135000244
#Sta/Elev= 30
       0 3221.42    33.3 3207.67    45.5  3204.5      66 3193.86    80.2 3191.13
    90.3 3187.85    99.6 3185.94   133.9    3185   151.1 3187.29   193.2 3188.08
   208.8 3184.64   218.5 3184.12   237.9 3186.09   254.2 3187.06   262.8  3186.8
     278 3188.65   296.1 3186.77   305.8 3186.85   314.6 3185.95   339.7  3185.5
   348.7 3186.02   363.5 3186.28   378.5 3184.88   405.3 3186.13   412.5 3189.38
   421.1 3196.06   432.6 3202.41   446.5 3207.47   456.2 3209.34   459.7 3210.97
#Mann= 7 ,-1,0
       0      .1       0      40     .06       0  197.16     .12       0
   314.6    .045       0   348.7     .12       0  367.16      .1       0
  437.16     .06       0
#XS Ineff= 2 , 0
          161.65 3194.81
Permanent Ineff=
       F       F
Bank Sta=314.6,348.7
XS Rating Curve= 0 ,0
Exp/Cntr(USF)=0,0
Exp/Cntr=0.3,0.1

Type RM Length L Ch R = 1 ,33919   ,206.4,195.4,186.6
XS GIS Cut Line= 3
2329245.29194956604054.9673764982329340.77871429604097.510984546
2329510.00773297604408.552030059
#Sta/Elev= 30
       0 3231.45     7.5 3227.79    16.3 3222.17    25.1 3220.06    42.6 3209.02
    55.7 3204.03    60.1 3201.79    68.8 3195.63    76.6 3192.01   113.3 3182.65
     120 3182.31   140.6 3184.43   154.2 3181.78   167.9  3183.3     177 3182.36
   190.7 3183.56   213.4 3182.51   232.13183.713   272.13183.456   286.7  3184.1
   313.6 3182.52   331.8 3182.19   345.7 3183.12   378.1 3181.98   381.9 3183.33
     391 3190.21   413.8 3195.73     443 3205.05   451.8 3208.72   458.6 3209.66
#Mann= 6 ,-1,0
       0      .1       0      40     .06       0  184.54     .12       0
   232.1    .045       0   272.1     .12       0  394.54     .06       0
Bank Sta=232.1,272.1
XS Rating Curve= 0 ,0
Exp/Cntr(USF)=0,0
Exp/Cntr=0.3,0.1

Type RM Length L Ch R = 1 ,33724   ,115.6,114.7,114.1
XS GIS Cut Line= 2
2329146.40454252604252.5214543952329468.54544297604461.446168819
#Sta/Elev= 30
       0 3216.53    10.4 3211.71    16.4 3210.04    25.9 3205.25    39.4  3199.9
    67.4 3190.16    74.1 3188.36    82.7 3183.87    91.4 3181.77    98.7 3178.16
   102.2 3176.94   111.7    3176   116.5 3176.25   121.3 3178.29   126.1 3180.28
   133.5 3181.04   146.4 3180.51   159.4 3178.95   183.3 3181.12   235.7 3182.15
   264.3 3181.64   273.6 3181.27   283.4 3179.99   293.8 3179.97     312 3184.77
   351.7 3197.82   360.4 3201.16   371.9 3207.18   376.1 3208.03     384 3208.21
#Mann= 6 ,-1,0
       0     .06       0      50      .1       0    98.7    .045       0
   121.3      .1       0     160     .12       0     280     .06       0
Bank Sta=98.7,121.3
XS Rating Curve= 0 ,0
Exp/Cntr(USF)=0,0
Exp/Cntr=0.3,0.1

Type RM Length L Ch R = 1 ,33609   ,179.2,201.9,222.1
XS GIS Cut Line= 2
2329131.81373294604381.7322822262329400.96300647604541.920676354
#Sta/Elev= 30
       0 3191.44    23.7 3186.58    28.3 3184.05      33 3180.81    42.3 3176.23
      47  3174.5    51.6 3174.07    64.1 3174.35    72.8 3175.82    79.6 3176.67
     102 3176.38   107.5 3176.96   116.2 3177.02   126.1 3177.97   148.7 3176.93
   160.4 3177.55   178.8 3179.44   186.6 3179.84   192.5 3179.81     210 3178.16
   225.7 3179.41   230.4 3180.53   239.1 3184.68   259.6 3188.78   284.4 3196.58
   291.7 3199.39   298.3 3203.12   300.4 3203.85   303.9 3204.56   313.2 3204.69
#Mann= 5 ,-1,0
       0     .06       0    42.3    .045       0    72.8     .12       0
     120      .1       0     180     .06       0
Bank Sta=42.3,72.8
XS Rating Curve= 0 ,0
Exp/Cntr(USF)=0,0
Exp/Cntr=0.3,0.1

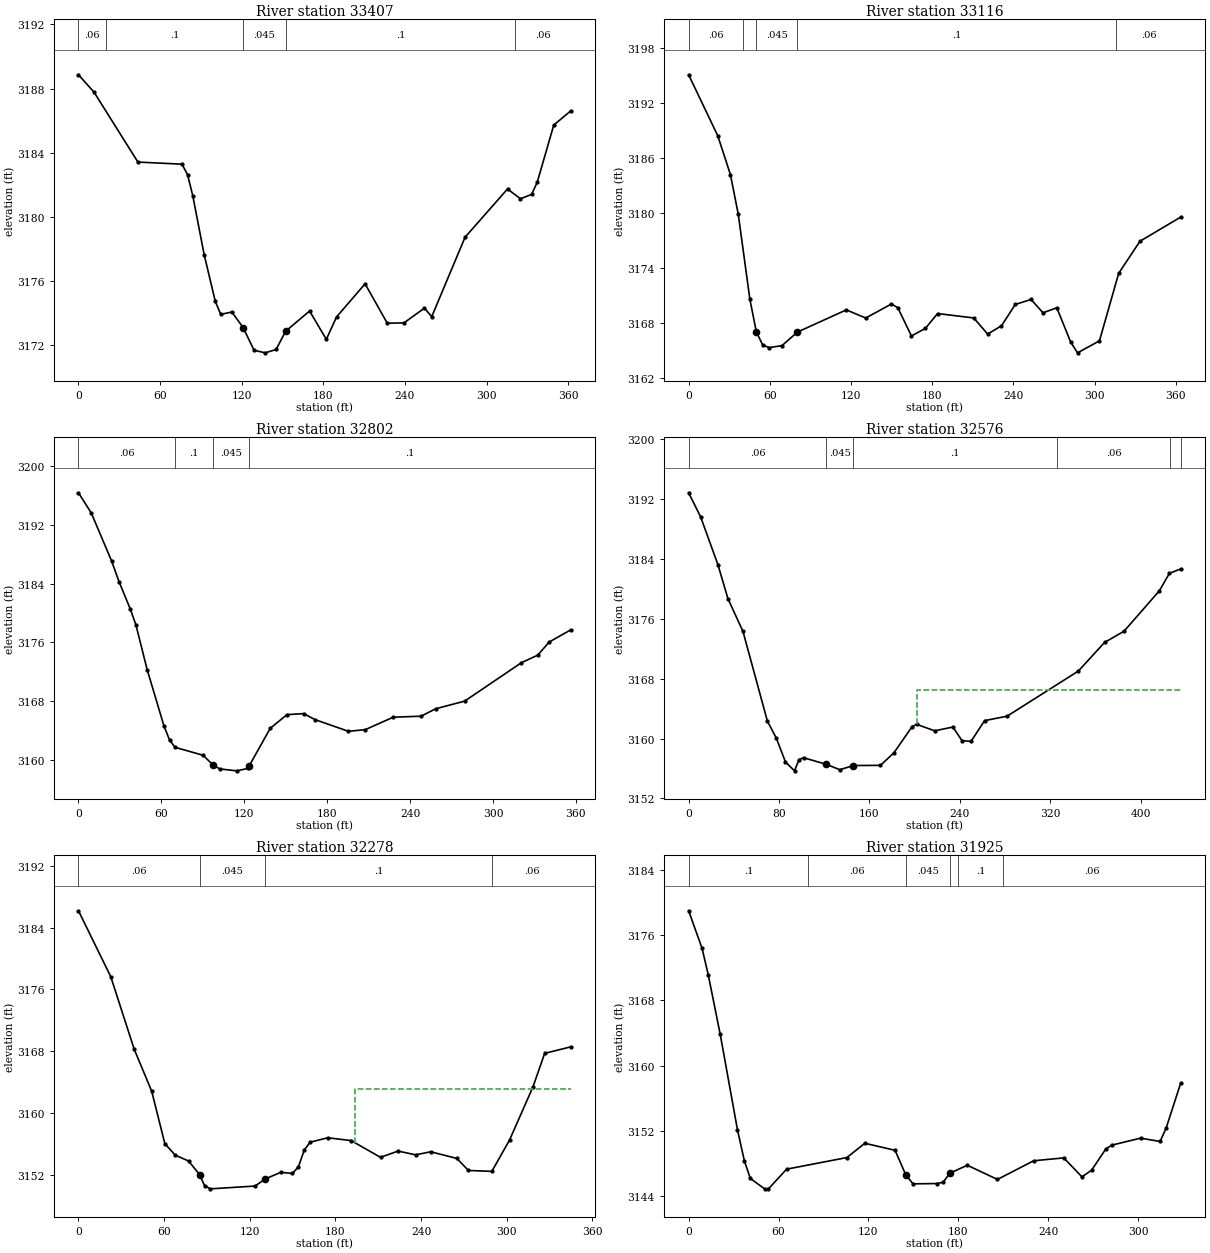
Type RM Length L Ch R = 1 ,33407   ,268.7,291.2,306.9
XS GIS Cut Line= 3
2329058.83788069604425.8385901152329051.44739917604486.515899198
2329110.60907958604781.265692846
#Sta/Elev= 30
       0 3188.86    11.4 3187.78    43.7 3183.41    76.1 3183.28    80.2 3182.62
      84 3181.32    92.4 3177.63   100.6 3174.71   104.6  3173.9   112.8 3174.05
     121 3173.08   129.1 3171.66   137.3  3171.5   145.3 3171.71   152.3 3172.85
   169.9 3174.11   182.2 3172.34   189.7 3173.74   210.7 3175.81     227 3173.35
   239.3 3173.37   254.3 3174.29   259.7 3173.76   284.2 3178.72   315.4 3181.73
   324.9 3181.12   333.1 3181.39   337.2 3182.14   349.4 3185.72   361.8  3186.6
#Mann= 5 ,-1,0
       0     .06       0      20      .1       0     121    .045       0
   152.3      .1       0  321.13     .06       0
Bank Sta=121,152.3
XS Rating Curve= 0 ,0
Exp/Cntr=0.3,0.1

Type RM Length L Ch R = 1 ,33116   ,324.1,313.9,303.9
XS GIS Cut Line= 3
2328904.79236761604383.0836255652328820.60922942604514.442722186
2328691.29259548604676.847338806
#Sta/Elev= 30
       0 3195.09    21.5 3188.44    30.9 3184.18    36.7 3179.84    45.2 3170.62
      50 3167.03    54.7 3165.59    59.5  3165.3      69 3165.52    80.33166.992
   116.5 3169.42   130.8 3168.53   149.8 3170.06   154.5 3169.67   164.6 3166.57
   174.9  3167.4   183.9 3169.02   210.6 3168.54   220.9 3166.78   231.1 3167.68
   241.3 3170.01     253 3170.56   261.8  3169.1     272 3169.65   282.2 3165.92
   287.3 3164.73   303.5 3166.04   317.7 3173.41   333.4 3176.91   363.6 3179.56
#Mann= 5 ,-1,0
       0     .06       0      40      .1       0      50    .045       0
    80.3      .1       0  316.02     .06       0
Bank Sta=50,80.3
XS Rating Curve= 0 ,0
Exp/Cntr(USF)=0,0
Exp/Cntr=0.3,0.1

Type RM Length L Ch R = 1 ,32802   ,230.8,226.2,222.1
XS GIS Cut Line= 3
2328578.49093486604284.1057902232328534.37695284604565.268619759
 2328536.9221882604636.827011784
#Sta/Elev= 30
       0 3196.38     9.2 3193.66      24 3187.09    29.4 3184.26    37.5 3180.56
    41.6 3178.38    49.7 3172.32    61.8 3164.69    65.9 3162.73    69.9 3161.73
    90.2 3160.65    97.5 3159.31   102.3 3158.79   114.5 3158.53   122.6 3158.86
   123.4 3159.15   138.8 3164.32   150.9 3166.18     163 3166.32   171.1 3165.51
   195.4 3163.91   207.6 3164.14   227.8 3165.83     248 3165.97   258.5 3166.98
   279.5 3168.02   320.5 3173.24   332.4 3174.28   340.7 3176.07   356.2 3177.71
#Mann= 4 ,-1,0
       0     .06       0      70      .1       0    97.5    .045       0
   123.4      .1       0
Bank Sta=97.5,123.4
XS Rating Curve= 0 ,0
Exp/Cntr=0.3,0.1

Type RM Length L Ch R = 1 ,32576   ,292.1,298.3,302.2
XS GIS Cut Line= 4
2328364.74150229604225.7896688792328336.96524586604283.840713724
2328348.17154367604535.2639502592328401.63358174604642.188026393
#Sta/Elev= 30
       0 3192.81    10.6  3189.6    25.9 3183.22    34.8 3178.67    48.1  3174.3
    69.7 3162.33    77.7 3160.03    85.7 3156.87    93.7 3155.69    97.7 3157.19
   101.7 3157.44   121.7 3156.57   133.8 3155.84   145.8  3156.4   169.8 3156.42
   181.8 3158.12   197.8 3161.59   201.8  3161.9   217.8 3161.03   233.9 3161.54
   241.9 3159.73   249.9 3159.61   261.9 3162.39   281.9 3162.99     345 3169.02
   368.1 3172.83   385.3 3174.32   416.6 3179.72   425.5 3182.05   435.6 3182.65
#Mann= 6 ,-1,0
       0     .06       0   121.7    .045       0   145.8      .1       0
  326.03     .06       0  426.03      .1       0  435.57     .06       0
#XS Ineff= 2 , 0
                          201.81         3166.46
Permanent Ineff=
       F       F
Bank Sta=121.7,145.8
XS Rating Curve= 0 ,0
Exp/Cntr(USF)=0,0
Exp/Cntr=0.3,0.1

Type RM Length L Ch R = 1 ,32278   ,356.5,353.2,348.4
XS GIS Cut Line= 2
2328082.91671244604167.208371199 2328004.0779368604502.895354192
#Sta/Elev= 30
       0 3186.17    22.6 3177.65      39 3168.27    51.3 3162.81    60.5 3156.03
    67.8 3154.53    77.1 3153.78    84.9 3152.01    88.3 3150.59    92.4 3150.17
   123.7 3150.53   130.93151.451   141.7 3152.31   149.9 3152.16   154.1 3153.02
   158.2  3155.2   162.3 3156.21   174.6 3156.78     191 3156.42   211.6 3154.25
   223.9 3155.06   236.2 3154.57   246.8 3154.97     265 3154.11   273.2 3152.55
   289.6 3152.43     302 3156.49   318.4 3163.36   326.6 3167.71   344.8 3168.55
#Mann= 4 ,-1,0
       0     .06       0    84.9    .045       0   130.9      .1       0
     290     .06       0
#XS Ineff= 2 , 0
                          193.62         3163.07
Permanent Ineff=
       F       F
Bank Sta=84.9,130.9
XS Rating Curve= 0 ,0
Exp/Cntr=0.3,0.1

Type RM Length L Ch R = 1 ,31925   ,103.7,84.1,69.3
XS GIS Cut Line= 2
2327727.00037933604072.1925807732327692.33521722 604398.88547221
#Sta/Elev= 30
       0 3178.99       9 3174.37    13.1 3171.14    21.1 3163.84    32.6 3152.16
    37.2 3148.36    41.2  3146.2    50.7 3144.93    53.3 3144.93    65.4 3147.34
   105.6 3148.76   117.6 3150.51   137.8 3149.65  144.96 3146.63   149.8 3145.54
   165.9 3145.58   169.9 3145.74   174.33146.843     186 3147.82   206.1 3146.08
   230.3 3148.37   250.4 3148.72   262.5  3146.4   268.9  3147.2   278.5 3149.83
   282.6 3150.29   301.7 3151.14   314.7 3150.73   318.8 3152.42   328.5 3157.92
#Mann= 6 ,-1,0
       0      .1       0      80     .06       0  144.96    .045       0
   174.3     .06       0     180      .1       0     210     .06       0
Bank Sta=144.96,174.3
XS Rating Curve= 0 ,0
Exp/Cntr(USF)=0,0
Exp/Cntr=0.5,0.3

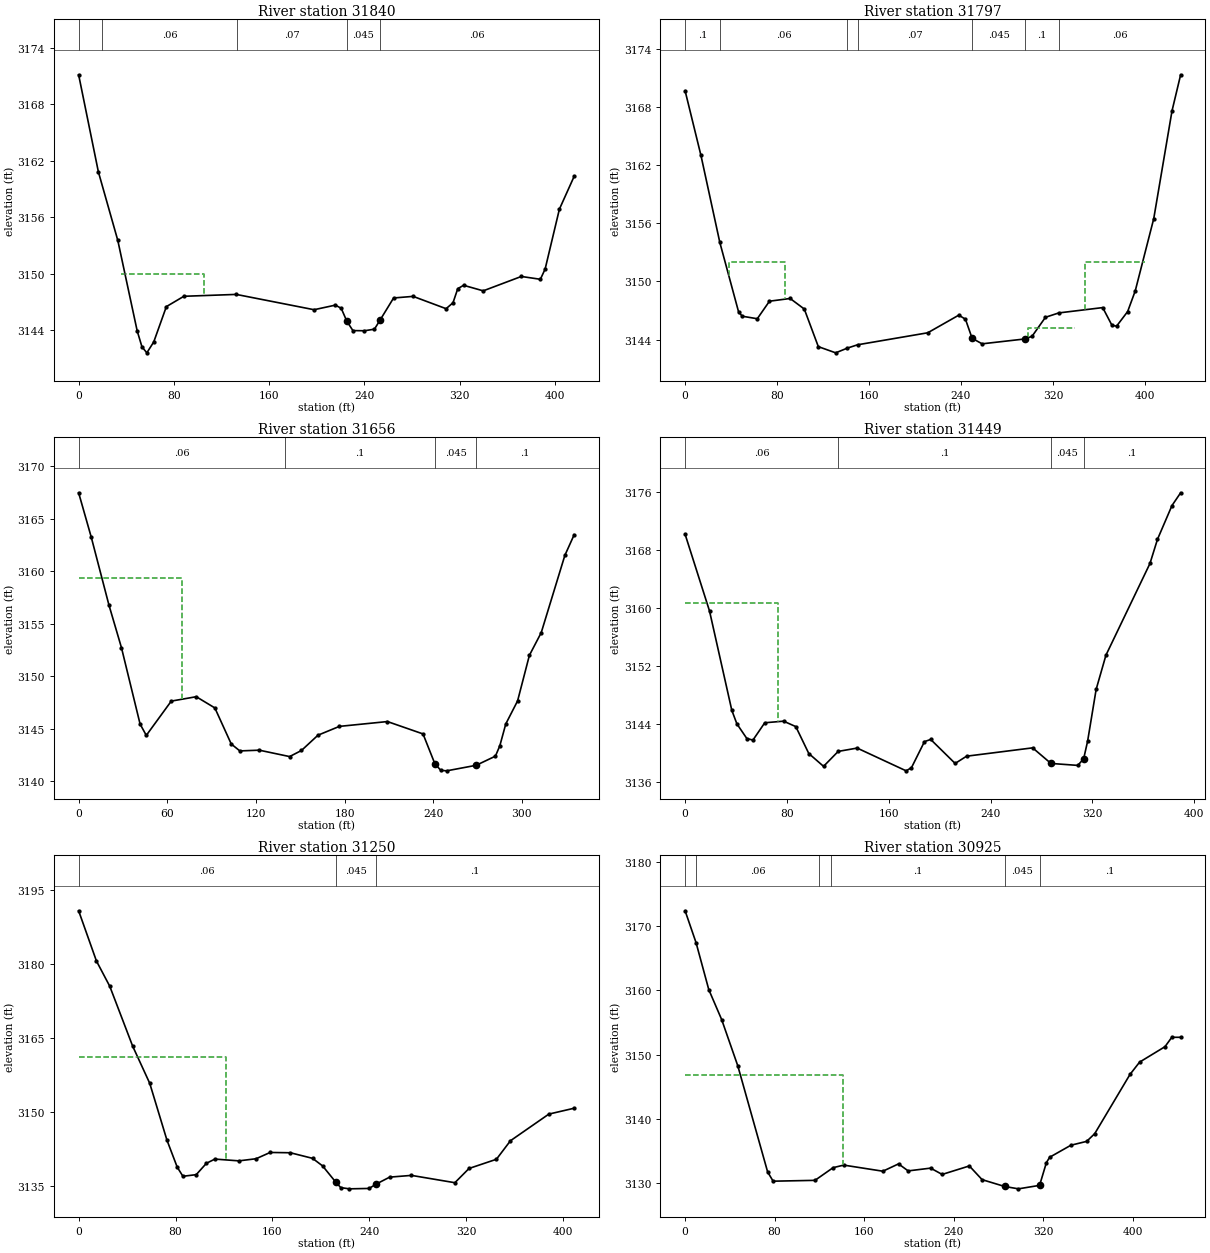
Type RM Length L Ch R = 1 ,31840   ,41.7,43.3,42.9
XS GIS Cut Line= 4
2327541.25349007604028.822595139 2327528.1488656604100.501489298
2327674.38075368604307.7264103022327674.83609023604397.512811893
#Sta/Elev= 30
       0 3171.16    16.6 3160.82    32.9 3153.53    49.2 3143.89    53.2  3142.2
    57.3 3141.56    63.1 3142.72    73.7 3146.48    88.4 3147.58   132.4 3147.78
   197.8 3146.15   215.7 3146.64   220.6  3146.3   225.3 3144.93   230.4 3143.93
   240.1 3143.91   248.5 3144.08   253.3 3145.06   264.6  3147.4     281 3147.57
   308.7 3146.26   314.5 3146.89   318.5 3148.39   323.4 3148.75   339.9 3148.16
   371.9 3149.69   387.9 3149.39   391.9 3150.48   403.9 3156.86   416.3 3160.35
#Mann= 5 ,-1,0
       0      .1       0      20     .06       0  132.87     .07       0
   225.3    .045       0   253.3     .06       0
#XS Ineff= 3 ,-1
      36     105    3150     105     214    3146     262     370  3145.6
Permanent Ineff=
       F       F       F
Bank Sta=225.3,253.3
XS Rating Curve= 0 ,0
Exp/Cntr(USF)=0,0
Exp/Cntr=0.5,0.3

Type RM Length L Ch R = 1 ,31797   ,125,140.9,159.5
XS GIS Cut Line= 5
2327513.29393522604015.6411114132327489.35554999604132.021058226
 2327559.0919901604210.9469074272327631.19361017604324.775345135
2327640.89193907604396.300520781
#Sta/Elev= 30
       0 3169.68    13.8    3163    30.2 3154.03    46.5 3146.87    49.7 3146.41
    62.8 3146.15    73.4 3147.96    91.4 3148.24   103.7 3147.15   115.9 3143.27
     131 3142.63   141.2 3143.12     150 3143.46   211.1  3144.7   238.1 3146.52
   243.9  3146.1   249.7 3144.13   258.4 3143.56   296.1 3144.07   301.9 3144.35
   313.5  3146.3   325.1 3146.75   363.3  3147.3   371.4 3145.46   375.4 3145.39
     385 3146.89   391.6 3149.02   407.7 3156.48   423.6 3167.61   431.1 3171.33
#Mann= 7 ,-1,0
       0      .1       0    30.2     .06       0   141.2      .1       0
     150     .07       0   249.7    .045       0   296.1      .1       0
   325.1     .06       0
#XS Ineff= 4 ,-1
      38      87    3152  103.83     245  3145.6  298.58  339.58  3145.2
     348     400    3152
Permanent Ineff=
       F       F       F       F
Bank Sta=249.7,296.1
XS Rating Curve= 0 ,0
Exp/Cntr(USF)=0,0
Exp/Cntr=0.5,0.3

Type RM Length L Ch R = 1 ,31656   ,193.7,207.6,219.7
XS GIS Cut Line= 3
2327507.43548087604017.7024903752327448.62862296  604194.0458779
2327443.34621137604343.478478869
#Sta/Elev= 30
       0 3167.49     8.5 3163.28    20.5 3156.79      29 3152.71    41.6 3145.43
    45.8 3144.35    62.7 3147.62    79.6 3148.04    92.2 3146.97   103.3 3143.53
   109.1 3142.87   122.3 3142.94   142.8 3142.33   150.8 3142.91     162 3144.37
   176.5 3145.21     209 3145.67   233.1 3144.49   241.1 3141.65   245.1 3141.02
   249.1 3140.97   269.1  3141.5   282.1 3142.37   285.1 3143.37   289.1 3145.44
   297.1 3147.64   305.1 3151.99   313.1 3154.15   329.1 3161.52   335.4 3163.49
#Mann= 4 ,-1,0
       0     .06       0     140      .1       0   241.1    .045       0
   269.1      .1       0
#XS Ineff= 2 , 0
           69.66 3159.38
Permanent Ineff=
       F       F
Bank Sta=241.1,269.1
XS Rating Curve= 0 ,0
Exp/Cntr=0.3,0.1

Type RM Length L Ch R = 1 ,31449   ,193.2,198.5,195.9
XS GIS Cut Line= 2
2327418.84809733603956.9466736362327201.87569628604280.278094807
#Sta/Elev= 30
       0 3170.23    19.2 3159.64    36.7 3145.95    40.7 3144.08    48.5 3142.06
    53.3 3141.84    62.6 3144.23    77.4 3144.45      87  3143.7    97.2 3139.99
   108.8 3138.22   120.3 3140.28   135.2 3140.74   173.7  3137.6   177.9 3138.04
   188.1 3141.63     193 3141.93   212.2 3138.62   221.2 3139.62   273.1 3140.77
   287.5 3138.62   308.6 3138.35   313.2 3139.27   316.3 3141.69     323 3148.83
   330.7 3153.55   365.3  3166.2   371.2 3169.53   382.6 3174.19   389.4 3175.95
#Mann= 4 ,-1,0
       0     .06       0     120      .1       0   287.5    .045       0
   313.2      .1       0
#XS Ineff= 2 , 0
           72.66 3160.79
Permanent Ineff=
       F       F
Bank Sta=287.5,313.2
XS Rating Curve= 0 ,0
Exp/Cntr(USF)=0,0
Exp/Cntr=0.3,0.1

Type RM Length L Ch R = 1 ,31250   ,330,325.5,321.8
XS GIS Cut Line= 2
2327360.46962804603866.4550454312327080.15609086604164.446169838
#Sta/Elev= 30
       0 3190.76    14.7  3180.6    25.7 3175.49    44.6 3163.38    58.7 3155.86
    72.9 3144.37    81.4 3138.89    86.1 3137.05    97.1 3137.38   105.5 3139.68
   112.5 3140.53   132.3 3140.17   146.5  3140.6   158.1 3141.87   174.8 3141.81
   193.1 3140.68   201.4 3139.15   212.4 3135.83   216.4 3134.76   223.4 3134.51
   239.8 3134.59   245.6 3135.47   256.8 3136.88   274.8 3137.23   310.6 3135.75
   322.3 3138.63   344.9 3140.49   356.5 3144.24   388.2 3149.63   409.1 3150.82
#Mann= 3 ,-1,0
       0     .06       0   212.4    .045       0   245.6      .1       0
#XS Ineff= 2 , 0
          121.26 3161.09
Permanent Ineff=
       F       F
Bank Sta=212.4,245.6
XS Rating Curve= 0 ,0
Exp/Cntr=0.3,0.1

Type RM Length L Ch R = 1 ,30925   ,125.6,125.7,126.5
XS GIS Cut Line= 2
2327085.12381344603648.5563691962326832.18900105604012.243702986
#Sta/Elev= 30
       0 3172.35     9.8 3167.39    21.2 3160.08    32.7 3155.43    47.1 3148.25
    73.8 3131.74    78.7 3130.31   116.1 3130.44   132.3 3132.41   141.8 3132.81
   176.8 3131.86   190.8    3133   199.4 3131.91   219.5 3132.34   229.8 3131.36
   254.1 3132.68   265.5 3130.55   285.6 3129.49     298 3129.12   316.9 3129.66
     323  3133.2   325.9 3134.03   344.9  3135.9     359  3136.5   366.2  3137.7
   397.7  3146.9   406.3 3148.82     429 3151.22   435.1 3152.68     443 3152.68
#Mann= 6 ,-1,0
       0      .1       0      10     .06       0     120     .07       0
     130      .1       0   285.6    .045       0   316.9      .1       0
#XS Ineff= 2 , 0
          141.55  3146.8
Permanent Ineff=
       F       F
Bank Sta=285.6,316.9
XS Rating Curve= 0 ,0
Exp/Cntr(USF)=0,0
Exp/Cntr=0.3,0.1

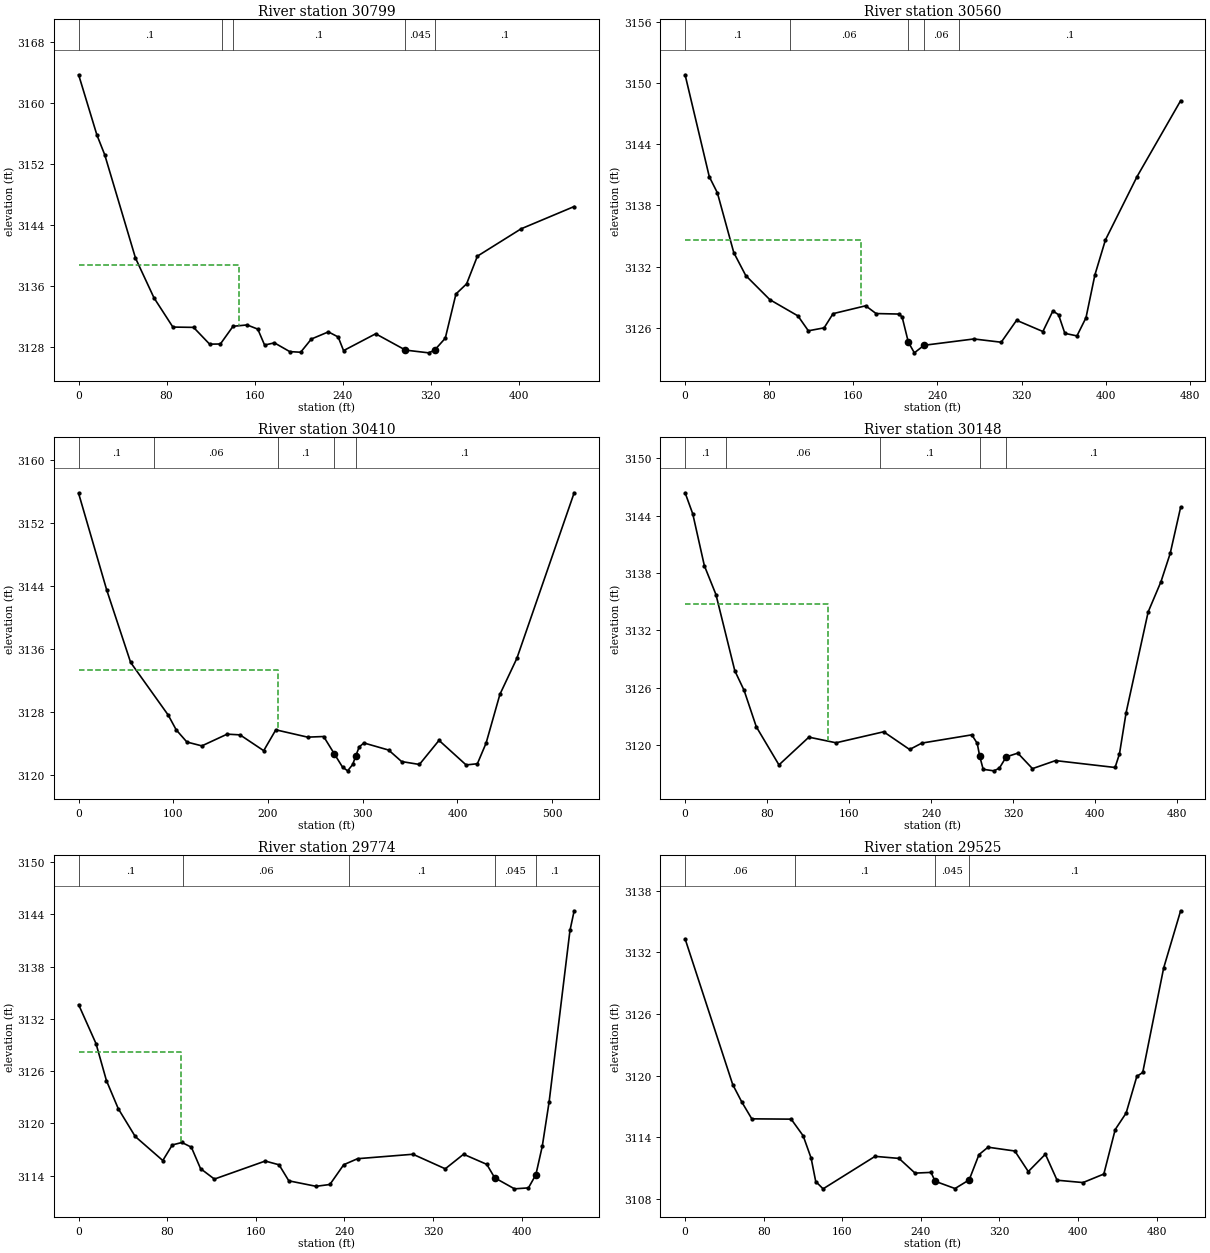
Type RM Length L Ch R = 1 ,30799   ,235.2,239.3,242.9
XS GIS Cut Line= 2
2326997.66637764603555.3350136552326740.70298503 603925.46440368
#Sta/Elev= 30
       0 3163.69    16.6  3155.8    23.7 3153.21    51.7 3139.65    68.5 3134.44
    85.7  3130.6   104.5 3130.56   119.1 3128.36   128.9 3128.38   140.4  3130.7
   153.2 3130.88   162.9 3130.33   169.1 3128.24     178 3128.53     192 3127.38
   201.9  3127.3   211.6 3129.03   227.1 3129.97     236  3129.3   240.9 3127.51
   270.1 3129.72   297.2 3127.58   318.2 3127.22   323.6 3127.56   333.4 3129.14
   343.1 3134.94   352.8 3136.27   362.6  3139.9   402.4 3143.49   450.6 3146.41
#Mann= 5 ,-1,0
       0      .1       0     130     .07       0     140      .1       0
   297.2    .045       0   323.6      .1       0
#XS Ineff= 2 , 0
          145.41 3138.68
Permanent Ineff=
       F       F
Bank Sta=297.2,323.6
XS Rating Curve= 0 ,0
Exp/Cntr(USF)=0,0
Exp/Cntr=0.3,0.1

Type RM Length L Ch R = 1 ,30560   ,146.5,149.2,151.2
XS GIS Cut Line= 2
 2326874.2899143603422.5989565422326596.05471766603802.938812499
#Sta/Elev= 30
       0 3150.81      23 3140.82    30.7 3139.24    46.3 3133.38    57.7 3131.13
    80.6 3128.77   107.3 3127.18   117.2 3125.72   132.2 3126.01   140.7  3127.4
   171.7 3128.17   181.6 3127.41   203.7 3127.36   206.4 3127.06   212.3  3124.6
     218 3123.56   227.2  3124.3   274.6 3124.92   300.6  3124.6   315.2 3126.75
   340.2 3125.65   349.7 3127.66   355.1  3127.3   361.1 3125.47   372.6 3125.22
   381.2    3127   389.7 3131.21   399.7 3134.63   429.8 3140.84   471.2 3148.27
#Mann= 5 ,-1,0
       0      .1       0     100     .06       0   212.3    .045       0
   227.2     .06       0     260      .1       0
#XS Ineff= 2 , 0
          167.63 3134.64
Permanent Ineff=
       F       F
Bank Sta=212.3,227.2
XS Rating Curve= 0 ,0
Exp/Cntr(USF)=0,0
Exp/Cntr=0.3,0.1

Type RM Length L Ch R = 1 ,30410   ,259.2,262.1,263.8
XS GIS Cut Line= 2
2326811.82735549 603307.293676772326459.32247927603693.914839362
#Sta/Elev= 30
       0 3155.78    29.6 3143.53    54.9 3134.31    94.6 3127.62     103 3125.75
   114.3  3124.2   130.1 3123.71   156.8  3125.2   170.4 3125.11   195.4  3123.1
   208.2 3125.75   241.8 3124.82   258.7  3124.9   270.1 3122.67   278.6 3121.02
     284 3120.54   289.4 3121.35   292.7 3122.48   296.3 3123.59   301.2 3124.08
   327.3 3123.18     341 3121.72   359.8 3121.35   380.5 3124.41   409.1 3121.29
     421 3121.44   430.2 3124.06   444.8 3130.26   462.7 3134.83   523.2 3155.86
#Mann= 5 ,-1,0
       0      .1       0      80     .06       0     210      .1       0
   270.1    .045       0   292.7      .1       0
#XS Ineff= 2 , 0
          211.01  3133.3
Permanent Ineff=
       F       F
Bank Sta=270.1,292.7
XS Rating Curve= 0 ,0
Exp/Cntr=0.3,0.1

Type RM Length L Ch R = 1 ,30148   ,355.2,374.2,384.3
XS GIS Cut Line= 2
 2326660.2706787603138.7054572652326300.62431528603461.983087301
#Sta/Elev= 30
       0 3146.38     7.5 3144.17    18.8 3138.76    30.1 3135.75    48.5 3127.79
    57.6 3125.73    69.5 3121.93    91.6 3117.95   120.8 3120.85   147.3 3120.26
   193.8 3121.41   219.1 3119.56   231.1 3120.23   279.8 3121.09   285.1  3120.2
   287.5 3118.86   290.9 3117.49   301.3 3117.33   306.7 3117.61   313.4 3118.79
   324.7 3119.18     339 3117.56   361.5  3118.4   419.6 3117.68   423.9  3119.1
   430.4 3123.42   451.9 3133.93   464.4 3137.09   473.4 3140.04   483.6 3144.87
#Mann= 5 ,-1,0
       0      .1       0      40     .06       0     190      .1       0
   287.5    .045       0   313.4      .1       0
#XS Ineff= 2 , 0
          139.13 3134.79
Permanent Ineff=
       F       F
Bank Sta=287.5,313.4
XS Rating Curve= 0 ,0
Exp/Cntr(USF)=0,0
Exp/Cntr=0.3,0.1

Type RM Length L Ch R = 1 ,29774   ,246,249.5,252.1
XS GIS Cut Line= 3
2326540.81924248603012.0412874422326463.15323639603065.892883309
2326124.53436663603165.499890034
#Sta/Elev= 30
       0 3133.63    15.7 3129.16    25.1 3124.92    35.8 3121.69    51.1  3118.5
      76 3115.74    84.6 3117.53    93.3 3117.81   101.8 3117.27   110.1 3114.81
   122.6 3113.61   168.5 3115.68     181 3115.25   189.8 3113.41   214.4 3112.78
   226.9 3112.99   239.4 3115.26   251.9 3115.95   301.9 3116.46   331.1 3114.79
   347.6 3116.46   368.6  3115.3   375.73113.762   393.6 3112.49   406.2  3112.6
   412.93114.108   418.7 3117.38   424.9 3122.49   443.7 3142.15   447.5 3144.41
#Mann= 5 ,-1,0
       0      .1       0   94.51     .06       0  244.51      .1       0
   375.7    .045       0   412.9      .1       0
#XS Ineff= 2 , 0
           92.75 3128.18
Permanent Ineff=
       F       F
Bank Sta=375.7,412.9
XS Rating Curve= 0 ,0
Exp/Cntr=0.3,0.1

Type RM Length L Ch R = 1 ,29525   ,249.3,235,221.3
XS GIS Cut Line= 4
 2326418.7265063 602826.09205337  2326369.946617602863.416059581
 2326130.4573115 602908.079712422325994.25971836603053.795266502
#Sta/Elev= 30
       0  3133.3    48.5 3119.12    57.7 3117.43    67.9 3115.79     108 3115.76
   120.2 3114.14   128.3 3111.97     133 3109.69   140.5 3108.98   193.4 3112.14
   217.8 3111.94   234.1 3110.51   250.4 3110.58   254.5 3109.72   274.8 3109.01
   289.2 3109.85   299.2 3112.31   308.4 3113.03   335.7 3112.66   349.4 3110.66
   366.8 3112.35   378.7 3109.82   405.1 3109.59   426.3 3110.42   437.9 3114.75
     449 3116.35   459.9 3119.92   465.9  3120.3   487.2 3130.46   504.5 3136.03
#Mann= 4 ,-1,0
       0     .06       0  111.42      .1       0   254.5    .045       0
   289.2      .1       0
Bank Sta=254.5,289.2
XS Rating Curve= 0 ,0
Exp/Cntr(USF)=0,0
Exp/Cntr=0.3,0.1

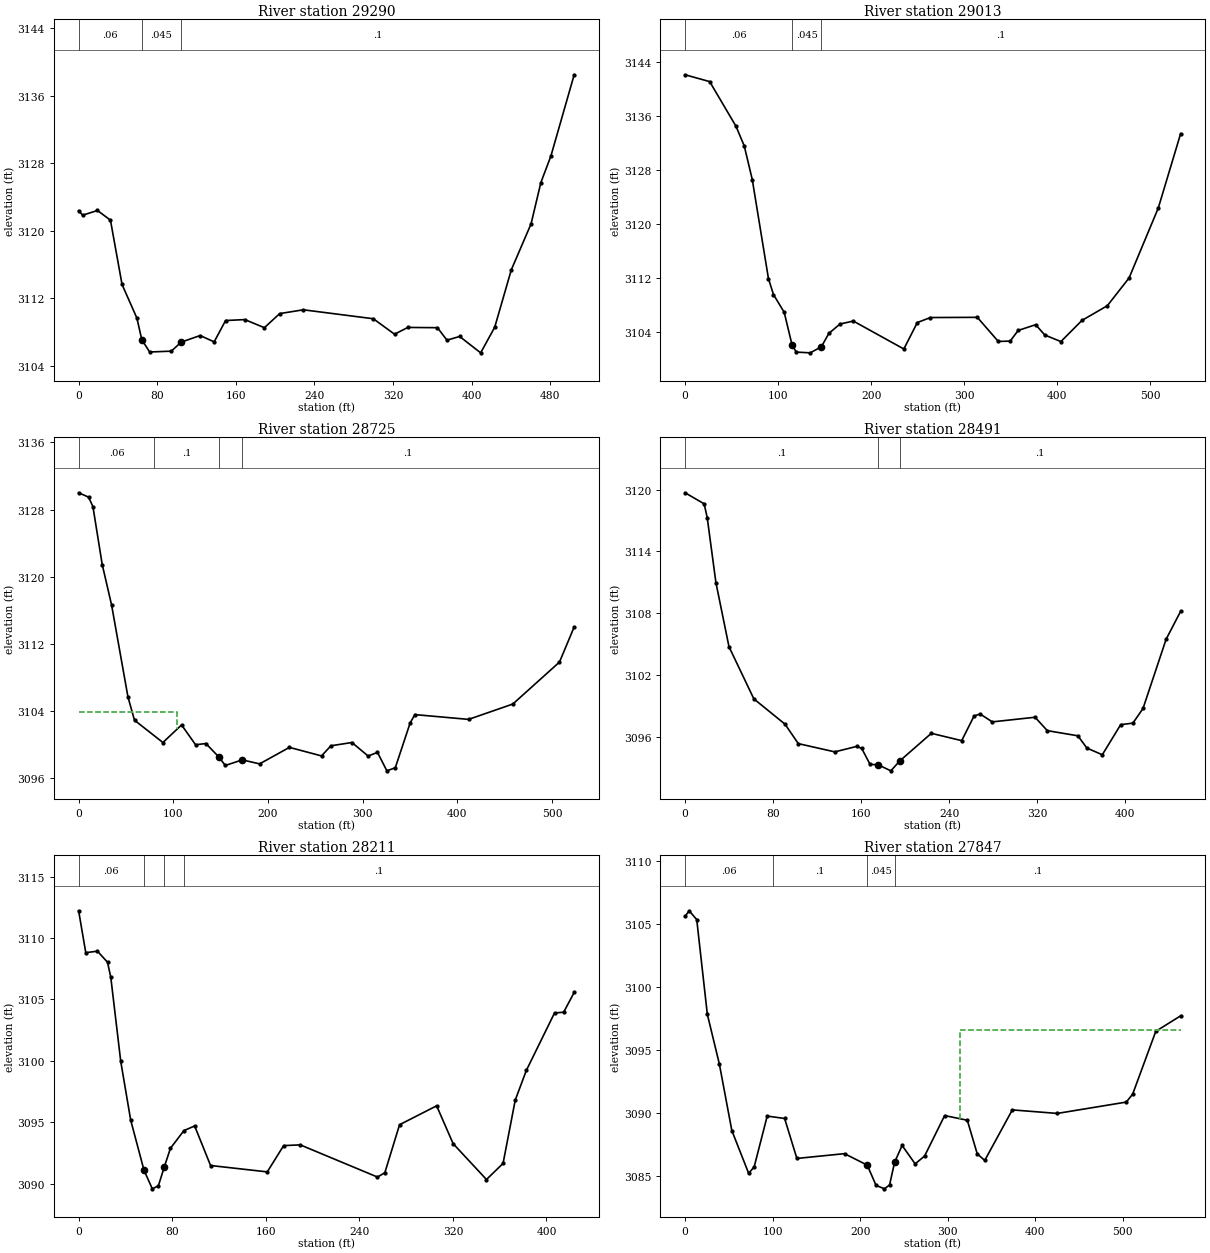
Type RM Length L Ch R = 1 ,29290   ,284.9,276.6,268.5
XS GIS Cut Line= 2
 2326211.4556796 602619.115729662325809.09567084602923.524492282
#Sta/Elev= 30
       0 3122.38     4.1 3121.85    19.2 3122.41    32.4 3121.26    44.2 3113.64
    59.3 3109.66    64.3  3107.1    72.3 3105.64    94.4 3105.74   104.4 3106.81
   123.7 3107.59     138 3106.84   149.6 3109.37   169.2 3109.48   189.1 3108.52
   204.7 3110.19   228.8 3110.64     300 3109.58   321.6 3107.75   335.2 3108.55
   365.3 3108.52     375 3107.04   387.9 3107.48   409.3 3105.54   423.6 3108.57
   440.5 3115.38   460.6 3120.82   470.6 3125.72   480.8 3128.86   504.5 3138.49
#Mann= 3 ,-1,0
       0     .06       0    64.3    .045       0   104.4      .1       0
Bank Sta=64.3,104.4
XS Rating Curve= 0 ,0
Exp/Cntr=0.3,0.1

Type RM Length L Ch R = 1 ,29013   ,288.5,288.1,287.2
XS GIS Cut Line= 2
2326009.31339964602405.3325583132325691.09442479602832.361892303
#Sta/Elev= 30
       0 3142.11    26.4  3141.1    54.7 3134.48    63.6 3131.56    72.2 3126.58
    89.6  3111.9      95 3109.54   106.5 3106.92     115 3102.06   119.5 3101.02
   134.5 3100.91   146.5 3101.81   154.5 3103.79   166.5 3105.18   180.8 3105.62
   235.1 3101.48   249.6  3105.4   263.7 3106.14   314.1 3106.17   336.6  3102.6
   349.4 3102.65     358 3104.23   376.8 3105.08   386.6 3103.55   403.9 3102.58
   426.6 3105.72   453.8 3107.89   477.2 3112.01   508.6 3122.38   532.6 3133.39
#Mann= 3 ,-1,0
       0     .06       0     115    .045       0   146.5      .1       0
Bank Sta=115,146.5
XS Rating Curve= 0 ,0
Exp/Cntr(USF)=0,0
Exp/Cntr=0.3,0.1

Type RM Length L Ch R = 1 ,28725   ,230.2,233.5,237.3
XS GIS Cut Line= 2
2325782.62169979602224.9238047522325477.10268229602649.772533242
#Sta/Elev= 30
       0    3130    10.5 3129.48    15.1 3128.35    24.9 3121.44    34.8 3116.61
    52.1 3105.63      59 3102.86      89  3100.2   108.7  3102.3   123.5 3099.93
   134.4 3100.08   148.1 3098.47   148.1 3098.46   154.9 3097.46   172.8 3098.13
   191.1 3097.65   222.6 3099.62   256.5  3098.6   266.4 3099.81   288.6  3100.2
   305.7 3098.59   315.6 3099.02   325.5 3096.82   334.4 3097.19   350.1 3102.54
   355.1 3103.53   411.8 3102.96   458.5 3104.79   507.8  3109.8   523.3 3113.99
#Mann= 4 ,-1,0
       0     .06       0      80      .1       0   148.1    .045       0
   172.8      .1       0
#XS Ineff= 2 , 0
          104.26  3103.9
Permanent Ineff=
       F       F
Bank Sta=148.1,172.8
XS Rating Curve= 0 ,0
Exp/Cntr=0.3,0.1

Type RM Length L Ch R = 1 ,28491   ,282.3,280.2,278.8
XS GIS Cut Line= 2
2325633.18838483602089.7633826042325308.91298433  602402.3981277
#Sta/Elev= 30
       0 3119.69    17.3 3118.62    20.1 3117.29      28 3110.98    39.9 3104.75
    62.5 3099.69    90.8 3097.24   102.9 3095.35   136.1 3094.55   155.9 3095.08
   160.5 3094.89   168.1 3093.34   175.7 3093.29     187 3092.71   195.1 3093.67
   223.8 3096.35   251.4 3095.64   262.6 3098.02   268.1 3098.23   279.2 3097.46
   318.1 3097.91   329.2 3096.61     357 3096.11   365.2 3094.92   379.2 3094.27
   395.9 3097.19     407 3097.34   416.2 3098.76   437.2 3105.48   450.4 3108.19
#Mann= 3 ,-1,0
       0      .1       0   175.7    .045       0   195.1      .1       0
Bank Sta=175.7,195.1
XS Rating Curve= 0 ,0
Exp/Cntr(USF)=0,0
Exp/Cntr=0.3,0.1

Type RM Length L Ch R = 1 ,28211   ,360.1,364.6,364.9
XS GIS Cut Line= 2
2325434.15591749601912.4634966542325165.55624483602240.087003044
#Sta/Elev= 30
       0 3112.22     6.1 3108.81    16.1 3108.93    24.7 3108.03    27.5  3106.8
      36 3099.96    44.5 3095.18    55.9 3091.09      63 3089.58    68.2 3089.83
    73.3 3091.38    78.5 3092.88      90 3094.32    99.2  3094.7   112.8 3091.48
   161.3 3090.96   175.3  3093.1   189.5 3093.16   255.5 3090.54   261.8 3090.89
   274.4  3094.8   306.1 3096.34   320.2 3093.26   348.7 3090.34   362.9 3091.65
   373.3  3096.8   382.8 3099.22   406.9  3103.9   414.7 3103.96   423.7 3105.57
#Mann= 4 ,-1,0
       0     .06       0    55.9    .045       0    73.3     .06       0
      90      .1       0
Bank Sta=55.9,73.3
XS Rating Curve= 0 ,0
Exp/Cntr=0.3,0.1

Type RM Length L Ch R = 1 ,27847   ,299.4,293.8,286.3
XS GIS Cut Line= 2
2325179.27383213 601705.651521142324843.35777623602161.300032609
#Sta/Elev= 30
       0 3105.61     4.7 3106.05    13.3 3105.35    25.4 3097.84    39.1 3093.91
    53.4 3088.62    72.6 3085.23    78.9 3085.74    93.8 3089.77   113.7 3089.58
   127.7 3086.41   182.1 3086.79   208.1 3085.88   218.1 3084.28   227.7    3084
   233.6 3084.31   239.3  3086.1   247.9 3087.44   262.8 3085.98   273.6  3086.6
   296.5 3089.81   322.4 3089.44   333.7 3086.78   342.3 3086.25   373.8 3090.26
   425.2 3089.98     504 3090.88   511.3 3091.51   537.7 3096.49   566.1 3097.72
#Mann= 4 ,-1,0
       0     .06       0     100      .1       0   208.1    .045       0
   239.3      .1       0
#XS Ineff= 2 , 0
                          313.62          3096.6
Permanent Ineff=
       F       F
Bank Sta=208.1,239.3
XS Rating Curve= 0 ,0
Exp/Cntr(USF)=0,0
Exp/Cntr=0.3,0.1