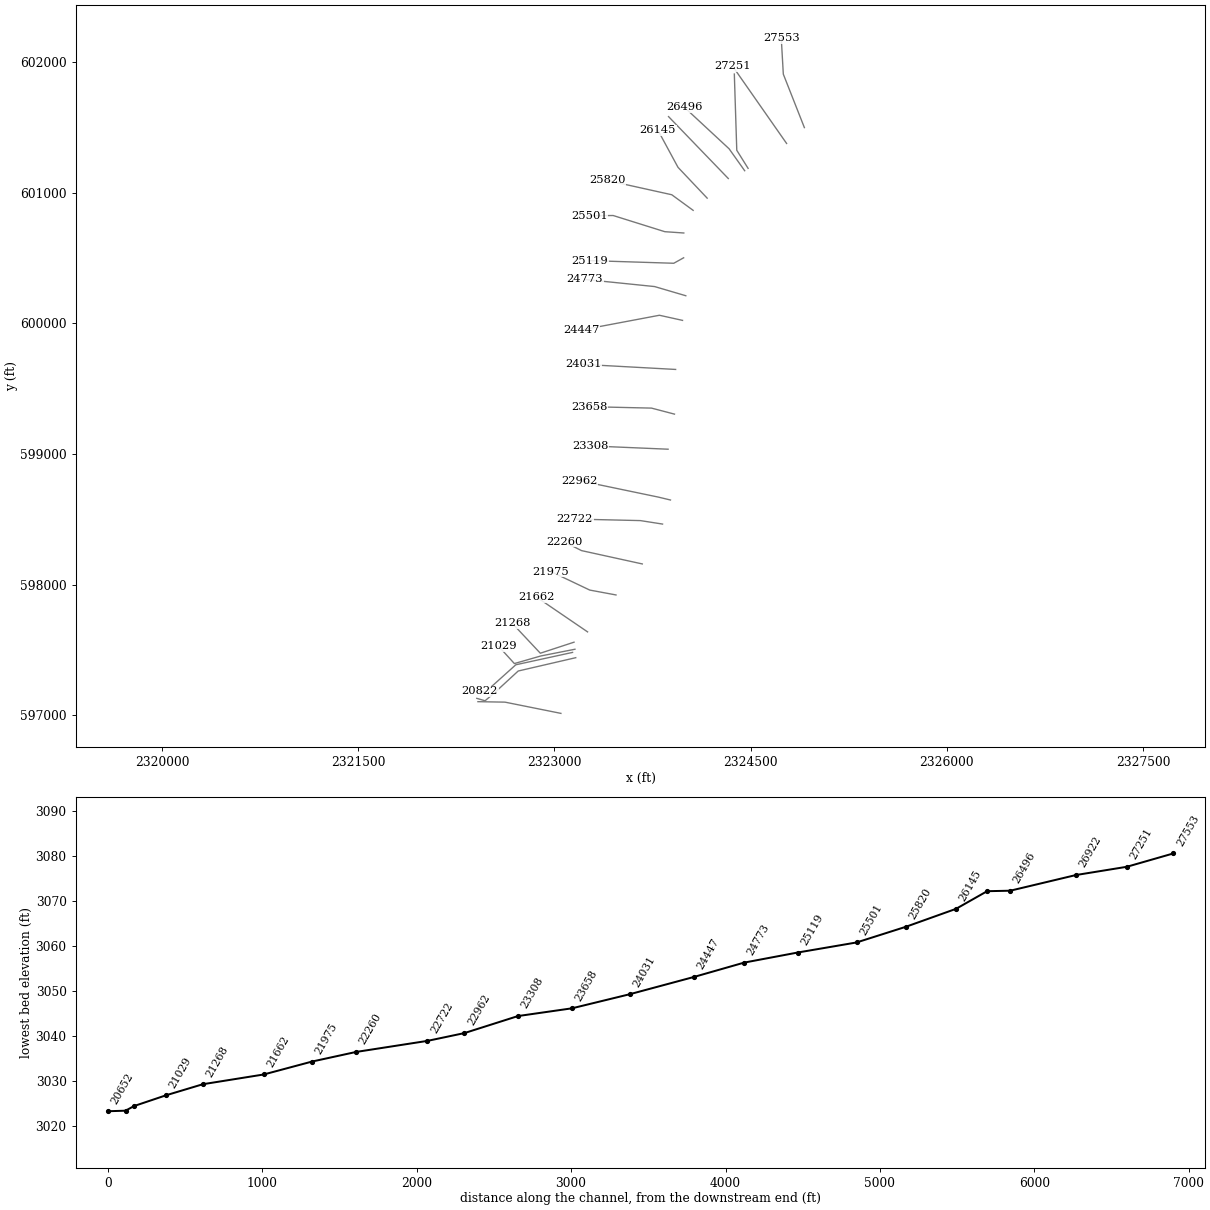
HEC-RAS study LTTLRV1.prj: LTTLRV1

--- LTTLRV1.g01 (geometry) --- (continued)

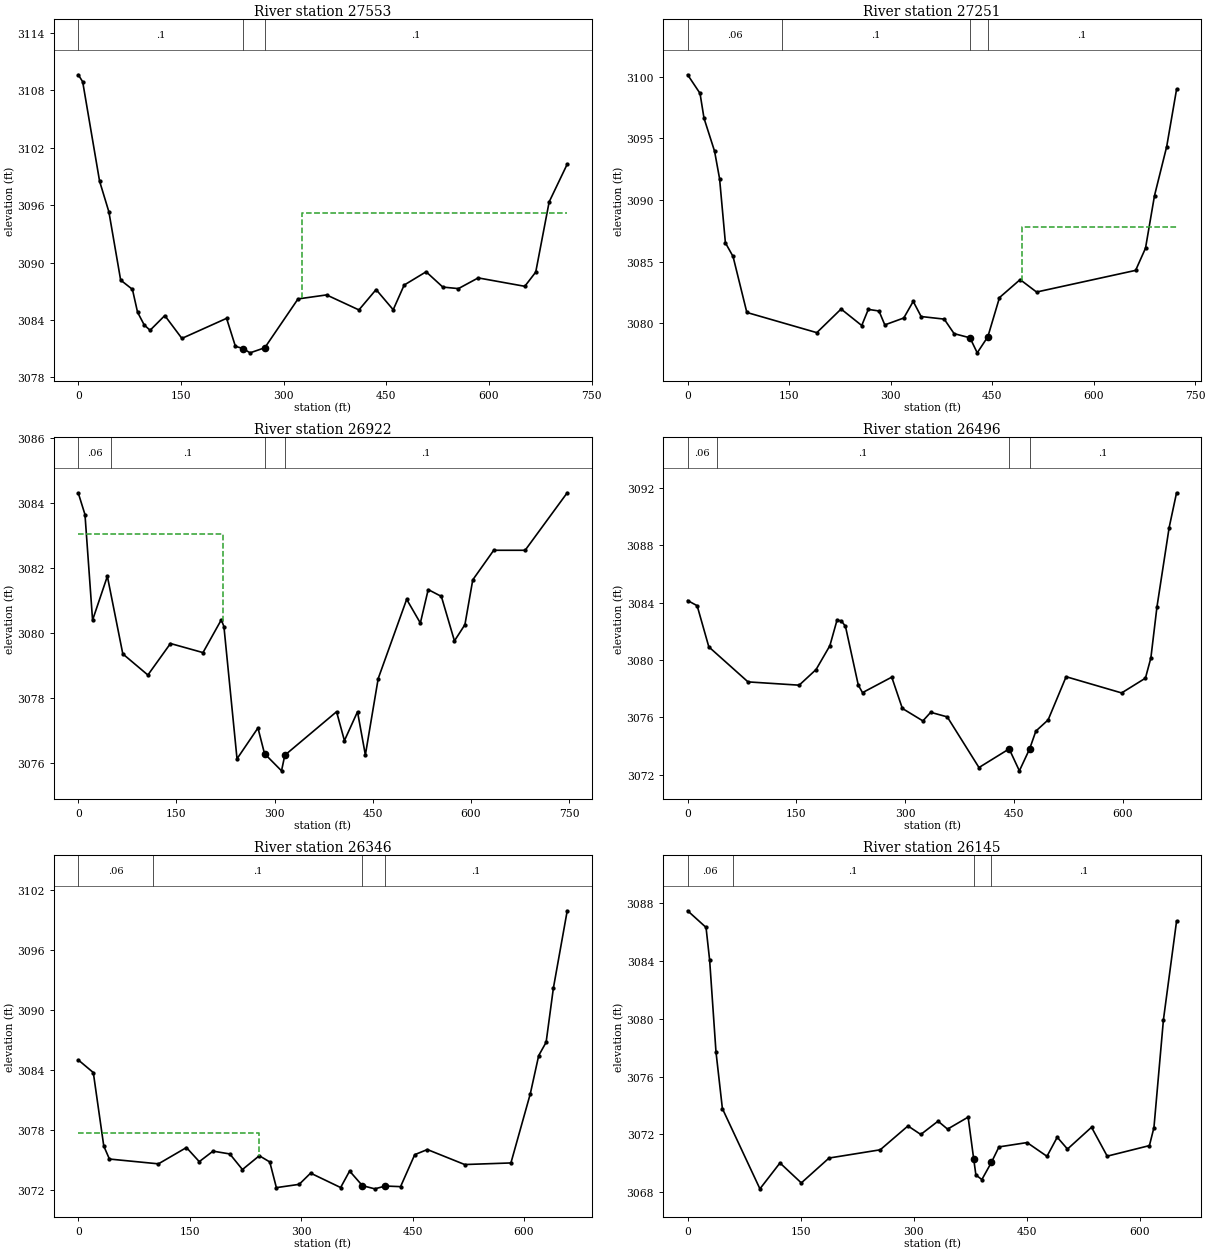
Type RM Length L Ch R = 1 ,27553   ,295.2,301.8,303.7
XS GIS Cut Line= 3
2324910.89476871601499.5688719022324749.86320478601908.833564295
2324734.27910258602183.039640981
#Sta/Elev= 30
       0 3109.64     6.4 3108.91    31.1 3098.51    44.7  3095.3    61.9 3088.16
    79.1 3087.19    86.6  3084.8    96.3 3083.47   104.9 3082.91   126.4 3084.45
   151.4 3082.06   216.7 3084.16   229.6 3081.23   240.9    3081     251 3080.55
   272.5 3081.08   321.1 3086.19   362.8 3086.61   410.1 3085.04   435.2 3087.17
   460.2 3085.06   476.2 3087.64   508.3 3089.03   532.7 3087.43   555.5 3087.27
   584.4 3088.39   652.5 3087.51   668.5    3089   688.1 3096.34   714.5 3100.29
#Mann= 3 ,-1,0
       0      .1       0   240.9    .045       0   272.5      .1       0
#XS Ineff= 2 , 0
                          326.96         3095.22
Permanent Ineff=
       F       F
Bank Sta=240.9,272.5
XS Rating Curve= 0 ,0
Exp/Cntr=0.3,0.1

Type RM Length L Ch R = 1 ,27251   ,345.5,329.2,313.6
XS GIS Cut Line= 2
2324774.91667624601378.1627249032324361.54037339601970.838379968
#Sta/Elev= 30
       0 3100.17    18.3 3098.66    24.2 3096.64    39.8 3093.96    47.2 3091.73
    55.8 3086.52    67.1 3085.41    87.5 3080.86   190.9 3079.22   226.8 3081.14
   257.3  3079.8     267 3081.11   282.8 3080.98   291.4 3079.85   319.4 3080.41
   333.4 3081.76   345.1 3080.53   379.2 3080.32   393.8 3079.14   417.3  3078.8
     428 3077.58   443.7 3078.89   460.9 3082.07   491.4 3083.53   515.7 3082.52
   662.1 3084.28   676.7 3086.08     690 3090.35     708 3094.33   722.6 3098.98
#Mann= 4 ,-1,0
       0     .06       0     140      .1       0   417.3    .045       0
   443.7      .1       0
#XS Ineff= 2 , 0
                          494.69          3087.8
Permanent Ineff=
       F       F
Bank Sta=417.3,443.7
XS Rating Curve= 0 ,0
Exp/Cntr(USF)=0,0
Exp/Cntr=0.3,0.1

Type RM Length L Ch R = 1 ,26922   ,392.7,425.8,432.9
XS GIS Cut Line= 3
2324480.51989525601187.5187897752324394.06232669 601325.85089947
 2324375.3298535601909.439487246
#Sta/Elev= 30
       0  3084.3    10.2 3083.64    21.8 3080.39    44.4 3081.74      68 3079.35
   106.3  3078.7   140.8 3079.67   190.5 3079.39   218.5  3080.4   222.5 3080.19
   242.5 3076.12   274.5 3077.07   284.5 3076.28   310.5 3075.75   315.5 3076.23
   394.6 3077.57   406.6 3076.68   426.6 3077.57   438.6 3076.24   458.2 3078.59
   501.7 3081.03   522.6  3080.3   534.6 3081.33   554.7 3081.12   574.7 3079.75
   590.7 3080.25   602.7 3081.63   634.7 3082.54   682.7 3082.54     747 3084.31
#Mann= 4 ,-1,0
       0     .06       0      50      .1       0   284.5    .045       0
   315.5      .1       0
#XS Ineff= 2 , 0
          220.33 3083.03
Permanent Ineff=
       F       F
Bank Sta=284.5,315.5
XS Rating Curve= 0 ,0
Exp/Cntr(USF)=0,0
Exp/Cntr=0.3,0.1

Type RM Length L Ch R = 1 ,26496   ,150.7,149.6,148
XS GIS Cut Line= 3
2324454.55292319601169.3217848232324335.63604087601337.044536549
2323992.76977102601655.807157444
#Sta/Elev= 30
       0 3084.14    13.1 3083.78    29.2 3080.91    83.2 3078.47   153.7 3078.24
     177 3079.33     196 3080.99   205.8 3082.76   211.7 3082.73   217.5 3082.34
   235.2 3078.24     241 3077.72   281.3  3078.8   295.9 3076.62   324.2 3075.75
     335 3076.35   357.8 3076.03   401.5  3072.5   443.1  3073.8   457.2 3072.27
   471.4 3073.81   479.9 3075.04   496.8 3075.82   521.6 3078.83   598.1  3077.7
   630.9 3078.73   638.4 3080.14   646.8  3083.7   663.6 3089.23   673.8 3091.65
#Mann= 4 ,-1,0
       0     .06       0      40      .1       0   443.1    .045       0
   471.4      .1       0
Bank Sta=443.1,471.4
XS Rating Curve= 0 ,0
Exp/Cntr=0.3,0.1

Type RM Length L Ch R = 1 ,26346   ,206.8,201.7,195.3
XS GIS Cut Line= 2
2324329.21915027601109.7069780712323872.43499638601583.782645672
#Sta/Elev= 30
       0 3085.05    20.2 3083.79    34.3 3076.44    41.9 3075.14   107.9 3074.66
   145.6 3076.29   162.9 3074.88   181.4 3075.93     204 3075.65     221 3074.09
   243.7 3075.47   257.8 3074.85   266.7 3072.28   297.4 3072.61   312.8 3073.73
   353.2 3072.29   365.3 3073.94   382.5 3072.48   399.2 3072.16   413.4 3072.44
   433.9 3072.38     453 3075.58     470 3076.09   520.3 3074.59   582.5 3074.75
   608.6 3081.67   619.9 3085.49   629.9 3086.82   639.7 3092.25   658.3 3099.97
#Mann= 4 ,-1,0
       0     .06       0     100      .1       0   382.5    .045       0
   413.4      .1       0
#XS Ineff= 2 , 0
          243.28 3077.78
Permanent Ineff=
       F       F
Bank Sta=382.5,413.4
XS Rating Curve= 0 ,0
Exp/Cntr(USF)=0,0
Exp/Cntr=0.3,0.1

Type RM Length L Ch R = 1 ,26145   ,304,324.5,342.4
XS GIS Cut Line= 3
2324167.68409448600959.471761365 2323944.7524296601195.383546594
2323790.71155563 601480.50103422
#Sta/Elev= 30
       0 3087.47    24.4 3086.32    29.2 3084.05    37.6 3077.71    46.1 3073.79
    95.9 3068.24   122.5 3070.03   150.8 3068.65   187.6 3070.37   255.5 3070.94
   292.3 3072.59   309.3    3072   332.2 3072.92   344.8 3072.37   372.1  3073.2
   379.5  3070.3   382.4  3069.2   390.3 3068.88   403.1 3070.08     413 3071.14
   450.3 3071.44   476.7 3070.49   490.3 3071.81   503.9 3070.99   535.8  3072.5
   556.6  3070.5   612.6 3071.23   618.6 3072.48   631.2 3079.94   648.6 3086.75
#Mann= 4 ,-1,0
       0     .06       0      60      .1       0   379.5    .045       0
   403.1      .1       0
Bank Sta=379.5,403.1
XS Rating Curve= 0 ,0
Exp/Cntr=0.3,0.1

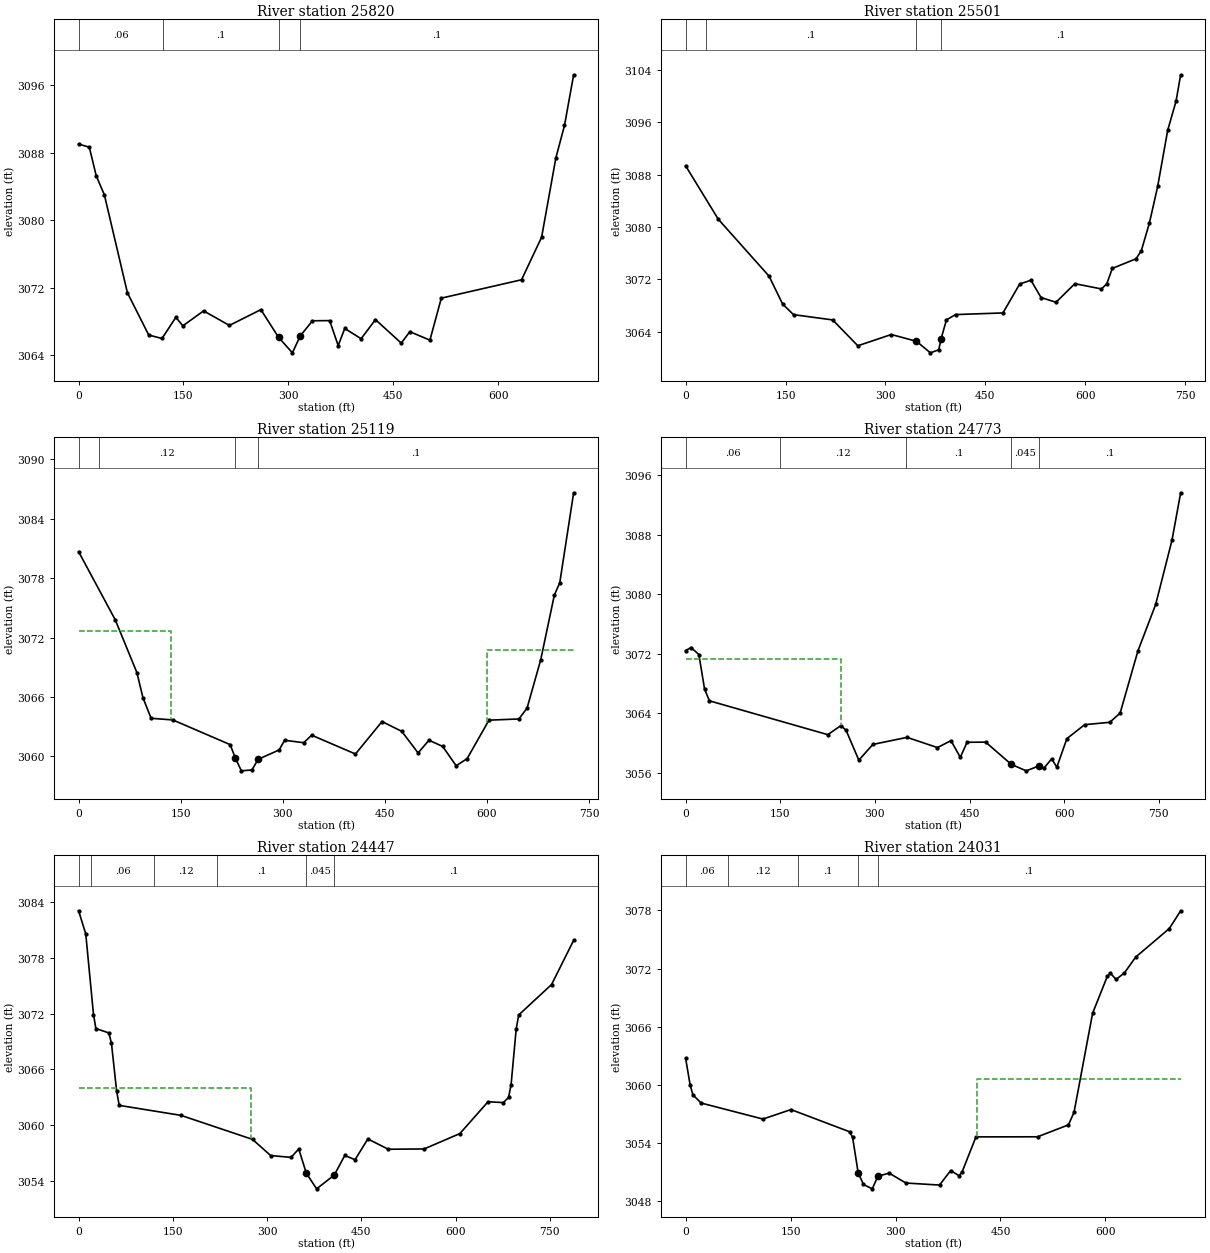
Type RM Length L Ch R = 1 ,25820   ,315.8,319.3,316.2
XS GIS Cut Line= 3
2324060.51549071600865.9801859112323897.05993159600985.441885912
2323403.45104402601094.933364041
#Sta/Elev= 30
       0    3089    15.3 3088.63    25.2 3085.24    36.9 3082.97    69.8 3071.38
   100.3 3066.37   119.3 3065.96   139.1 3068.47   149.1 3067.46   178.8 3069.23
   215.7 3067.51   260.7 3069.38   286.1 3066.09   305.8 3064.26     317 3066.26
   334.5 3068.06   359.1 3068.08   371.3 3065.12   380.7 3067.15   404.1 3065.93
   424.6  3068.2   461.5 3065.41   473.8 3066.77   502.5 3065.76   518.8 3070.74
   633.6 3072.92   662.3 3077.97   682.7 3087.37     695  3091.2   708.1 3097.21
#Mann= 4 ,-1,0
       0     .06       0     120      .1       0   286.1    .045       0
     317      .1       0
Bank Sta=286.1,317
XS Rating Curve= 0 ,0
Exp/Cntr=0.3,0.1

Type RM Length L Ch R = 1 ,25501   ,372.9,382,387.5
XS GIS Cut Line= 4
2323989.11710164600692.565079122   2323843.85617600702.578152139
2323448.80692265600826.4651350072323265.27236935600824.404538405
#Sta/Elev= 30
       0 3089.37    49.1  3081.2   125.3  3072.5   145.6 3068.24     162 3066.62
   220.8 3065.81   258.5 3061.86   308.8 3063.58   346.5 3062.55   367.5 3060.78
     380 3061.25   383.6 3062.95   391.5 3065.81   405.2 3066.63   476.4 3066.88
   501.6 3071.31   518.4 3071.88   533.6 3069.23   556.1 3068.51   584.3 3071.35
   624.3 3070.55   632.3 3071.33   640.6 3073.69   676.3 3075.16   684.2 3076.41
   696.3 3080.64   708.7 3086.23   723.7 3094.79   736.3 3099.27   743.2 3103.29
#Mann= 4 ,-1,0
       0     .06       0      30      .1       0   346.5    .045       0
   383.6      .1       0
Bank Sta=346.5,383.6
XS Rating Curve= 0 ,0
Exp/Cntr=0.3,0.1

Type RM Length L Ch R = 1 ,25119   ,325.3,345.4,341
XS GIS Cut Line= 3
2323987.82496284600502.7348292722323912.39351583600460.828469823
2323271.84766713600481.101687455
#Sta/Elev= 30
       0 3080.68    53.8  3073.8    85.6 3068.47    94.5 3065.93   106.5 3063.85
   138.5 3063.68   222.6 3061.19   230.4 3059.81   239.1 3058.54   254.6 3058.63
   263.73059.704   294.6 3060.65   302.6 3061.63   330.6 3061.38   342.4 3062.14
   406.7 3060.24   445.7 3063.52   474.7 3062.53   498.7 3060.35   514.7 3061.63
   534.7 3061.01   554.7 3059.05   570.8 3059.78   602.8 3063.66   646.8 3063.78
   658.8 3064.88   678.8 3069.75   698.8 3076.28   706.8 3077.54   727.2 3086.63
#Mann= 4 ,-1,0
       0     .06       0      30     .12       0   230.4    .045       0
   263.7      .1       0
#XS Ineff= 2 , 0
          136.04 3072.67  600.58         3070.72
Permanent Ineff=
       F       F
Bank Sta=230.4,263.7
XS Rating Curve= 0 ,0
Exp/Cntr(USF)=0,0
Exp/Cntr=0.3,0.1

Type RM Length L Ch R = 1 ,24773   ,313.7,326.7,328
XS GIS Cut Line= 3
2324004.36613837600212.1490308712323765.82924748600282.417509843
2323232.73460109 600336.94844023
#Sta/Elev= 30
       0 3072.44     8.5 3072.85      21 3071.91      30 3067.28    37.7  3065.7
   225.4 3061.16   246.2 3062.39   254.4 3061.72   274.5 3057.74   296.7 3059.85
   350.9  3060.8   399.1 3059.43   420.5 3060.36   435.3 3058.12     446 3060.14
   475.5 3060.16   516.2 3057.17   539.8 3056.31   559.9 3056.97     568 3056.69
     580 3057.91   588.3 3056.81   604.2 3060.63   632.3  3062.5   672.2 3062.82
   688.6 3064.06   716.8  3072.4   744.9 3078.62   770.7 3087.22   784.5  3093.6
#Mann= 5 ,-1,0
       0     .06       0     150     .12       0  348.67      .1       0
   516.2    .045       0   559.9      .1       0
#XS Ineff= 2 , 0
           245.8 3071.31
Permanent Ineff=
       F       F
Bank Sta=516.2,559.9
XS Rating Curve= 0 ,0
Exp/Cntr=0.3,0.1

Type RM Length L Ch R = 1 ,24447   ,417.8,415.5,406.3
XS GIS Cut Line= 3
2323979.27441218600023.4865907392323802.72699416600062.688409261
2323206.35045688599949.990059249
#Sta/Elev= 30
       0 3083.09    11.4 3080.59    23.7  3071.9    27.5 3070.39    48.2 3069.92
    52.3 3068.79    60.5 3063.65    64.6 3062.11     163 3061.03   276.8 3058.44
   305.6  3056.7   338.1  3056.5   350.3 3057.41   362.4 3054.79   378.8 3053.11
   406.9  3054.6   423.6 3056.71   439.9 3056.25   460.3 3058.49   492.8 3057.38
   549.8 3057.41   606.8 3059.07   651.6  3062.5     676 3062.41   684.2 3062.97
   688.2 3064.32   696.4 3070.36   700.4 3071.86   752.7 3075.14   787.8  3079.9
#Mann= 6 ,-1,0
       0      .1       0      20     .06       0     120     .12       0
  220.85      .1       0   362.4    .045       0   406.9      .1       0
#XS Ineff= 2 , 0
           274.4 3064.02
Permanent Ineff=
       F       F
Bank Sta=362.4,406.9
XS Rating Curve= 0 ,0
Exp/Cntr=0.3,0.1

Type RM Length L Ch R = 1 ,24031   ,369.6,372.9,379.6
XS GIS Cut Line= 2
2323926.55591665599647.8340202872323219.99996011599686.565051085
#Sta/Elev= 30
       0 3062.75     6.4 3060.02    10.4 3058.98    22.3 3058.13   110.5 3056.48
   150.6 3057.46   234.7 3055.16   238.7 3054.58   246.6 3050.95   254.2 3049.73
   266.8 3049.28   274.8 3050.58   290.8  3050.9   314.9 3049.88   362.9 3049.67
   378.9 3051.17   390.9 3050.63     395 3050.99     415 3054.64   503.1 3054.65
   547.2 3055.88   555.2 3057.18   581.7 3067.39   602.9 3071.23   607.3 3071.52
   615.3 3070.88   627.3 3071.57   643.3 3073.19   691.4 3076.14   707.6 3077.97
#Mann= 5 ,-1,0
       0     .06       0      60     .12       0     160      .1       0
   246.6    .045       0   274.8      .1       0
#XS Ineff= 2 , 0
                          416.62         3060.63
Permanent Ineff=
       F       F
Bank Sta=246.6,274.8
XS Rating Curve= 0 ,0
Exp/Cntr=0.3,0.1

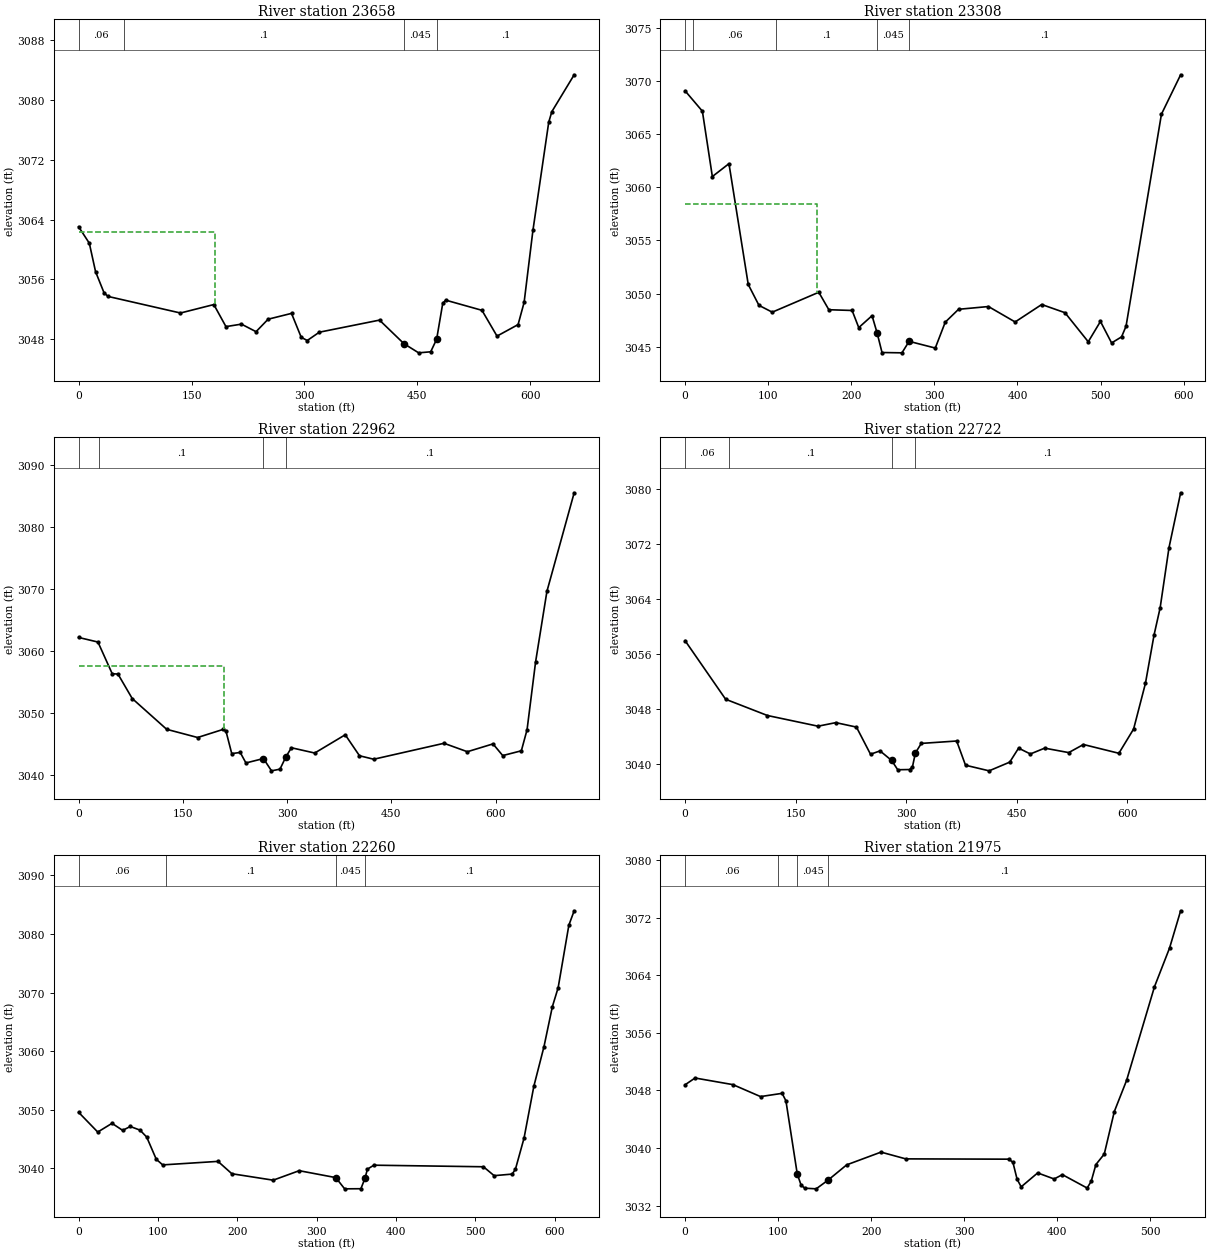
Type RM Length L Ch R = 1 ,23658   ,351.1,349.9,353.4
XS GIS Cut Line= 3
2323917.90129091 599305.723442122323742.11907958  599351.7905044
2323265.68867232599362.701124414
#Sta/Elev= 30
       0 3063.03    14.2 3060.83    22.5 3057.02    33.7 3054.21      39 3053.71
   135.3 3051.49   179.6 3052.62   195.7 3049.67   216.3    3050   235.7 3048.99
   251.7 3050.66   282.8 3051.44   295.7 3048.24   303.7 3047.81   319.7 3048.92
   399.7 3050.54   432.1 3047.39   451.7 3046.16   467.7  3046.3   475.63047.982
   483.7 3052.78   487.7 3053.21   535.8 3051.85   555.8  3048.4   583.8 3049.94
   591.8 3052.91   603.5 3062.54   624.5 3077.02   628.6 3078.43   658.3 3083.37
#Mann= 4 ,-1,0
       0     .06       0      60      .1       0   432.1    .045       0
   475.6      .1       0
#XS Ineff= 2 , 0
          180.58 3062.28
Permanent Ineff=
       F       F
Bank Sta=432.1,475.6
XS Rating Curve= 0 ,0
Exp/Cntr(USF)=0,0
Exp/Cntr=0.3,0.1

Type RM Length L Ch R = 1 ,23308   ,348.5,346.6,340.5
XS GIS Cut Line= 2
2323868.96772591599037.0744826892323273.11495954599062.618987486
#Sta/Elev= 30
       0 3069.05    20.8 3067.14    32.8    3061    52.8 3062.21      76 3050.86
    88.9  3048.9   104.9 3048.26   160.9 3050.13     173 3048.49     201 3048.42
     209 3046.81     225 3047.93   231.2 3046.28     237 3044.47     261 3044.44
   269.6 3045.52   301.1 3044.89   313.1 3047.32   329.1 3048.53   365.1 3048.79
   397.2 3047.34   429.2 3048.98   457.2 3048.21   485.2 3045.48   499.9 3047.39
   513.3 3045.37   525.3 3045.94   530.7 3046.94   573.3 3066.86   596.4 3070.56
#Mann= 5 ,-1,0
       0      .1       0      10     .06       0     110      .1       0
   231.2    .045       0   269.6      .1       0
#XS Ineff= 2 , 0
          158.84 3058.43
Permanent Ineff=
       F       F
Bank Sta=231.2,269.6
XS Rating Curve= 0 ,0
Exp/Cntr=0.3,0.1

Type RM Length L Ch R = 1 ,22962   ,232.4,239.4,241.7
XS GIS Cut Line= 3
2323887.17321819598648.1421138922323793.36878181598670.598181477
2323189.83726158598796.454295369
#Sta/Elev= 30
       0 3062.15    27.8 3061.41    48.3 3056.31    56.6 3056.25    77.1 3052.31
   126.7 3047.35   171.2 3046.03     208 3047.34   212.1 3047.01   220.3 3043.44
   232.5 3043.62   240.7 3041.93   265.9 3042.64   277.5 3040.66   289.7 3040.93
   297.9 3042.84   306.1 3044.38   339.7 3043.53   383.6 3046.47   404.1 3043.09
   424.6 3042.53   525.7  3045.1   559.3 3043.74   596.2    3045   610.2 3043.12
     637 3043.89   645.2 3047.28   657.5 3058.22   673.8 3069.58     713 3085.46
#Mann= 4 ,-1,0
       0     .06       0      30      .1       0   265.9    .045       0
   297.9      .1       0
#XS Ineff= 2 , 0
           208.7 3057.48
Permanent Ineff=
       F       F
Bank Sta=265.9,297.9
XS Rating Curve= 0 ,0
Exp/Cntr=0.3,0.1

Type RM Length L Ch R = 1 ,22722   ,459.9,462.5,454.1
XS GIS Cut Line= 3
2323826.54794894598463.8899101432323656.92697022598490.497122492
2323156.37878791598502.137777894
#Sta/Elev= 30
       0 3057.91      55 3049.37   111.7    3047   180.4 3045.44   204.5 3045.96
   232.5 3045.31   251.6 3041.35   264.5 3041.84   280.3 3040.44   288.5 3039.09
   304.5 3039.12   308.5 3039.51   312.5 3041.54   320.5 3042.93   368.5 3043.28
   380.5 3039.75   412.5 3038.93   440.5  3040.2   452.5 3042.24   468.5 3041.39
   487.9 3042.24   520.5 3041.59   540.5 3042.77   588.6 3041.49   608.6 3045.03
   624.6 3051.67   636.4 3058.78   644.6 3062.71   656.6 3071.48   672.4 3079.48
#Mann= 4 ,-1,0
       0     .06       0      60      .1       0   280.3    .045       0
   312.5      .1       0
Bank Sta=280.3,312.5
XS Rating Curve= 0 ,0
Exp/Cntr(USF)=0,0
Exp/Cntr=0.3,0.1

Type RM Length L Ch R = 1 ,22260   ,285.2,284.8,287.9
XS GIS Cut Line= 3
 2323671.7484921598158.584584896 2323207.1455996598260.666492282
2323074.22894507598328.145598348
#Sta/Elev= 30
       0 3049.54    24.1 3046.17    42.1 3047.66    55.5 3046.46    65.1 3047.12
    77.4  3046.5    85.8 3045.32    97.9 3041.52     106 3040.56   175.7 3041.16
   193.2 3039.05   245.3 3037.95   278.1 3039.57   324.2 3038.39   335.4 3036.47
   355.9 3036.49   361.1 3038.29   364.1 3039.83   372.2 3040.51   510.4 3040.24
   523.9 3038.72   546.7 3038.99   550.8 3039.85   561.6 3045.14     574 3054.02
   586.7 3060.74   597.3 3067.59   604.6 3070.83   618.1 3081.51   624.8 3083.97
#Mann= 4 ,-1,0
       0     .06       0     110      .1       0   324.2    .045       0
   361.1      .1       0
Bank Sta=324.2,361.1
XS Rating Curve= 0 ,0
Exp/Cntr=0.3,0.1

Type RM Length L Ch R = 1 ,21975   ,328.4,312.9,307.8
XS GIS Cut Line= 3
2323470.72576233597921.1427188982323269.99009484597958.533359746
2322973.45524293598099.849536752
#Sta/Elev= 30
       0 3048.79    10.7 3049.73    51.4 3048.81    81.1 3047.15   104.3  3047.6
   108.4 3046.56   120.6 3036.38   124.7 3034.86   128.7 3034.43   140.9 3034.34
   153.7 3035.55   173.7 3037.67   210.6 3039.44   237.2  3038.5     348 3038.46
   352.4 3038.02   356.9 3035.67   361.3 3034.62     379 3036.55   396.7 3035.71
   405.6 3036.31   432.2 3034.45   436.6  3035.4   441.6 3037.71   450.6 3039.17
   461.4 3045.07   474.6  3049.4   504.6 3062.41   520.8 3067.78   532.7 3072.95
#Mann= 4 ,-1,0
       0     .06       0     100      .1       0   120.6    .045       0
   153.7      .1       0
Bank Sta=120.6,153.7
XS Rating Curve= 0 ,0
Exp/Cntr=0.3,0.1

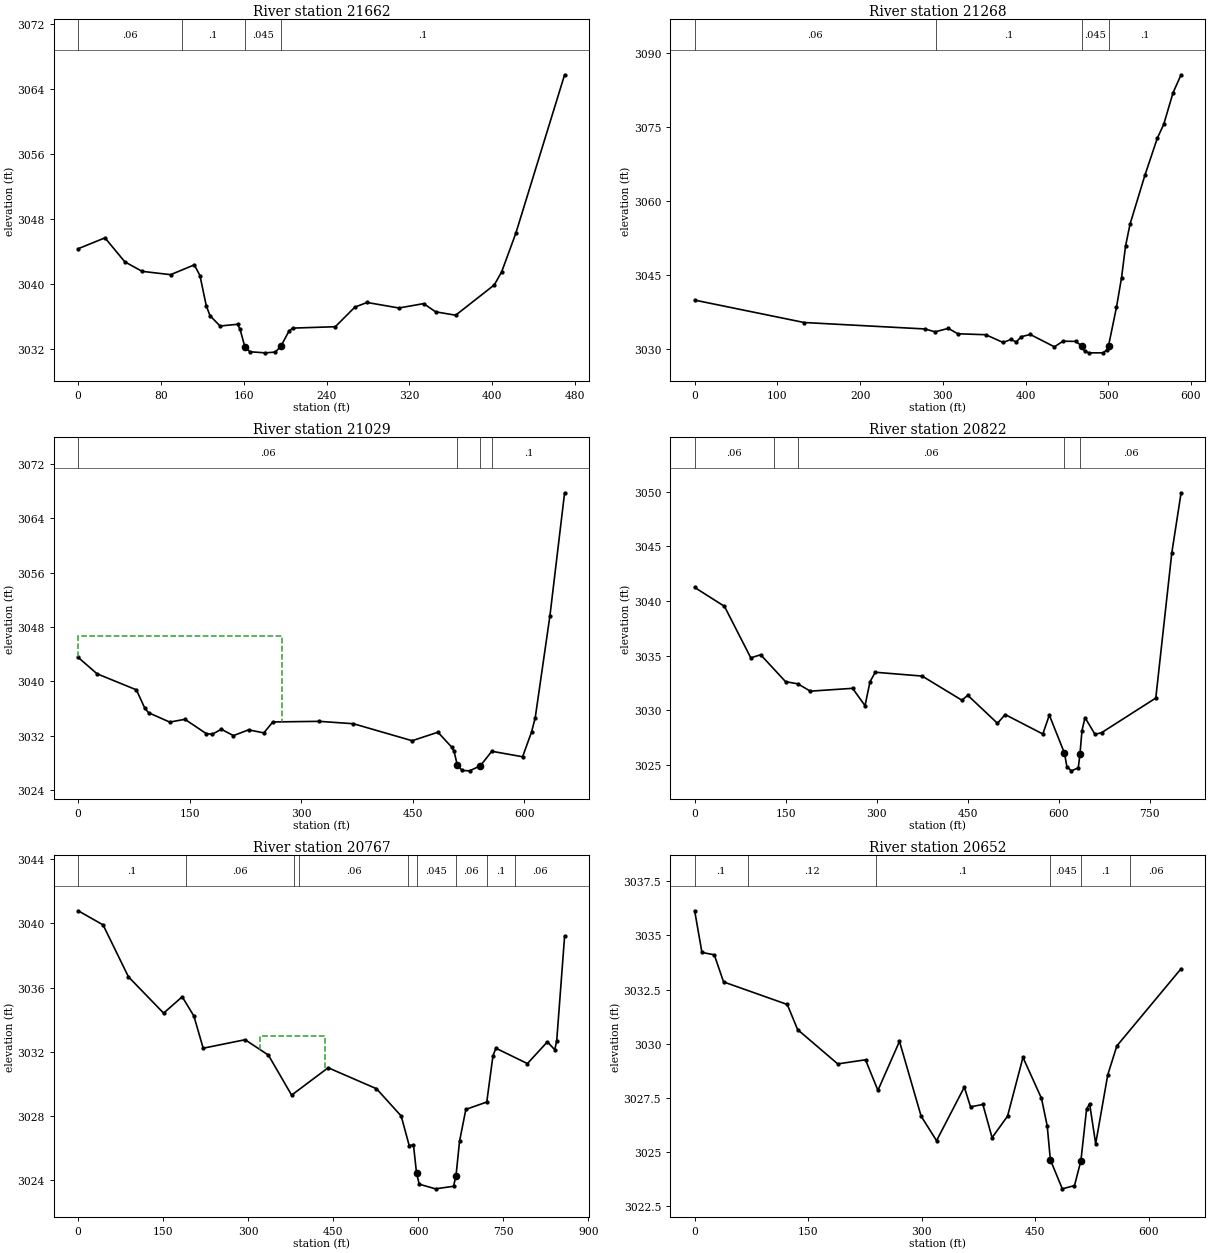
Type RM Length L Ch R = 1 ,21662   ,402.7,393.8,389.9
XS GIS Cut Line= 2
2323253.40044423597638.3482564442322865.16273261597903.484800027
#Sta/Elev= 30
       0 3044.31    25.9 3045.65    45.1 3042.69    61.8 3041.52    89.3 3041.11
   112.3 3042.32   117.7 3040.99   123.8 3037.27   127.4 3036.05   137.1 3034.78
     154 3034.99   156.5 3034.36   161.2 3032.14   166.2  3031.6   180.7 3031.47
   190.4 3031.56   195.8 3032.26   203.6 3034.12   207.3 3034.52   248.5 3034.69
   267.4 3037.11   279.2 3037.68     310    3037   333.9 3037.54   345.4 3036.53
   364.8 3036.11   402.2 3039.85   409.3 3041.47   422.9 3046.19   470.1 3065.76
#Mann= 4 ,-1,0
       0     .06       0     100      .1       0   161.2    .045       0
   195.8      .1       0
Bank Sta=161.2,195.8
XS Rating Curve= 0 ,0
Exp/Cntr(USF)=0,0
Exp/Cntr=0.3,0.1

Type RM Length L Ch R = 1 ,21268   ,237.4,238.9,236.5
XS GIS Cut Line= 3
2323149.90320637597559.5364321822322892.10771335597475.047794802
2322675.43683485597706.159957527
#Sta/Elev= 30
       0    3040   132.3 3035.46   278.4 3034.15   290.7 3033.57   306.7 3034.27
   318.1 3033.18     352 3032.98   372.9 3031.41   382.3 3032.02   388.8 3031.51
   394.8 3032.58   405.8 3033.03   434.9 3030.53   445.4 3031.67   460.6 3031.63
     468 3030.72   471.6 3029.61   477.1 3029.31   493.5 3029.31     499 3029.97
   500.4 3030.76     510 3038.58   516.1 3044.54   520.9 3050.93   526.4 3055.42
   544.4 3065.34   559.3  3072.8   567.1 3075.63   578.4 3082.06   588.1 3085.68
#Mann= 4 ,-1,0
       0     .06       0  291.29      .1       0     468    .045       0
   500.4      .1       0
Bank Sta=468,500.4
XS Rating Curve= 0 ,0
Exp/Cntr=0.3,0.1

Type RM Length L Ch R = 1 ,21029   ,169.7,207,240.7
XS GIS Cut Line= 4
2323156.96375855597505.5012904922322896.72175095597454.206846129
2322693.75754409597395.8027341782322574.23287937  597527.1237447
#Sta/Elev= 30
       0 3043.54    25.3 3041.13    78.3 3038.76    89.5 3036.08    94.6  3035.4
   123.1 3034.02   143.5 3034.43     172 3032.34   180.2 3032.22   192.4 3032.97
   208.7 3032.03   229.1 3032.88   249.6 3032.43   261.7 3034.04   324.1 3034.13
     370 3033.78     449 3031.28   483.7 3032.53   502.6 3030.29   505.4 3029.71
   509.7 3027.72   516.2  3026.9   526.3 3026.85   540.8  3027.6   556.1 3029.73
   597.5 3028.92   609.5 3032.54   614.5 3034.66   634.3 3049.68     654 3067.75
#Mann= 4 ,-1,0
       0     .06       0   509.7    .045       0   540.8     .06       0
  556.45      .1       0
#XS Ineff= 2 , 0
          274.59  3046.7
Permanent Ineff=
       F       F
Bank Sta=509.7,540.8
XS Rating Curve= 0 ,0
Exp/Cntr(USF)=0,0
Exp/Cntr=0.5,0.3

Type RM Length L Ch R = 1 ,20822   ,50.1,55.2,69.8
XS GIS Cut Line= 4
2323138.51337228597481.2296027352322704.79324651597386.520766561
2322469.66929101597175.1008066092322429.05633445597184.259298011
#Sta/Elev= 30
       0 3041.24    49.1 3039.51    92.5  3034.8   108.8 3035.08   149.8 3032.62
     170 3032.42   190.7 3031.75   260.3 3032.01   280.8 3030.42     289 3032.61
   297.7 3033.48     375 3033.13   440.5 3030.92   450.2 3031.37   499.1 3028.81
   511.8 3029.61   573.9 3027.83   584.6 3029.56   609.6 3026.07   613.5 3024.85
   620.9 3024.46   632.3 3024.73   635.1 3025.99   638.4 3028.12   643.4 3029.33
   659.9  3027.8   670.7 3027.95   760.1 3031.12   786.5 3044.41   801.8  3049.9
#Mann= 5 ,-1,0
       0     .06       0     130      .1       0     170     .06       0
   609.6    .045       0   635.1     .06       0
#XS Ineff= 2 ,-1
     290     583  3026.3     643     800  3026.4
Permanent Ineff=
       F       F
Bank Sta=609.6,635.1
XS Rating Curve= 0 ,0
Exp/Cntr=0.5,0.3

Type RM Length L Ch R = 1 ,20767   ,150.7,115,81.4
XS GIS Cut Line= 5
2323162.96033052 597440.770044792322723.03813355597338.760106814
2322539.98217555597170.2516421592322469.66929101 597110.84937764
2322406.76007426 597129.41743474
#Sta/Elev= 30
       0 3040.79    43.9 3039.91    88.6 3036.67   150.7  3034.4   183.5 3035.42
   204.1 3034.22   220.5 3032.21   294.4 3032.74   335.5 3031.78   376.5 3029.28
   440.9 3030.99   526.2 3029.68   569.7 3027.98   583.9 3026.13   591.4 3026.18
   596.8 3024.42   601.6 3023.72   630.3 3023.43   662.1 3023.59   666.5 3024.26
   672.7  3026.4   683.8 3028.39   720.7 3028.85   731.6 3031.73   736.8 3032.21
   792.4 3031.25   827.7 3032.61   840.6 3032.11   844.1 3032.68     858  3039.2
#Mann= 9 ,-1,0
       0      .1       0     190     .06       0     380      .1       0
     390     .06       0  581.59      .1       0   596.8    .045       0
   666.5     .06       0   720.4      .1       0   770.4     .06       0
#XS Ineff= 3 ,-1
     321     435    3033     435     580  3026.3     675     800  3026.4
Permanent Ineff=
       F       F       F
Bank Sta=596.8,666.5
XS Rating Curve= 0 ,0
Exp/Cntr(USF)=0,0
Exp/Cntr=0.5,0.3

Type RM Length L Ch R = 1 ,20652   ,68,66.9,65.6
XS GIS Cut Line= 3
2323049.57701334597014.4102678862322622.28304659597100.398095388
2322415.24144627597104.065134376
#Sta/Elev= 30
       0 3036.13     9.6 3034.21    25.9  3034.1    38.2 3032.85   122.4 3031.81
   136.1 3030.65   189.1 3029.07   225.8 3029.26   242.2 3027.85   270.7 3030.11
   299.3 3026.66   319.7 3025.53   356.4    3028   364.6 3027.09   380.9  3027.2
   393.1 3025.67   413.5 3026.66   433.9 3029.37   458.4 3027.48     466  3026.2
   470.1 3024.65   485.9 3023.31     502 3023.46   510.5 3024.61     518 3026.99
     522 3027.23     530 3025.39     546 3028.57     558  3029.9   642.9 3033.46
#Mann= 6 ,-1,0
       0      .1       0      70     .12       0     240      .1       0
   470.1    .045       0   510.5      .1       0  575.86     .06       0
Bank Sta=470.1,510.5
XS Rating Curve= 0 ,0
Exp/Cntr(USF)=0,0
Exp/Cntr=0.3,0.1