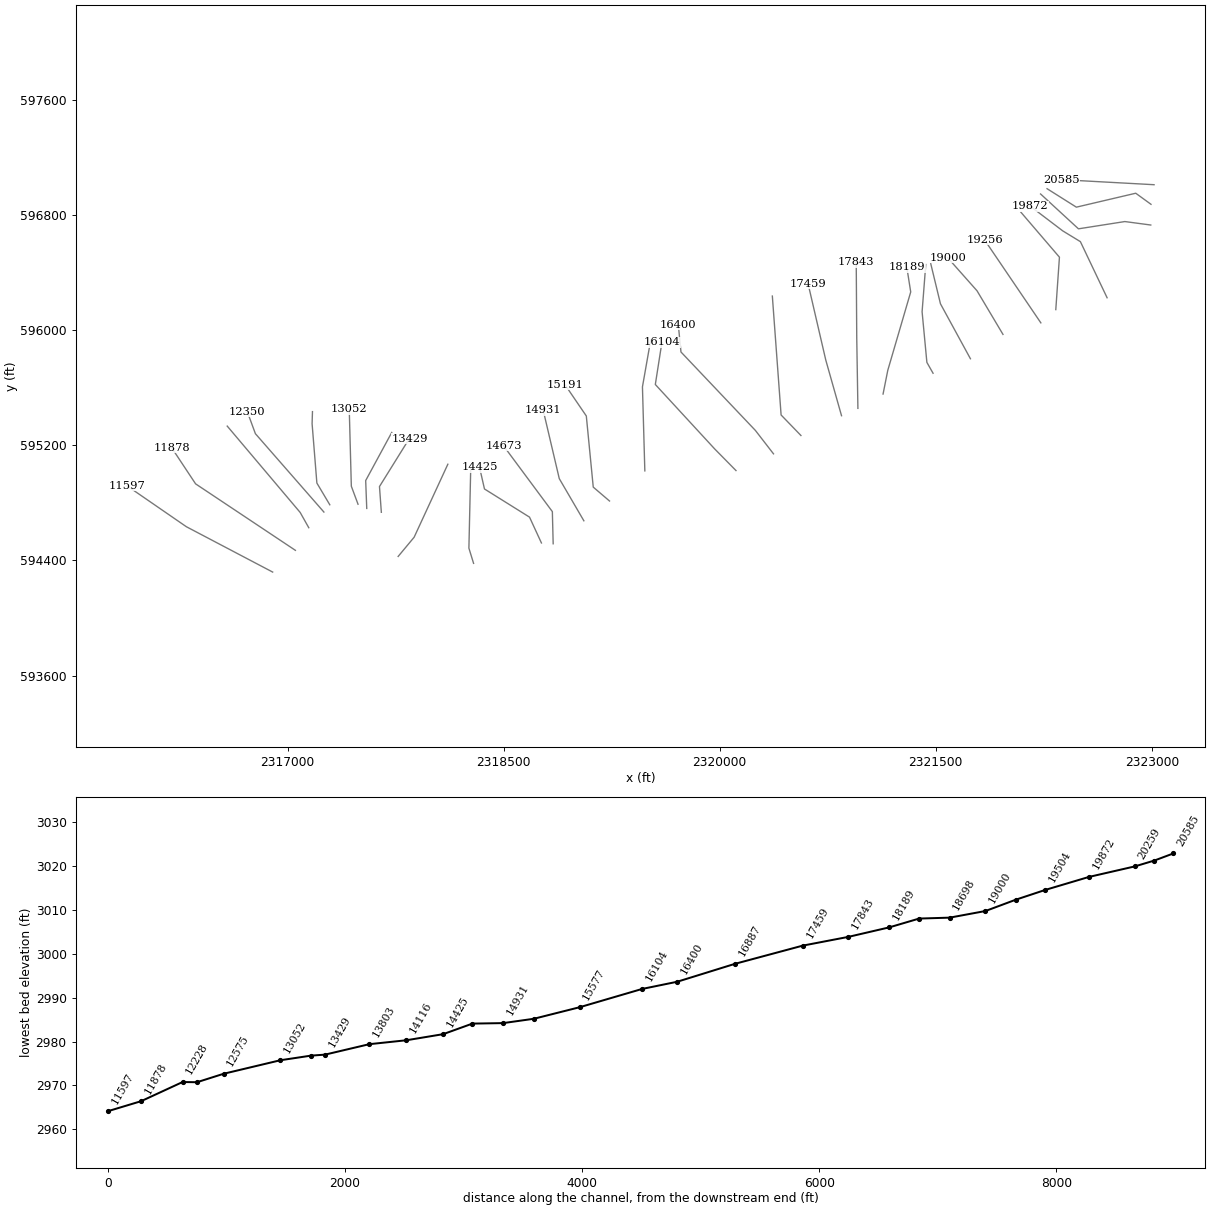
HEC-RAS study LTTLRV1.prj: LTTLRV1

--- LTTLRV1.g01 (geometry) --- (continued)

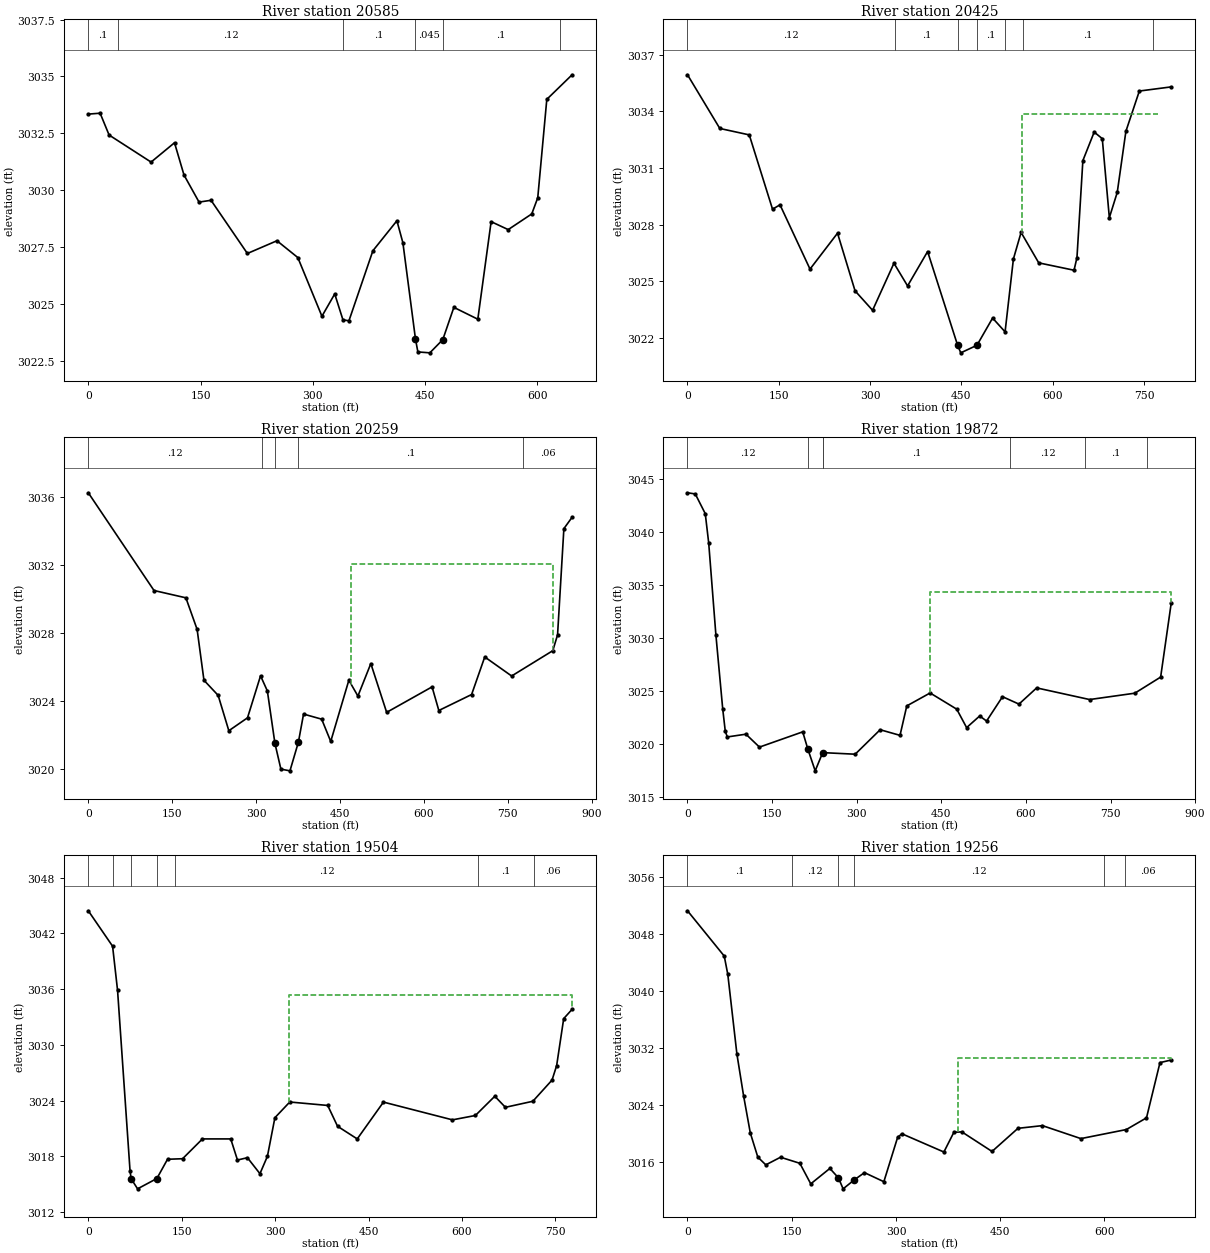
Type RM Length L Ch R = 1 ,20585   ,152.3,160.4,167.5
XS GIS Cut Line= 2
2323015.92909472597010.1368783992322370.37238618597045.362985864
#Sta/Elev= 30
       0 3033.34    15.8 3033.38    27.8 3032.42    83.9 3031.23   115.2 3032.08
   127.9 3030.66     148 3029.47     164 3029.55   212.6 3027.21   252.1 3027.77
     280 3027.03   312.2 3024.45   329.3 3025.43   340.3 3024.29   348.3 3024.25
   380.3 3027.33   412.4 3028.65   420.4 3027.68   437.2 3023.45   440.4 3022.88
   456.4 3022.84   473.7 3023.42   488.5 3024.84   520.5 3024.32   538.3 3028.61
   561.1 3028.26   592.6 3028.95   600.6 3029.66   612.7 3033.99   646.5 3035.07
#Mann= 6 ,-1,0
       0      .1       0      40     .12       0     340      .1       0
   437.2    .045       0   473.7      .1       0     630     .06       0
Bank Sta=437.2,473.7
XS Rating Curve= 0 ,0
Exp/Cntr(USF)=0,0
Exp/Cntr=0.3,0.1

Type RM Length L Ch R = 1 ,20425   ,169.6,165.6,162.5
XS GIS Cut Line= 4
2322994.66117141596873.9548566712322888.61231792596950.947589093
2322476.37904568596854.1471671252322273.00801431596982.415066486
#Sta/Elev= 30
       0 3035.93    53.1 3033.09   101.5 3032.75   139.7 3028.82     152 3029.05
   201.3 3025.65   246.5 3027.55   275.3  3024.5   304.1 3023.47   339.2 3025.96
   361.6 3024.76   394.5 3026.58   443.8 3021.62     449 3021.22   475.6 3021.62
   501.3 3023.06   521.8 3022.33   535.5 3026.19   548.1 3027.59   577.1 3025.98
   635.1 3025.59   639.9 3026.26   649.6 3031.39   668.2  3032.9   681.5 3032.55
   693.1 3028.37   706.1 3029.71   720.3 3032.94   742.4 3035.07   794.9 3035.29
#Mann= 7 ,-1,0
       0     .12       0  341.05      .1       0   443.8    .045       0
   475.6      .1       0  521.05     .12       0  551.05      .1       0
   764.5     .06       0
#XS Ineff= 1 ,-1
  549.57  772.373033.877
Permanent Ineff=
       F
Bank Sta=443.8,475.6
XS Rating Curve= 0 ,0
Exp/Cntr(USF)=0,0
Exp/Cntr=0.3,0.1

Type RM Length L Ch R = 1 ,20259   ,419.1,387,359.7
XS GIS Cut Line= 4
2322993.04262261 596729.998087272322813.26447092596754.137282095
2322490.95862058596703.6347008352322227.99045886596945.711568798
#Sta/Elev= 30
       0 3036.24   117.5 3030.49   174.5 3030.06   194.6  3028.2   206.8 3025.21
   232.2 3024.32   251.3 3022.24   284.7    3023     308 3025.47   320.2 3024.58
   333.7  3021.5   344.4 3019.98   360.6 3019.88   375.7 3021.57   384.9 3023.22
   417.3 3022.92   433.5 3021.61   465.9 3025.21   482.1 3024.28   505.2 3026.19
   533.5 3023.32   614.7 3024.82   626.8 3023.43   685.4 3024.37   708.9 3026.58
     757 3025.46   830.6 3026.95   839.1 3027.88   850.4 3034.13   865.1  3034.8
#Mann= 5 ,-1,0
       0     .12       0  311.39      .1       0   333.7    .045       0
   375.7      .1       0  777.63     .06       0
#XS Ineff= 1 ,-1
  470.53   830.4 3032.07
Permanent Ineff=
       F
Bank Sta=333.7,375.7
XS Rating Curve= 0 ,0
Exp/Cntr=0.3,0.1

Type RM Length L Ch R = 1 ,19872   ,380.7,368.7,342.3
XS GIS Cut Line= 4
 2322689.7930029596224.7097658592322504.41377726596614.528874979
2322382.18755079596689.1312196362322156.95653215596860.324232339
#Sta/Elev= 30
       0 3043.73    13.8 3043.62    31.5 3041.76    37.6 3038.99    50.3 3030.34
    62.5  3023.3      67 3021.21    70.6 3020.68   103.6 3020.94   127.6 3019.72
   204.3 3021.16   213.1 3019.58   226.4 3017.48   239.7  3019.2   297.3 3019.05
   341.6 3021.36   376.8 3020.83   388.8 3023.61   430.2 3024.83   477.4  3023.3
   494.9 3021.56   518.1 3022.66   530.3 3022.18   558.5 3024.48   587.7 3023.78
   619.1 3025.31     713 3024.21   793.1 3024.81   838.9 3026.33   857.8 3033.37
#Mann= 7 ,-1,0
       0     .12       0   213.1    .045       0   239.7     .12       0
     240      .1       0  571.65     .12       0  704.85      .1       0
  814.85     .06       0
#XS Ineff= 2 , 0
                          429.95         3034.34
Permanent Ineff=
       F       F
Bank Sta=213.1,239.7
XS Rating Curve= 0 ,0
Exp/Cntr=0.3,0.1

Type RM Length L Ch R = 1 ,19504   ,228.4,247.8,257
XS GIS Cut Line= 3
2322333.58912128596142.2720690472322358.92557209596506.589647806
2322091.19481765596819.261734041
#Sta/Elev= 30
       0 3044.43      39 3040.62      47 3035.86    67.1 3016.39    68.9  3015.6
    79.1 3014.52   110.1 3015.63   127.2  3017.7   151.4 3017.76   183.3 3019.89
   228.7 3019.89   239.5 3017.62   255.5 3017.87   275.6 3016.15   287.6 3018.02
   299.6 3022.17   323.5 3023.86   384.4 3023.49   400.2 3021.25   431.8 3019.89
   473.9 3023.85   584.7 3021.94   621.5 3022.41   652.7 3024.48   669.7 3023.29
   713.8 3023.94   744.6 3026.22     752 3027.78   763.3 3032.83   776.8 3033.83
#Mann= 7 ,-1,0
       0     .12       0      40      .1       0    68.9    .045       0
   110.1      .1       0     140     .12       0   625.2      .1       0
   715.2     .06       0
#XS Ineff= 2 , 0
                          322.32          3035.4
Permanent Ineff=
       F       F
Bank Sta=68.9,110.1
XS Rating Curve= 0 ,0
Exp/Cntr=0.3,0.1

Type RM Length L Ch R = 1 ,19256   ,257,256.1,256.1
XS GIS Cut Line= 2
 2322229.8278607596050.324264205 2321839.1677361596626.708054603
#Sta/Elev= 30
       0 3051.27    52.9 3044.92      58 3042.36    71.1  3031.2    80.8  3025.3
    90.4 3020.13   101.2 3016.75   112.7 3015.66   133.9 3016.73   161.7 3015.88
   177.4    3013   204.9 3015.16   217.13013.853     224  3012.3   240.2 3013.57
   254.7 3014.57   282.6  3013.3   302.4 3019.51   308.5 3020.02     369 3017.46
   383.4 3020.23   394.9 3020.28   438.3 3017.54   475.6 3020.78   510.8 3021.16
   566.2 3019.34   631.6 3020.61   660.6 3022.25     680 3029.99   696.3 3030.36
#Mann= 6 ,-1,0
       0      .1       0     150     .12       0   217.1    .045       0
   240.2     .12       0     600      .1       0     630     .06       0
#XS Ineff= 2 , 0
                          389.57         3030.66
Permanent Ineff=
       F       F
Bank Sta=217.1,240.2
XS Rating Curve= 0 ,0
Exp/Cntr(USF)=0,0
Exp/Cntr=0.3,0.1

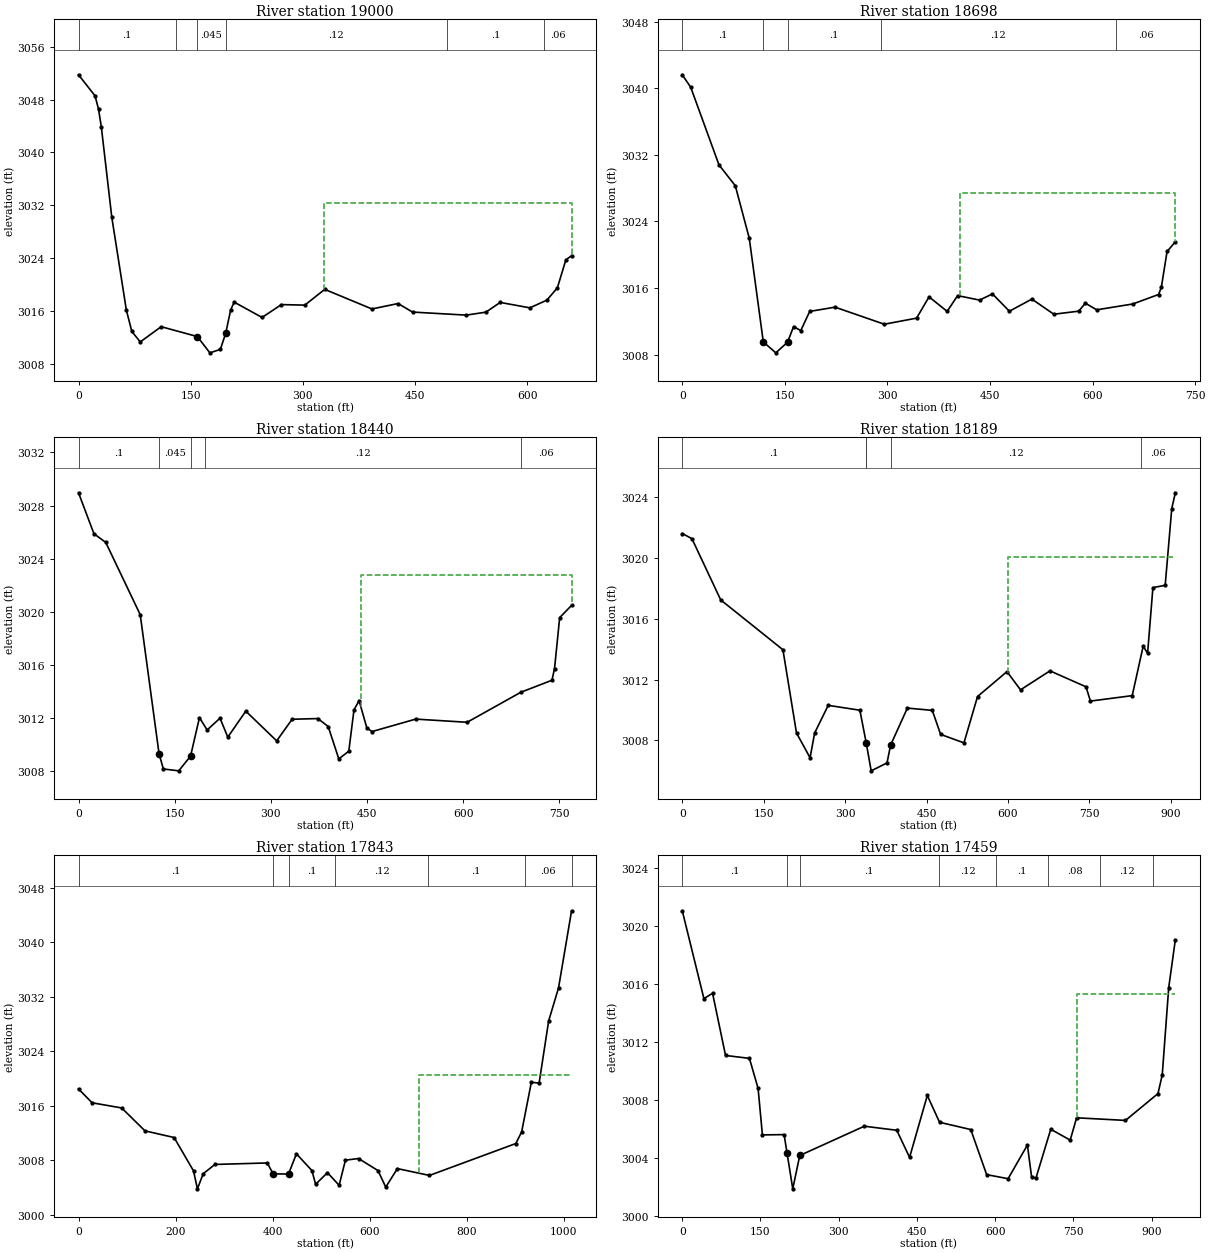
Type RM Length L Ch R = 1 ,19000   ,297.9,301.8,296.2
XS GIS Cut Line= 3
 2321966.9084761595970.1566641682321786.73511652596273.116749184
2321583.05811389596502.835883479
#Sta/Elev= 30
       0 3051.74    22.1 3048.56    26.8 3046.53    30.5 3043.88    44.5 3030.22
      64 3016.18    71.3 3012.95    82.6 3011.37   110.6 3013.67   158.9 3012.18
   175.7 3009.72   189.7 3010.24   196.8 3012.65   203.6 3016.24   208.3 3017.38
   245.5 3015.07   271.4 3017.01   302.7 3016.93   329.3 3019.31   392.5 3016.35
   427.4 3017.17   446.8 3015.88   518.7 3015.42     545 3015.87     564 3017.34
   603.7 3016.52   626.4 3017.68   640.5 3019.54   651.9  3023.8   659.5 3024.38
#Mann= 6 ,-1,0
       0      .1       0     130     .12       0   158.9    .045       0
   196.8     .12       0  492.49      .1       0  622.49     .06       0
#XS Ineff= 2 , 0
                           328.7         3032.37
Permanent Ineff=
       F       F
Bank Sta=158.9,196.8
XS Rating Curve= 0 ,0
Exp/Cntr=0.3,0.1

Type RM Length L Ch R = 1 ,18698   ,270.4,257.7,244.6
XS GIS Cut Line= 3
2321740.91346622595801.0345706782321532.87832467596182.681772801
2321465.52881841596461.059731997
#Sta/Elev= 30
       0 3041.63    12.4 3040.12    53.7  3030.8    77.6 3028.29      98 3021.98
   118.5 3009.53   136.8 3008.21     154 3009.49   162.8 3011.37   173.3 3010.88
   186.4 3013.19   223.4  3013.7   295.5 3011.65   342.7 3012.38   360.9 3014.94
   387.4 3013.19   402.7 3015.09   434.7 3014.55   453.7 3015.29   478.4 3013.21
   511.3 3014.67   543.4 3012.85   579.8 3013.22   589.5 3014.18     606 3013.38
   658.8 3014.08   696.5 3015.22   700.6 3016.07     709 3020.39   721.1 3021.55
#Mann= 5 ,-1,0
       0      .1       0   118.5    .045       0     154      .1       0
     290     .12       0  634.66     .06       0
#XS Ineff= 2 , 0
                           405.8         3027.42
Permanent Ineff=
       F       F
Bank Sta=118.5,154
XS Rating Curve= 0 ,0
Exp/Cntr(USF)=0,0
Exp/Cntr=0.3,0.1

Type RM Length L Ch R = 1 ,18440   ,254.9,251.2,224.8
XS GIS Cut Line= 4
2321481.43632916595700.2715490582321438.58901591 595775.59142387
2321405.37870638596127.375270585     2321430.857596455.709473341
#Sta/Elev= 30
       0 3028.96    24.1 3025.87    42.5 3025.22    96.3 3019.77   125.7 3009.28
   132.4 3008.14   156.4    3008   174.8 3009.11   188.7 3012.01   200.7 3011.08
   220.8 3011.97   232.9 3010.54     261  3012.5   309.2 3010.26   333.3 3011.89
   373.5 3011.94   389.6 3011.34   406.1  3008.9   421.7 3009.48   429.8  3012.6
   437.8 3013.29   449.8 3011.24   457.9 3010.96   526.1  3011.9   606.3 3011.66
     690 3013.92   738.7 3014.83   742.7 3015.71   750.7 3019.55   769.3 3020.47
#Mann= 5 ,-1,0
       0      .1       0   125.7    .045       0   174.8      .1       0
  196.65     .12       0     690     .06       0
#XS Ineff= 2 , 0
                          440.58         3022.78
Permanent Ineff=
       F       F
Bank Sta=125.7,174.8
XS Rating Curve= 0 ,0
Exp/Cntr=0.3,0.1

Type RM Length L Ch R = 1 ,18189   ,324.4,345.7,349.8
XS GIS Cut Line= 4
 2321134.3421184595555.6979903372321167.17484469595720.663394399
2321326.33983881596264.9978360042321299.40003631596435.616585188
#Sta/Elev= 30
       0 3021.62    17.8 3021.28    70.8 3017.25   185.4 3013.97   210.4 3008.49
   235.4 3006.86   243.8 3008.49   268.8 3010.31   327.1 3009.99   338.83007.842
   347.9    3006   377.1 3006.52   383.73007.693   414.6 3010.13   460.5 3009.98
   475.8  3008.4   518.8 3007.84   543.8 3010.89     598 3012.53     623 3011.33
   677.2 3012.58   743.6 3011.53   751.7 3010.59   828.7 3010.95   848.9 3014.21
     857 3013.73   866.8 3018.06   889.4 3018.21   901.5 3023.26   908.1  3024.3
#Mann= 5 ,-1,0
       0      .1       0   338.2     .12       0   338.8    .045       0
   383.7     .12       0  845.33     .06       0
#XS Ineff= 2 , 0
                             600          3020.1
Permanent Ineff=
       F       F
Bank Sta=338.8,383.7
XS Rating Curve= 0 ,0
Exp/Cntr(USF)=0,0
Exp/Cntr=0.3,0.1

Type RM Length L Ch R = 1 ,17843   ,371.8,384.1,393.4
XS GIS Cut Line= 3
2320959.66519191595456.1968653862320951.63443778595945.450274752
2320948.10221222596472.085523473
#Sta/Elev= 30
       0 3018.49      28 3016.46      89  3015.7     137 3012.34     197 3011.36
     237 3006.46     245 3003.83     257 3006.05     281 3007.41     389 3007.63
     401 3006.03   432.7    3006     449 3008.97     481 3006.51   488.5  3004.5
     513  3006.2     537 3004.35     550 3008.04   577.1 3008.28   617.1 3006.51
   633.1 3004.08   657.1  3006.8   723.2  3005.8   901.1 3010.48   913.1 3012.19
   933.1 3019.47   949.1 3019.35   968.8 3028.49   989.1 3033.32    1016 3044.64
#Mann= 7 ,-1,0
       0      .1       0     401    .045       0   432.7      .1       0
  529.32     .12       0  719.32      .1       0  919.32     .06       0
 1015.97      .1       0
#XS Ineff= 1 ,-1
  701.45  1014.8 3020.49
Permanent Ineff=
       F
Bank Sta=401,432.7
XS Rating Curve= 0 ,0
Exp/Cntr=0.3,0.1

Type RM Length L Ch R = 1 ,17459   ,568.4,572.4,565.4
XS GIS Cut Line= 3
2320845.93588825595405.2831930432320736.58517766595792.061870546
 2320613.8996974596321.551312511
#Sta/Elev= 30
       0 3021.02    41.5 3014.96    58.1 3015.33      83 3011.04   128.8 3010.84
   145.4 3008.77   153.7 3005.56   195.3 3005.58   200.93004.321   211.9 3001.84
   225.3 3004.14   349.1 3006.16   411.3 3005.88   435.9 3004.01   469.9 3008.28
   493.4 3006.43   553.2 3005.93   583.7 3002.82   624.8 3002.54   661.8 3004.86
   669.9 3002.66   678.2 3002.58   706.6 3005.95   743.9  3005.2   756.2 3006.74
   849.9 3006.56   912.2 3008.41   920.4  3009.7   932.8 3015.72   945.5 3019.02
#Mann= 8 ,-1,0
       0      .1       0   200.9    .045       0   225.3      .1       0
  491.94     .12       0  601.94      .1       0  701.94     .08       0
  801.94     .12       0  901.94      .1       0
#XS Ineff= 2 , 0
                          757.49         3015.29
Permanent Ineff=
       F       F
Bank Sta=200.9,225.3
XS Rating Curve= 0 ,0
Exp/Cntr(USF)=0,0
Exp/Cntr=0.3,0.1

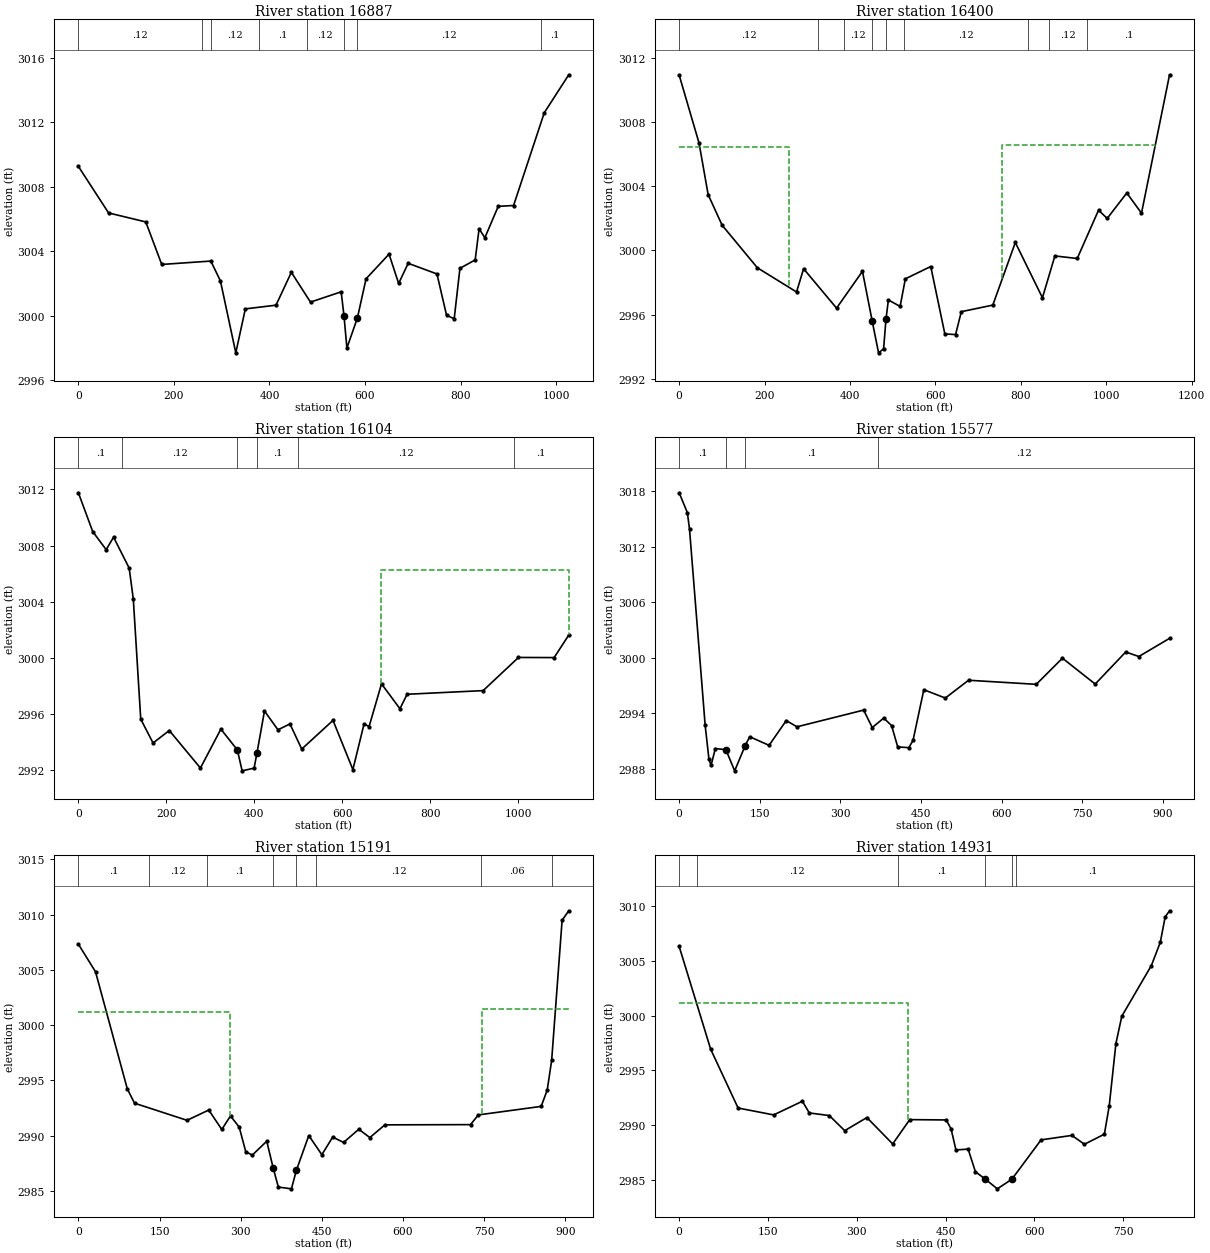
Type RM Length L Ch R = 1 ,16887   ,462.4,487.1,495.7
XS GIS Cut Line= 3
2320564.14748372595267.7273374452320426.45580046 595410.22221896
2320365.61528925596236.372318532
#Sta/Elev= 30
       0 3009.27    63.2 3006.38   141.1 3005.82   174.5 3003.18   277.3 3003.39
   297.4 3002.15   329.5 2997.69   349.5 3000.42   413.7 3000.65   445.8 3002.69
   485.9 3000.84   550.1 3001.48     556 2999.99   562.1 2997.99   584.1 2999.86
   602.2 3002.29   650.3 3003.82   670.4    3002   690.4 3003.25   750.6 3002.59
   770.7 3000.02   786.7 2999.81   798.7 3002.94   830.6 3003.46   838.8 3005.39
   850.9 3004.84   878.9 3006.79     911 3006.84   975.2  3012.6  1026.5 3014.96
#Mann= 8 ,-1,0
       0     .12       0  258.15      .1       0  278.15     .12       0
  378.15      .1       0  478.15     .12       0     556    .045       0
   584.1     .12       0  968.15      .1       0
Bank Sta=556,584.1
XS Rating Curve= 0 ,0
Exp/Cntr(USF)=0,0
Exp/Cntr=0.3,0.1

Type RM Length L Ch R = 1 ,16400   ,295.7,296.1,295
XS GIS Cut Line= 4
 2320373.6675498595140.3216820792320247.70769961595303.184392504
  2319731.251994595847.9036782552319712.66688916 596038.56390893
#Sta/Elev= 30
       0 3010.95    46.6  3006.7    67.8 3003.49   100.5 3001.58   183.1 2998.92
   274.8 2997.41   291.3 2998.86   368.5  2996.4   429.1  2998.7  451.78 2995.61
   466.8 2993.61   478.6 2993.86   484.2 2995.71   489.8 2996.91   517.3 2996.51
   529.5 2998.23     589    2999     622 2994.79   647.1 2994.75   660.6 2996.18
   734.3 2996.59     787  3000.5   850.5 2997.05   879.6 2999.66   931.9  2999.5
   981.9 3002.52    1002    3002    1048 3003.59  1082.4 3002.33  1148.1 3010.97
#Mann= 9 ,-1,0
       0     .12       0  325.89      .1       0  385.89     .12       0
  451.78    .045       0   484.2      .1       0  525.89     .12       0
  815.89      .1       0  865.89     .12       0  955.89      .1       0
#XS Ineff= 2 ,-1
       0  257.39 3006.47  755.94  1113.4 3006.56
Permanent Ineff=
       F       F
Bank Sta=451.78,484.2
XS Rating Curve= 0 ,0
Exp/Cntr=0.3,0.1

Type RM Length L Ch R = 1 ,16104   ,542.5,526.3,501.4
XS GIS Cut Line= 4
2320113.20789829595024.1364674282319965.87498364595173.816267586
2319553.16990111595622.099063424 2319598.7926932595914.084932817
#Sta/Elev= 30
       0 3011.76    32.6    3009    63.2 3007.71      80  3008.6   115.5  3006.4
   124.9 3004.19   141.8 2995.65   169.8 2993.95   206.7 2994.84   277.5 2992.17
     324 2994.94   361.4 2993.46   372.3 2991.97   399.5 2992.16   406.1 2993.25
   423.1 2996.23   453.8 2994.89     481 2995.31   507.8 2993.52   578.9 2995.56
   624.1 2992.06   649.5 2995.31   660.9 2995.12   689.2 2998.16   731.1 2996.39
   747.4 2997.42   920.2 2997.68  1000.6 3000.04  1081.6 3000.03  1114.9 3001.63
#Mann= 6 ,-1,0
       0      .1       0     100     .12       0   361.4    .045       0
   406.1      .1       0  500.03     .12       0  989.36      .1       0
#XS Ineff= 2 , 0
                             689        3006.257
Permanent Ineff=
       F       F
Bank Sta=361.4,406.1
XS Rating Curve= 0 ,0
Exp/Cntr(USF)=0,0
Exp/Cntr=0.3,0.1

Type RM Length L Ch R = 1 ,15577   ,383.2,386.4,387.5
XS GIS Cut Line= 3
2319480.37173708595021.9296998642319463.77815685595605.613798091
2319520.80215399 595929.53261546
#Sta/Elev= 30
       0  3017.8    15.3 3015.65    19.3 3013.85    48.4 2992.71    55.3 2989.12
    59.3 2988.39    67.3 2990.21    86.92990.094   103.3 2987.81   122.92990.536
   131.3 2991.49   167.3 2990.56   199.3 2993.23   219.3 2992.56   343.4 2994.36
   359.4 2992.48   380.8  2993.5   395.4 2992.69   406.8 2990.39   427.5 2990.31
   435.3 2991.09   455.4 2996.56   495.4 2995.66   538.6 2997.58   664.7 2997.14
   713.4 2999.96   774.4 2997.17   831.2 3000.63   855.6 3000.14   912.8  3002.1
#Mann= 4 ,-1,0
       0      .1       0    86.9    .045       0   122.9      .1       0
     370     .12       0
Bank Sta=86.9,122.9
XS Rating Curve= 0 ,0
Exp/Cntr=0.3,0.1

Type RM Length L Ch R = 1 ,15191   ,256.5,259.9,265.5
XS GIS Cut Line= 4
2319235.12119405594812.6161715872319122.20478362594909.108376863
2319074.08127469595403.2819365452318926.99899052595619.325308092
#Sta/Elev= 30
       0 3007.32    31.7 3004.82    90.4 2994.23   103.8 2992.93   200.8 2991.38
     241 2992.31   265.1 2990.55   281.2 2991.78   297.3 2990.76   309.4 2988.54
   321.4 2988.23   348.2 2989.49   360.1 2987.06   369.6 2985.34   393.8 2985.18
   403.1 2986.88   425.9    2990     450 2988.27   470.1 2989.86   490.2 2989.38
   518.3 2990.57   538.7 2989.82   566.6 2990.97   724.8 2990.99   739.3 2991.87
   855.4 2992.64   866.6 2994.12   874.8 2996.81   894.1 3009.48   906.4 3010.34
#Mann= 8 ,-1,0
       0      .1       0     130     .12       0  238.53      .1       0
   360.1    .045       0   403.1      .1       0  438.53     .12       0
  745.04     .06       0  875.04      .1       0
#XS Ineff= 2 , 0
          280.19 3001.18  745.89         3001.44
Permanent Ineff=
       F       F
Bank Sta=360.1,403.1
XS Rating Curve= 0 ,0
Exp/Cntr(USF)=0,0
Exp/Cntr=0.3,0.1

Type RM Length L Ch R = 1 ,14931   ,246.7,258.3,273
XS GIS Cut Line= 3
 2319056.9681396594675.2431623722318886.32713661594968.088692025
2318774.47795147595444.409808862
#Sta/Elev= 30
       0 3006.32    53.2 2996.94    99.5 2991.57   159.6 2990.94   208.1 2992.19
   219.8 2991.12   253.6 2990.88   279.6  2989.5     317  2990.7   360.6 2988.29
   389.4 2990.51     451 2990.48   459.2 2989.67   467.4 2987.74     488 2987.82
   500.3 2985.75   516.7 2985.09   537.3 2984.19   561.9 2985.07   611.2 2988.66
   663.3 2989.07   684.4 2988.26   718.1 2989.18   726.3 2991.76   737.6 2997.46
   747.6 2999.96   797.5 3004.58   812.6 3006.71   820.8 3009.03   828.2 3009.58
#Mann= 6 ,-1,0
       0      .1       0      30     .12       0  368.93      .1       0
   516.7    .045       0   561.9     .12       0  568.93      .1       0
#XS Ineff= 2 , 0
          386.89 3001.19
Permanent Ineff=
       F       F
Bank Sta=516.7,561.9
XS Rating Curve= 0 ,0
Exp/Cntr=0.3,0.1

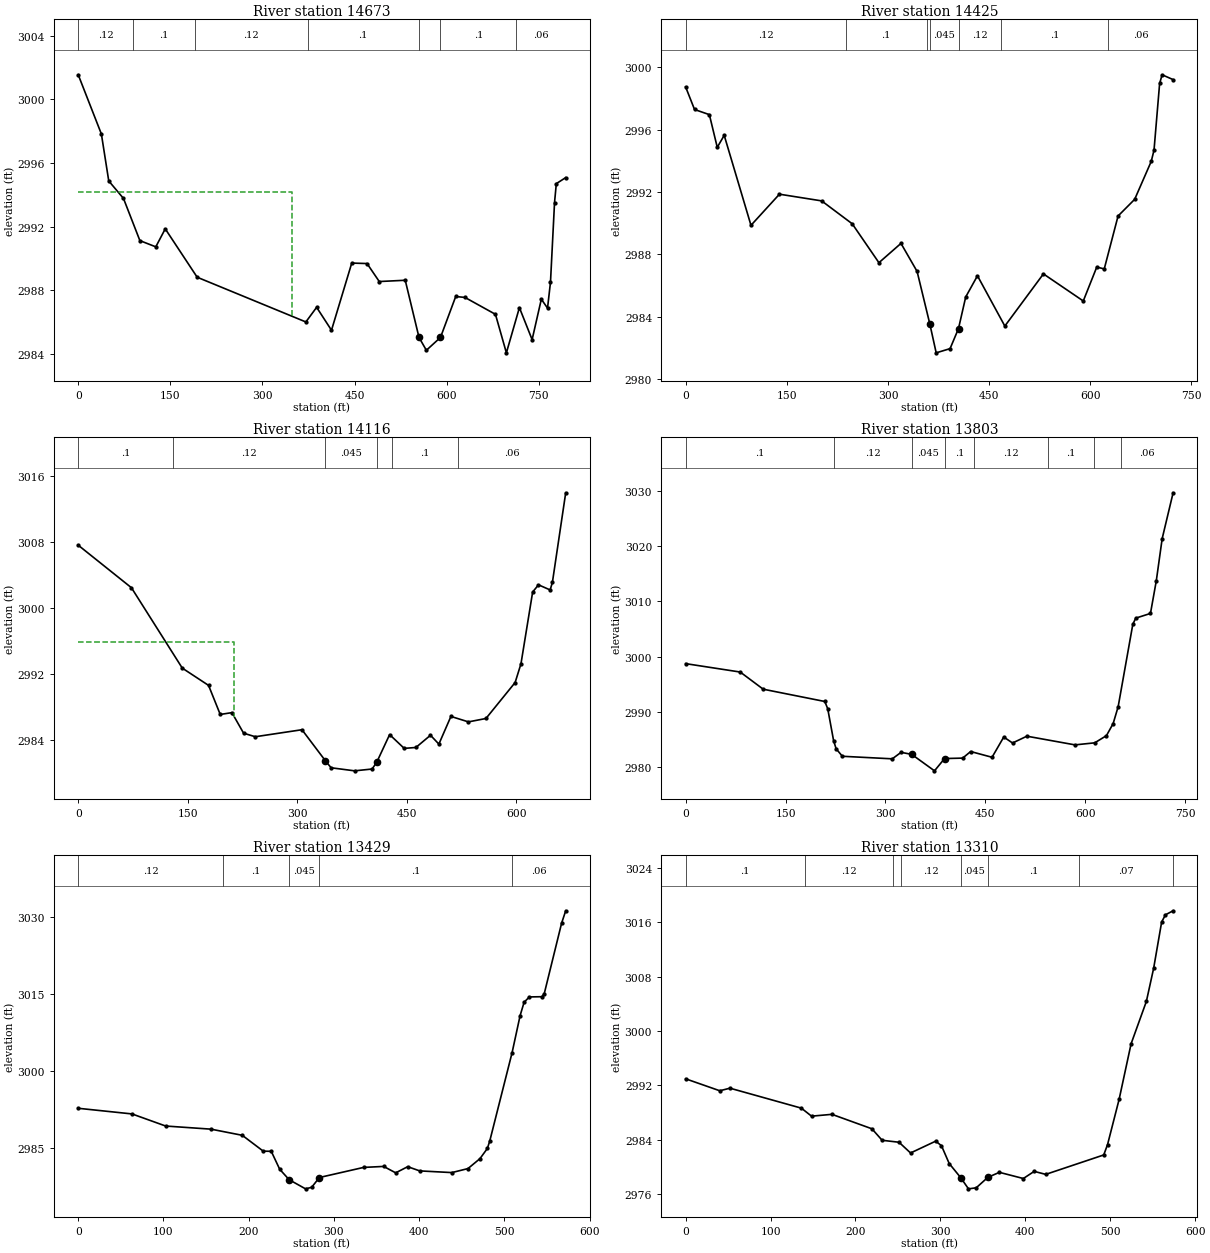
Type RM Length L Ch R = 1 ,14673   ,242.5,247.5,261.6
XS GIS Cut Line= 3
2318843.99861854 594515.523411692318838.29576953594738.846978983
 2318498.6340824595197.127925552
#Sta/Elev= 30
       0 3001.55    37.7 2997.83    49.7 2994.88    73.7 2993.78   100.4 2991.13
   126.3 2990.74   141.7 2991.87   193.7 2988.83   370.7 2986.02   388.2 2986.94
   412.4  2985.5   445.4 2989.72   470.3 2989.69   490.2 2988.56   532.5 2988.64
   554.9 2985.05   566.9 2984.24   589.9 2985.05   614.7 2987.62   629.8 2987.56
   679.4  2986.5   697.2 2984.08   718.4 2986.92   739.1 2984.91   754.1 2987.45
   764.2 2986.89     769 2988.51   775.6 2993.52   778.5 2994.71   793.8 2995.09
#Mann= 7 ,-1,0
       0     .12       0      90      .1       0     190     .12       0
   373.4      .1       0   554.9    .045       0   589.9      .1       0
   713.4     .06       0
#XS Ineff= 2 , 0
          347.98  2994.2
Permanent Ineff=
       F       F
Bank Sta=554.9,589.9
XS Rating Curve= 0 ,0
Exp/Cntr(USF)=0,0
Exp/Cntr=0.3,0.1

Type RM Length L Ch R = 1 ,14425   ,341.8,308.7,271.1
XS GIS Cut Line= 4
2318762.38052965594521.1968573962318679.75656701594700.523833625
2318366.97857519594896.2363475122318332.27149012595048.687783096
#Sta/Elev= 30
       0 2998.75    13.2  2997.3    35.2 2996.97    46.9 2994.87    57.2 2995.64
    96.9 2989.86   139.1 2991.86   201.7 2991.43     247 2989.96   286.6 2987.46
   319.3  2988.7   343.2  2986.9   362.1 2983.52   371.5 2981.67   392.1 2981.94
   404.6 2983.23   415.3 2985.26   432.7 2986.62   473.3 2983.39   530.5 2986.74
   589.6    2985   609.6 2987.18   620.7 2987.06   641.2 2990.46   665.8 2991.53
   690.4 2993.97   694.5 2994.69   702.8 2998.97   706.5 2999.53   722.8 2999.22
#Mann= 7 ,-1,0
       0     .12       0  237.45      .1       0  357.45     .12       0
   362.1    .045       0   404.6     .12       0  467.45      .1       0
  626.41     .06       0
Bank Sta=362.1,404.6
XS Rating Curve= 0 ,0
Exp/Cntr=0.3,0.1

Type RM Length L Ch R = 1 ,14116   ,330.4,313.9,303.6
XS GIS Cut Line= 3
2318291.33958471594379.4687693862318258.85957177   594485.019227
2318271.63094367595042.484790232
#Sta/Elev= 30
       0 3007.62    72.9 3002.47   142.6 2992.73   178.6 2990.64   194.6 2987.12
   210.6 2987.34   226.6 2984.85   242.6 2984.42   306.6 2985.27   338.7 2981.51
   338.7 2981.49   346.6 2980.66   378.7 2980.29   402.7 2980.51   409.1 2981.34
   426.7 2984.68   446.7 2983.01   462.7 2983.12   482.7  2984.6   494.2 2983.53
   510.7 2986.88   534.7 2986.22   558.7 2986.63   598.7 2990.99   606.7 2993.26
   622.7 3001.95   630.7 3002.82   646.7  3002.2   649.8 3003.14     668 3013.97
#Mann= 6 ,-1,0
       0      .1       0  130.43     .12       0   338.7    .045       0
   409.1     .12       0  430.43      .1       0  520.43     .06       0
#XS Ineff= 2 , 0
          213.72 2995.89
Permanent Ineff=
       F       F
Bank Sta=338.7,409.1
XS Rating Curve= 0 ,0
Exp/Cntr=0.3,0.1

Type RM Length L Ch R = 1 ,13803   ,379.4,373.4,368.2
XS GIS Cut Line= 3
2317767.77583769594427.5345089632317878.63922247594560.981175834
2318112.68414591595068.078509942
#Sta/Elev= 30
       0 2998.76      82 2997.24   116.5 2994.14     209 2991.92   213.4  2990.6
   222.2 2984.84     226 2983.37   235.4 2982.02   310.3 2981.56   323.5 2982.73
   339.4 2982.37   373.7 2979.39   388.8 2981.61     416 2981.69     428 2982.88
   460.1 2981.84   477.7  2985.5   490.9 2984.42   512.4 2985.65   584.7 2984.08
   614.3 2984.45   631.9 2985.75     642 2987.94   649.5 2990.99   671.5 3005.87
   675.9 3006.98     698 3007.83   706.8 3013.76   715.6 3021.36     732 3029.63
#Mann= 8 ,-1,0
       0      .1       0  223.49     .12       0   339.4    .045       0
   388.8      .1       0  433.49     .12       0  543.49      .1       0
  613.49     .12       0  653.49     .06       0
Bank Sta=339.4,388.8
XS Rating Curve= 0 ,0
Exp/Cntr(USF)=0,0
Exp/Cntr=0.3,0.1

Type RM Length L Ch R = 1 ,13429   ,119.5,119.2,121.5
XS GIS Cut Line= 3
 2317650.9309347594734.2684248122317638.02678609594913.117396046
2317845.32160312595246.590793672
#Sta/Elev= 30
       0 2992.72    63.1 2991.62   102.6 2989.26   155.8 2988.65   192.5 2987.45
   217.1 2984.36   226.5 2984.33   236.4 2980.83   247.5 2978.79   266.7 2977.01
   273.9 2977.31     283 2979.22   334.9 2981.19   358.4 2981.38   372.5 2980.13
   386.6 2981.33   400.7 2980.51   438.4 2980.18   457.3 2980.96   471.4  2982.9
   480.1 2984.89     483 2986.42   509.1 3003.58   518.5  3010.8   523.2 3013.41
   529.4 3014.44     544 3014.48   546.8 3015.06   567.2 3028.83     572 3031.24
#Mann= 5 ,-1,0
       0     .12       0     170      .1       0   247.5    .045       0
     283      .1       0  509.31     .06       0
Bank Sta=247.5,283
XS Rating Curve= 0 ,0
Exp/Cntr=0.3,0.1

Type RM Length L Ch R = 1 ,13310   ,240.9,257.9,263.2
XS GIS Cut Line= 3
2317549.63214703594760.9869904132317542.24125471594954.587308657
2317723.31811653595289.025186092
#Sta/Elev= 30
       0 2992.98    40.2 2991.22    52.2  2991.6   136.3 2988.66   148.3 2987.48
   172.3 2987.75   219.4 2985.62   231.4 2983.93   251.3 2983.64   264.9 2982.06
   294.5  2983.8   301.3 2983.13   310.4 2980.51     324 2978.42   333.1 2976.78
   342.2 2976.93   355.9 2978.47   369.5 2979.21   397.7  2978.3   410.5 2979.35
   424.1 2978.91   492.4 2981.77   496.9  2983.3   510.5 2989.95   524.6 2998.13
   542.6 3004.37   551.2 3009.27   560.6 3016.07   565.1 3017.13   574.1 3017.72
#Mann= 8 ,-1,0
       0      .1       0     140     .12       0  243.74      .1       0
  253.74     .12       0     324    .045       0   355.9      .1       0
  463.74     .07       0  573.74      .1       0
Bank Sta=324,355.9
XS Rating Curve= 0 ,0
Exp/Cntr(USF)=0,0
Exp/Cntr=0.3,0.1

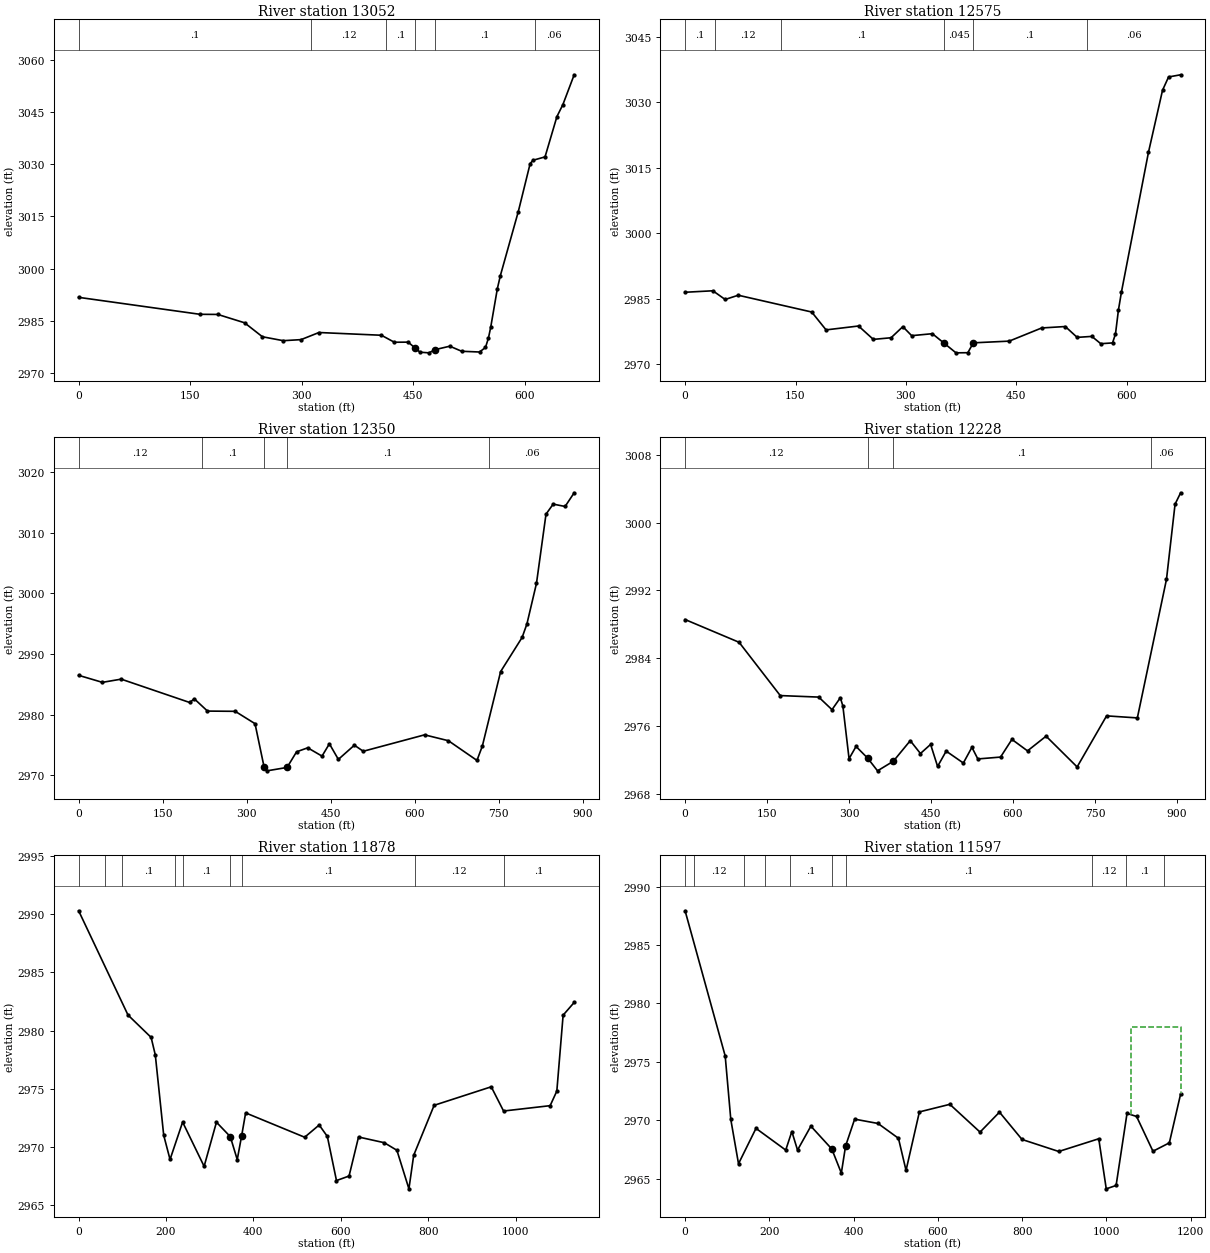
Type RM Length L Ch R = 1 ,13052   ,468.7,477.1,467.4
XS GIS Cut Line= 3
 2317489.0559255594790.3435320132317442.62500905594915.226686599
2317428.21541429595448.381692719
#Sta/Elev= 30
       0  2991.7   163.2 2986.82   187.2 2986.78   223.2 2984.38   247.2 2980.36
   275.2 2979.23   299.2 2979.53   323.3 2981.58   407.3 2980.79   424.7 2978.78
   443.3 2978.81   453.1 2977.03   459.3 2975.91   471.3 2975.73   479.3 2976.64
   499.3 2977.64   515.3 2976.18   539.3 2975.97   547.3 2977.28   551.3    2980
   554.4 2983.18   563.3 2994.24   567.3 2997.94   591.4 3016.34   607.4 3030.21
   611.4 3031.16   627.4 3032.12   643.4 3043.72   651.4 3047.16   666.6 3055.75
#Mann= 6 ,-1,0
       0      .1       0  313.24     .12       0  413.24      .1       0
   453.1    .045       0   479.3      .1       0  613.24     .06       0
Bank Sta=453.1,479.3
XS Rating Curve= 0 ,0
Exp/Cntr(USF)=0,0
Exp/Cntr=0.3,0.1

Type RM Length L Ch R = 1 ,12575   ,203.3,225.3,241.7
XS GIS Cut Line= 4
2317293.06546063594786.4025276982317203.36796013594937.330136527
2317170.20982049595349.4946669932317172.79274927595433.634625669
#Sta/Elev= 30
       0 2986.52    37.7 2986.86    54.4 2984.87    72.2 2985.84     172    2982
   191.5 2977.91   235.6  2978.8   255.7 2975.74   279.8 2976.11   295.8 2978.65
   307.8 2976.59   335.9 2977.04   351.4 2974.93     368 2972.66   384.1 2972.69
   391.6 2974.95   440.3 2975.34   484.4 2978.35   516.5 2978.68   532.6  2976.2
   552.6 2976.42   564.7 2974.75   580.7 2974.93   584.7    2977   588.7 2982.46
   592.8 2986.59   629.5 3018.55   648.6 3032.74   656.8 3035.78   673.2 3036.28
#Mann= 6 ,-1,0
       0      .1       0      40     .12       0     130      .1       0
   351.4    .045       0   391.6      .1       0  545.57     .06       0
Bank Sta=351.4,391.6
XS Rating Curve= 0 ,0
Exp/Cntr=0.3,0.1

Type RM Length L Ch R = 1 ,12350   ,123.1,121.8,121.6
XS GIS Cut Line= 3
  2317252.098145594735.9072851422316776.58151792595280.269753852
2316720.54420497595432.371031874
#Sta/Elev= 30
       0 2986.49    42.4 2985.33      76 2985.86   198.2 2982.01   206.6 2982.61
   230.1 2980.59   279.6 2980.55     315 2978.51     331 2971.44   336.3 2970.73
   372.2 2971.29   389.2 2973.87   409.1 2974.53   434.6 2973.16   447.8 2975.19
   463.8 2972.62   492.4 2974.96   508.3 2973.96   617.8 2976.67   660.3  2975.7
   711.3 2972.45   720.9 2974.81   753.6 2987.11     792 2992.75   800.5 2994.96
   817.6 3001.67   834.6 3013.08   847.4 3014.74   868.7 3014.35   884.9 3016.61
#Mann= 5 ,-1,0
       0     .12       0     220      .1       0     331    .045       0
   372.2      .1       0   732.8     .06       0
Bank Sta=331,372.2
XS Rating Curve= 0 ,0
Exp/Cntr(USF)=0,0
Exp/Cntr=0.3,0.1

Type RM Length L Ch R = 1 ,12228   ,328.9,349.7,353.8
XS GIS Cut Line= 3
2317147.04703615594627.0285336242317087.45578426594733.059281913
2316581.04279203 595332.99899793
#Sta/Elev= 30
       0 2988.58    98.8  2985.9   174.1 2979.63   244.5 2979.45   268.8 2977.97
   284.1 2979.38   288.7 2978.39     300  2972.2   312.8 2973.64   334.1 2972.26
   352.1 2970.77     381  2971.9     412 2974.32   430.6 2972.81   449.2 2973.88
     462 2971.29   477.7 2973.09   509.1 2971.69   524.8 2973.54   535.6 2972.17
   577.2 2972.39     598 2974.47   626.5 2973.12   660.5 2974.85   717.3 2971.23
   771.2 2977.24   827.5    2977   880.8 2993.31   896.5 3002.16   906.7  3003.5
#Mann= 4 ,-1,0
       0     .12       0   334.1    .045       0     381      .1       0
  851.63     .06       0
Bank Sta=334.1,381
XS Rating Curve= 0 ,0
Exp/Cntr(USF)=0,0
Exp/Cntr=0.3,0.1

Type RM Length L Ch R = 1 ,11878   ,276.1,281.3,284.1
XS GIS Cut Line= 3
2317054.20809513594469.8548544382316361.31194023594931.785624375
2316195.01686305595183.075963221
#Sta/Elev= 30
       0 2990.28     113 2981.33   165.9 2979.41   175.5  2977.9   194.7 2971.01
   209.2 2968.93     238 2972.14   287.2 2968.34   315.4 2972.13   347.1 2970.89
     363 2968.92   373.1 2970.97   382.2 2972.93   517.3 2970.84   550.5 2971.89
   569.2 2970.91   590.1 2967.12   618.9 2967.51   640.6 2970.86   699.5 2970.37
   728.4 2969.72   755.9 2966.41   766.8 2969.29   813.6 2973.58   944.3 2975.17
   972.5 2973.09  1079.1 2973.55  1094.4  2974.8  1108.8 2981.32  1134.1 2982.41
#Mann= 9 ,-1,0
       0      .1       0      60     .12       0     100      .1       0
     220     .12       0     240      .1       0   347.1    .045       0
   373.1      .1       0     770     .12       0  972.76      .1       0
Bank Sta=347.1,373.1
XS Rating Curve= 0 ,0
Exp/Cntr(USF)=0,0
Exp/Cntr=0.3,0.1

Type RM Length L Ch R = 1 ,11597   ,242.7,235.3,224.7
XS GIS Cut Line= 3
2316896.43104169594318.8594068742316297.13410012594634.033313807
2315886.04638353594917.469218501
#Sta/Elev= 30
       0 2987.94    95.2  2975.5   108.5 2970.06   126.8 2966.27   168.3  2969.3
   238.9 2967.44   253.4 2969.03   266.9 2967.44   298.6 2969.49   348.3 2967.53
   370.9 2965.47     381 2967.79   402.5 2970.09     458 2969.72   506.5 2968.45
   524.5  2965.7   556.2 2970.71   628.5 2971.36   700.2 2968.98   746.3 2970.69
   799.8 2968.35     887 2967.32     982 2968.41   999.8 2964.12  1023.2 2964.41
  1049.1 2970.58  1071.8 2970.32  1110.7 2967.34  1149.6 2968.06  1176.4 2972.25
#Mann= 10 ,-1,0
       0      .1       0      20     .12       0     140      .1       0
     190     .12       0     250      .1       0   348.3    .045       0
     381      .1       0  967.12     .12       0 1047.12      .1       0
 1137.12     .06       0
#XS Ineff= 2 , 0
                         1057.39         2977.99
Permanent Ineff=
       F       F
Bank Sta=348.3,381
XS Rating Curve= 0 ,0
Exp/Cntr(USF)=0,0
Exp/Cntr=0.3,0.1