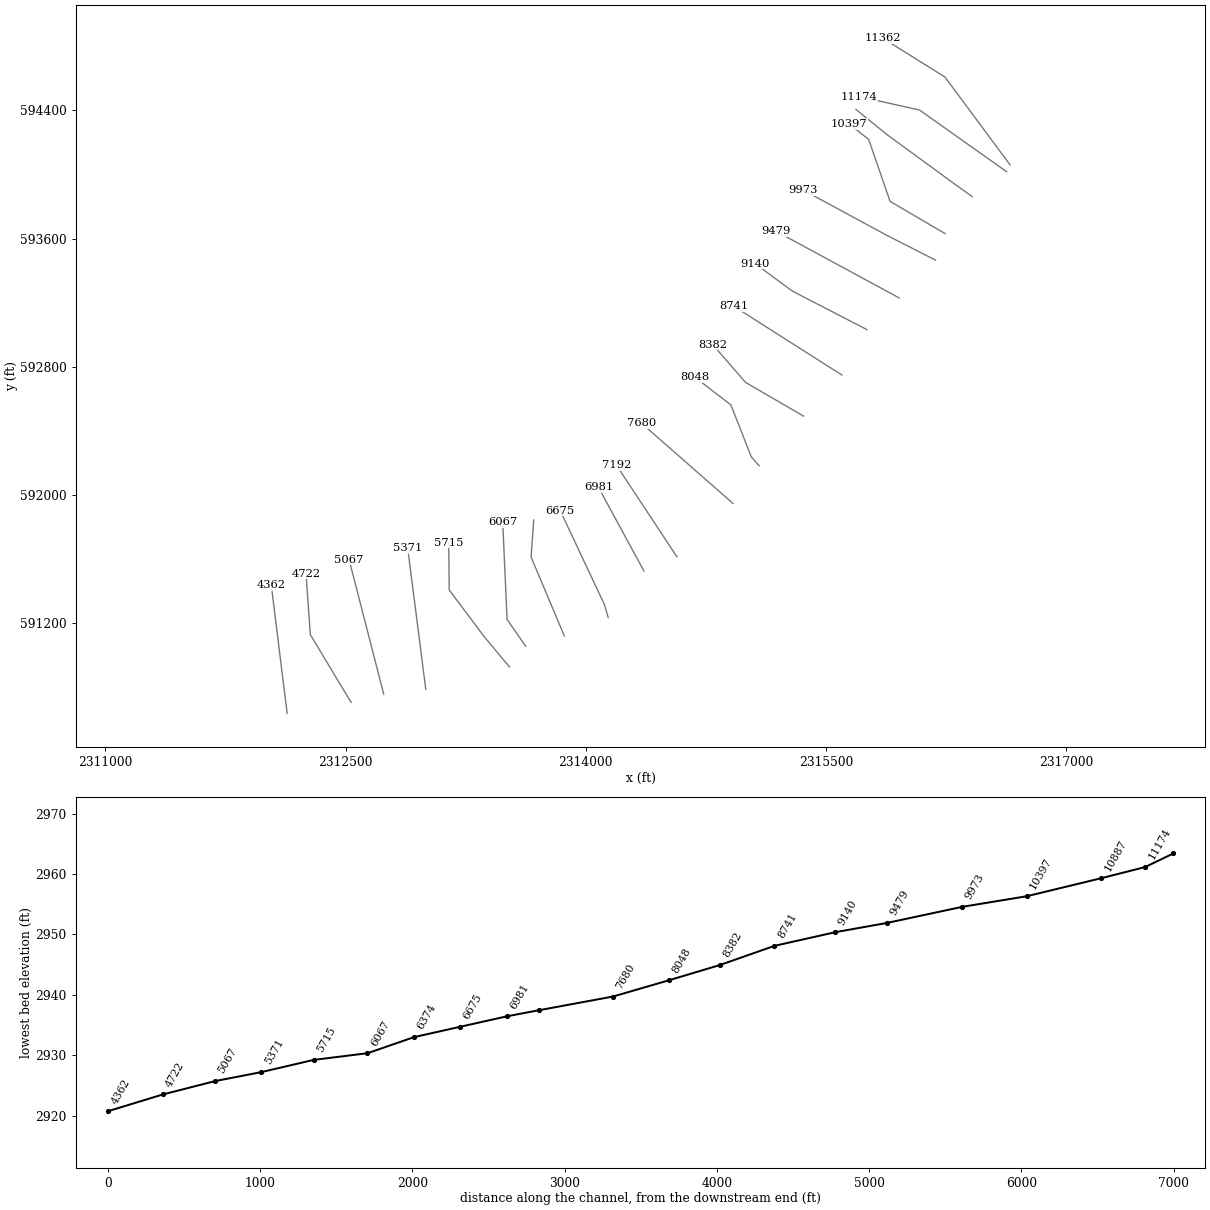
HEC-RAS study LTTLRV1.prj: LTTLRV1

--- LTTLRV1.g01 (geometry) --- (continued)

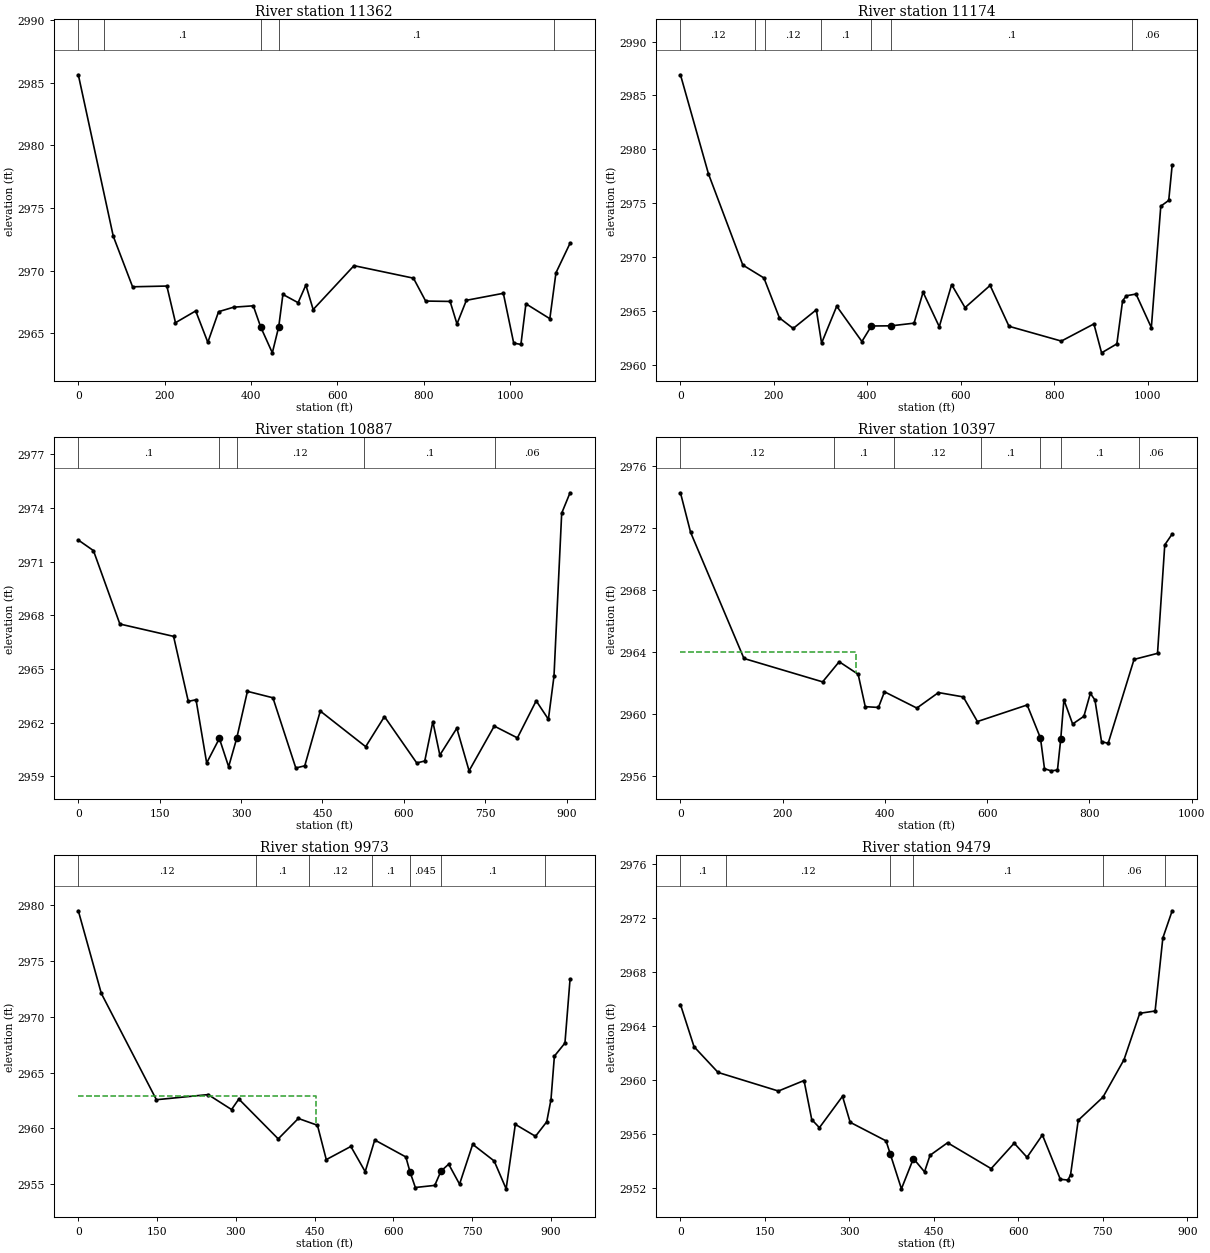
Type RM Length L Ch R = 1 ,11362   ,178.1,187.3,197.1
XS GIS Cut Line= 3
2316650.08485935594060.1843394082316243.36660842594608.798420717
2315856.46065444594850.328286541
#Sta/Elev= 30
       0 2985.65    80.9 2972.75   125.7  2968.7   205.1 2968.76   225.1 2965.83
   271.9 2966.77     300 2964.26   324.9 2966.71   359.8 2967.07   405.3 2967.18
   422.4 2965.49   449.4 2963.42   464.3 2965.52   473.9 2968.09   509.1 2967.43
   527.1 2968.84     544 2966.88   638.6 2970.39   776.3 2969.39   804.5 2967.56
   861.2 2967.53   877.1 2965.73   898.9 2967.62   984.5 2968.18  1008.5  2964.2
  1025.2 2964.09  1036.8 2967.34  1092.2 2966.15  1106.4 2969.82    1139 2972.18
#Mann= 5 ,-1,0
       0     .12       0      60      .1       0   422.4    .045       0
   464.3      .1       0 1102.93     .06       0
Bank Sta=422.4,464.3
XS Rating Curve= 0 ,0
Exp/Cntr=0.3,0.1

Type RM Length L Ch R = 1 ,11174   ,283.8,287.6,284.6
XS GIS Cut Line= 3
2316629.06460835594017.1487898962316084.87828418594402.424510115
2315708.65954884594486.811972683
#Sta/Elev= 30
       0 2986.92    59.9 2977.74   133.4 2969.29   178.6 2968.09   211.8 2964.39
   241.2 2963.41   290.8 2965.14     302 2962.05   334.4 2965.47   388.3  2962.2
   408.62963.638   450.92963.654   499.9  2963.9   519.2 2966.77   553.9 2963.57
   580.3 2967.47     609 2965.34   662.7  2967.4   703.1 2963.61   815.1 2962.24
   884.8 2963.83   901.2 2961.15   933.9 2961.98   946.2 2965.98   954.4 2966.44
   974.9  2966.6  1007.7 2963.49  1027.9 2974.74  1044.9 2975.28  1052.3 2978.56
#Mann= 7 ,-1,0
       0     .12       0     160      .1       0     180     .12       0
     300      .1       0   408.6    .045       0   450.9      .1       0
  966.77     .06       0
Bank Sta=408.6,450.9
XS Rating Curve= 0 ,0
Exp/Cntr=0.3,0.1

Type RM Length L Ch R = 1 ,10887   ,503.8,489.5,479.6
XS GIS Cut Line= 4
2316412.66683738593862.7199359552316285.34393541593953.999303818
2315881.02332337594249.4095743612315687.73855517594406.310827401
#Sta/Elev= 30
       0  2972.2    27.9 2971.61    76.6 2967.51   175.6 2966.82   202.7 2963.19
     217 2963.28   236.6 2959.75     260 2961.12   277.1 2959.54   291.9 2961.12
   311.7 2963.75   358.7 2963.39   400.9 2959.47   417.4 2959.59     446 2962.65
   529.7 2960.66   564.3 2962.34   623.8 2959.75   638.6 2959.86   653.5 2962.06
   666.4 2960.19   697.7 2961.69   720.3 2959.31   766.7 2961.81   809.4 2961.15
     844 2963.22   866.5 2962.19   876.8 2964.59     891  2973.7   906.4 2974.84
#Mann= 5 ,-1,0
       0      .1       0     260    .045       0   291.9     .12       0
  526.66      .1       0   767.4     .06       0
Bank Sta=260,291.9
XS Rating Curve= 0 ,0
Exp/Cntr(USF)=0,0
Exp/Cntr=0.3,0.1

Type RM Length L Ch R = 1 ,10397   ,403.2,424.1,447
XS GIS Cut Line= 4
2316244.10070629593631.1513887272315900.62092668593832.352124171
2315767.39551302 594218.54618245 2315645.7247372594315.011913638
#Sta/Elev= 30
       0 2974.27    19.8 2971.72   124.2 2963.58   278.1 2962.07   310.5 2963.37
   347.6 2962.56   361.5 2960.47   387.3 2960.42   399.1 2961.43   462.4 2960.38
   504.7 2961.38   553.2  2961.1   580.9 2959.51   678.2 2960.58   704.2 2958.45
   712.1 2956.47   724.8 2956.33   737.5 2956.38   743.9 2958.38   750.1 2960.91
   767.2 2959.35   789.2 2959.85   801.8 2961.33   810.8  2960.9   823.7 2958.22
   836.6  2958.1   887.3 2963.52   933.2 2963.91   947.4 2970.91   961.9 2971.61
#Mann= 7 ,-1,0
       0     .12       0     300      .1       0  418.07     .12       0
  588.07      .1       0   704.2    .045       0   743.9      .1       0
   896.6     .06       0
#XS Ineff= 2 , 0
          344.26 2963.99
Permanent Ineff=
       F       F
Bank Sta=704.2,743.9
XS Rating Curve= 0 ,0
Exp/Cntr(USF)=0,0
Exp/Cntr=0.3,0.1

Type RM Length L Ch R = 1 ,9973    ,452.9,493.8,466.1
XS GIS Cut Line= 3
2316184.68573007593465.313271167 2315882.6028873 593618.90531287
2315357.18508909593903.332553008
#Sta/Elev= 30
       0  2979.5    43.8 2972.09   148.7 2962.56   247.2 2963.02   291.8 2961.68
   305.7 2962.62   380.7 2959.05     419 2960.88   455.4 2960.27   472.2 2957.19
     519 2958.37   546.3 2956.11   564.5 2958.95   623.7 2957.43   631.6  2956.1
   641.8 2954.69   678.8 2954.88   690.6 2956.16   705.3 2956.78     726 2954.99
     751 2958.56   791.9 2957.07   814.7 2954.57   832.2 2960.35   870.6 2959.28
     892 2960.58   900.1 2962.57   906.6 2966.47   926.7 2967.64   936.4 2973.36
#Mann= 7 ,-1,0
       0     .12       0  338.89      .1       0  438.89     .12       0
  558.89      .1       0   631.6    .045       0   690.6      .1       0
  888.89     .06       0
#XS Ineff= 2 , 0
          453.55 2962.87
Permanent Ineff=
       F       F
Bank Sta=631.6,690.6
XS Rating Curve= 0 ,0
Exp/Cntr=0.3,0.1

Type RM Length L Ch R = 1 ,9479    ,333,338.9,332.1
XS GIS Cut Line= 2
2315957.07680929593229.3484668572315189.53482061593645.383435951
#Sta/Elev= 30
       0 2965.59    24.1 2962.46    66.8 2960.55   173.9 2959.17   219.4 2959.95
   233.1 2957.05   246.7 2956.45   287.7 2958.78   301.3 2956.85     365 2955.47
   372.3 2954.52   392.3 2951.91   413.6 2954.16   433.3 2953.17   443.1  2954.4
   474.2 2955.33   551.6 2953.41   592.5  2955.3   615.3 2954.25   642.6 2955.91
   674.4 2952.62     688 2952.56   692.6 2952.96   706.2    2957     750 2958.71
   787.5  2961.5   815.4 2964.94   842.7 2965.11   856.4 2970.53     873 2972.55
#Mann= 6 ,-1,0
       0      .1       0      80     .12       0   372.3    .045       0
   413.6      .1       0     750     .06       0     860      .1       0
Bank Sta=372.3,413.6
XS Rating Curve= 0 ,0
Exp/Cntr=0.3,0.1

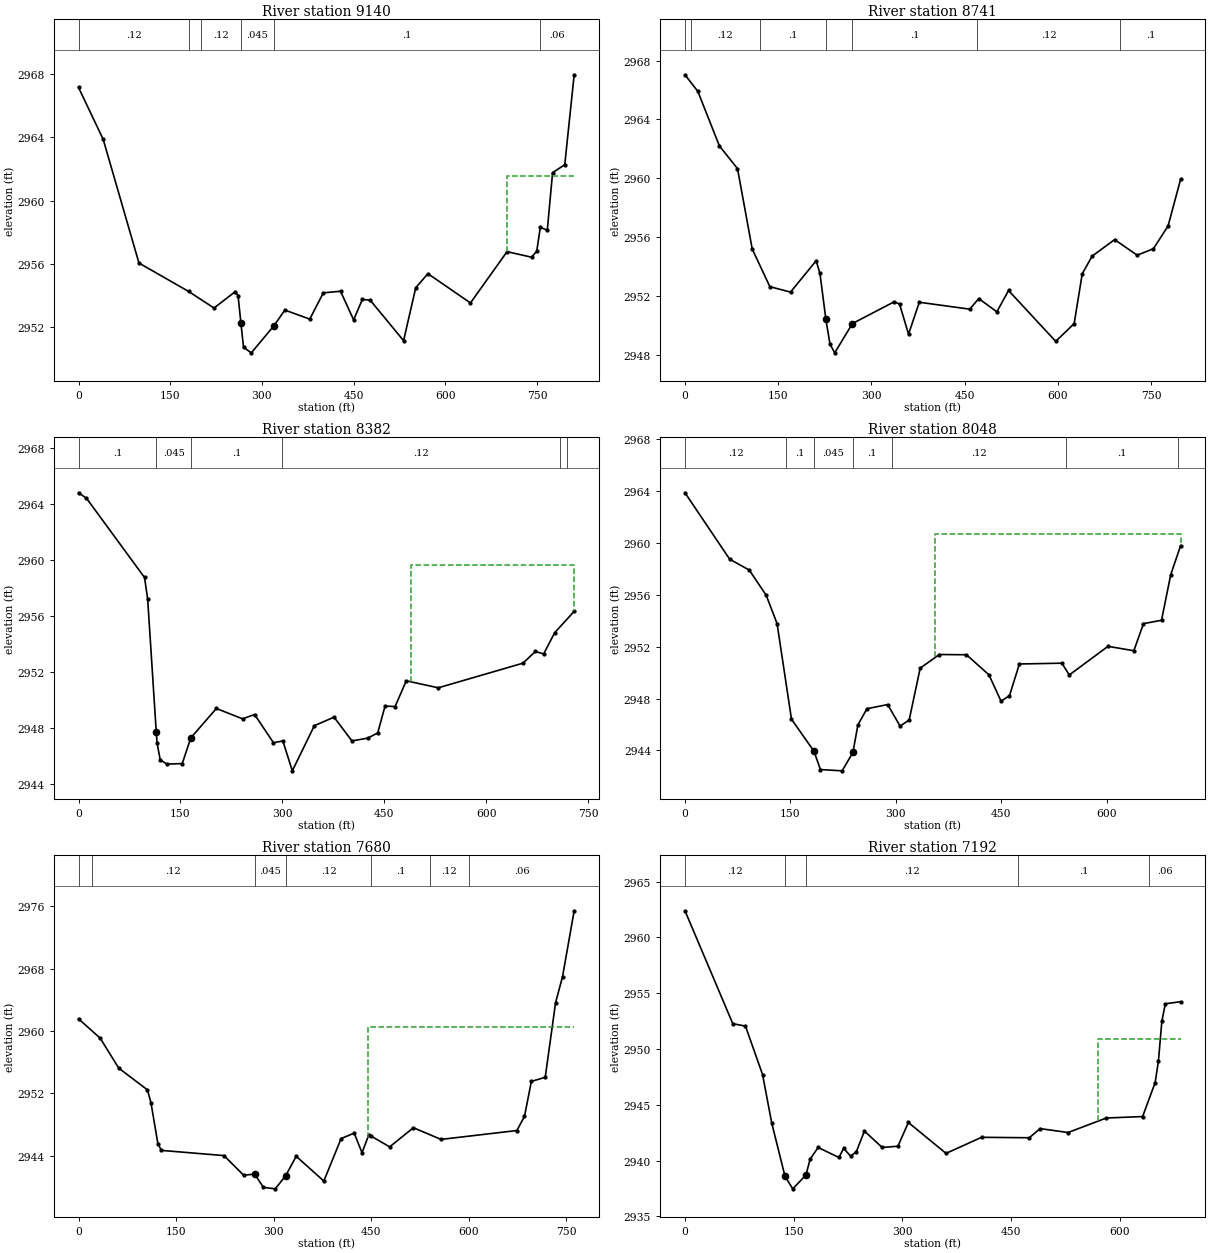
Type RM Length L Ch R = 1 ,9140    ,392.3,399.6,388.1
XS GIS Cut Line= 3
2315756.07043858 593031.408259442315289.86022768593272.257493114
2315059.59067526593442.178350511
#Sta/Elev= 30
       0 2967.14    40.4 2963.86    98.9 2956.05     180 2954.26   221.7 2953.21
   256.6 2954.25     261    2954   265.7 2952.26     270 2950.73   282.7 2950.38
   319.5 2952.08   337.6 2953.08   378.3 2952.51   400.6 2954.17   428.7 2954.27
   450.1 2952.46   464.3 2953.75   477.1 2953.71   531.8 2951.15   551.7 2954.49
   571.6 2955.38   641.2 2953.53   701.1 2956.77   741.1 2956.42   749.7  2956.8
   755.5 2958.31   766.9 2958.12   775.6 2961.76   795.5 2962.26   810.9 2967.94
#Mann= 6 ,-1,0
       0     .12       0     180      .1       0     200     .12       0
   265.7    .045       0   319.5      .1       0  754.75     .06       0
#XS Ineff= 2 , 0
                          700.48         2961.55
Permanent Ineff=
       F       F
Bank Sta=265.7,319.5
XS Rating Curve= 0 ,0
Exp/Cntr=0.3,0.1

Type RM Length L Ch R = 1 ,8741    ,357.9,359.2,359.2
XS GIS Cut Line= 2
2315599.43015006 592747.916715342314926.53958949593176.040996336
#Sta/Elev= 30
       0 2967.03    20.7  2965.9    55.4 2962.19    84.5 2960.65   108.2 2955.18
   136.6 2952.62   169.8 2952.25     211 2954.38   217.2 2953.52   226.7 2950.39
   233.3 2948.72   240.9 2948.12   269.4 2950.11   336.5 2951.59   345.2 2951.44
   359.7 2949.39     377 2951.56   458.2 2951.09   472.7 2951.81   501.8 2950.91
   520.6 2952.36   596.5  2948.9   626.2 2950.11   639.2  2953.5   655.2  2954.7
   691.3 2955.82   727.6 2954.76   753.7  2955.2   777.3 2956.75   797.5 2959.93
#Mann= 7 ,-1,0
       0      .1       0      10     .12       0     120      .1       0
   226.7    .045       0   269.4      .1       0     470     .12       0
     700      .1       0
Bank Sta=226.7,269.4
XS Rating Curve= 0 ,0
Exp/Cntr(USF)=0,0
Exp/Cntr=0.3,0.1

Type RM Length L Ch R = 1 ,8382    ,356.7,333.2,308.3
XS GIS Cut Line= 3
2315360.12593254 592491.288509822314998.44766632592701.394347141
 2314794.7240052592936.144212237
#Sta/Elev= 30
       0 2964.83    11.7 2964.44    97.1 2958.77   101.7 2957.24   114.42947.688
   115.6 2946.91   120.2 2945.73   130.1 2945.42   152.6 2945.46   165.2  2947.3
   202.8  2949.4   241.3 2948.66     259 2948.97   286.8 2946.95   300.6 2947.08
   314.5 2944.94   346.9 2948.17   375.9 2948.78   402.2 2947.08   425.4 2947.28
   440.1 2947.65   450.9 2949.57   465.7 2949.54   482.1 2951.38   529.2 2950.88
   653.7 2952.64   672.1 2953.48   684.2  2953.3   700.4 2954.82   729.1 2956.35
#Mann= 6 ,-1,0
       0      .1       0   114.4    .045       0   165.2      .1       0
     300     .12       0  708.28      .1       0  718.28     .06       0
#XS Ineff= 2 , 0
                          489.28         2959.66
Permanent Ineff=
       F       F
Bank Sta=114.4,165.2
XS Rating Curve= 0 ,0
Exp/Cntr=0.3,0.1

Type RM Length L Ch R = 1 ,8048    ,349.7,368.1,384.7
XS GIS Cut Line= 4
2315083.03699464592181.6332118572315033.76437918592237.064904249
2314907.05976908592560.8453336192314682.26906846592733.772296246
#Sta/Elev= 30
       0 2963.87    63.6 2958.75    91.5 2957.91   115.6 2955.97   131.1 2953.78
   151.6 2946.41   183.5 2943.95   192.8 2942.53   223.7 2942.43   239.1 2943.86
   246.1 2945.97     259 2947.22   288.5 2947.54   306.2 2945.88   319.1 2946.35
   334.8 2950.35   362.1  2951.4   400.7 2951.38   432.7 2949.83   449.8 2947.81
   461.8 2948.21     476 2950.67   536.5 2950.73     547 2949.82   602.1 2952.03
   638.9 2951.69   652.6 2953.78   678.3 2954.04   691.4 2957.55   705.5  2959.8
#Mann= 7 ,-1,0
       0     .12       0  144.17      .1       0   183.5    .045       0
   239.1      .1       0  294.17     .12       0  541.85      .1       0
  701.85     .07       0
#XS Ineff= 2 , 0
                          356.33         2960.69
Permanent Ineff=
       F       F
Bank Sta=183.5,239.1
XS Rating Curve= 0 ,0
Exp/Cntr=0.3,0.1

Type RM Length L Ch R = 1 ,7680    ,489.5,488.3,482
XS GIS Cut Line= 2
2314919.93551291591945.8647607222314346.65978428592448.070317677
#Sta/Elev= 30
       0 2961.57    33.4 2959.08    61.7 2955.25     106 2952.44   111.4 2950.79
     122 2945.55   127.3 2944.67   223.6    2944   253.9 2941.48   270.9 2941.62
   284.3 2939.92   302.5 2939.73   318.7 2941.44   334.7 2943.91   377.2 2940.73
   403.8 2946.19   423.9 2946.89   435.9 2944.36   446.4 2946.69     450  2946.5
   478.4 2945.12   514.9 2947.58   557.4 2946.08     674 2947.22   685.7 2949.04
   696.3 2953.53   717.6 2954.06   733.5 2963.63   744.2 2966.99   762.1 2975.45
#Mann= 7 ,-1,0
       0      .1       0      20     .12       0   270.9    .045       0
   318.7     .12       0     450      .1       0     540     .12       0
     600     .06       0
#XS Ineff= 2 , 0
                          444.44         2960.56
Permanent Ineff=
       F       F
Bank Sta=270.9,318.7
XS Rating Curve= 0 ,0
Exp/Cntr(USF)=0,0
Exp/Cntr=0.3,0.1

Type RM Length L Ch R = 1 ,7192    ,212.9,210.7,208.7
XS GIS Cut Line= 2
2314570.18287482591611.8078706872314193.04286382592182.854774139
#Sta/Elev= 30
       0 2962.39      66 2952.27    83.5 2952.05   107.1 2947.71   119.8 2943.35
   138.1 2938.58   148.8 2937.46     167  2938.7   172.8 2940.12   183.8 2941.17
   212.6 2940.27     219 2941.09   228.6  2940.4   236.5 2940.77   247.8 2942.64
   272.2 2941.17     294 2941.28   308.4 2943.41   360.4 2940.64   409.5 2942.08
   475.4 2942.04   490.3 2942.86   528.9 2942.51   581.7 2943.81   631.8 2943.94
   649.1 2946.98   653.6 2948.89   658.4  2952.5   663.2 2954.05   684.3 2954.24
#Mann= 5 ,-1,0
       0     .12       0   138.1    .045       0     167     .12       0
     460      .1       0     640     .06       0
#XS Ineff= 2 , 0
                          570.63          2950.9
Permanent Ineff=
       F       F
Bank Sta=138.1,167
XS Rating Curve= 0 ,0
Exp/Cntr(USF)=0,0
Exp/Cntr=0.3,0.1

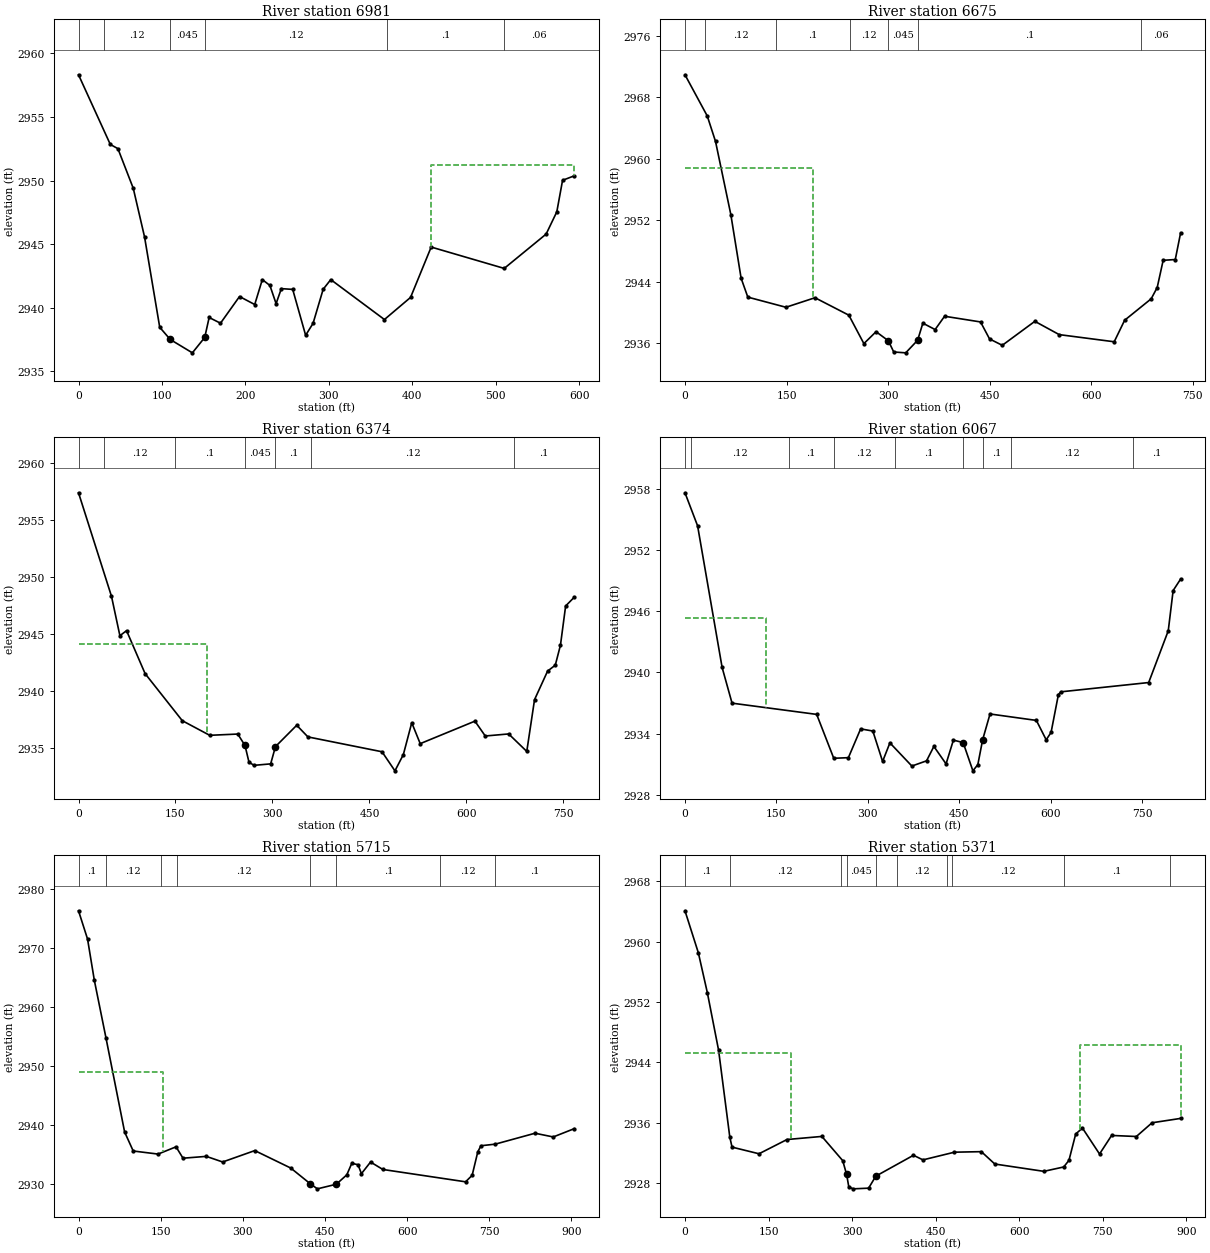
Type RM Length L Ch R = 1 ,6981    ,307.5,306.1,304.1
XS GIS Cut Line= 2
 2314363.6867692591523.6810510452314080.15043595592045.406102577
#Sta/Elev= 30
       0 2958.32    38.1 2952.84    47.2 2952.51    65.6 2949.39    79.1 2945.57
    97.3 2938.46   109.9  2937.5   136.4 2936.45   151.2 2937.66   156.5 2939.23
   170.1 2938.78   192.9 2940.88   211.1 2940.25   220.2 2942.21   229.3 2941.75
   236.7 2940.32     243  2941.5   256.6 2941.44   272.1 2937.83     281 2938.77
   293.1 2941.45   302.2 2942.21   366.5 2939.07   397.8 2940.81   422.5 2944.77
     510 2943.09   560.2 2945.79     573 2947.54   579.9 2950.02   593.8 2950.37
#Mann= 6 ,-1,0
       0      .1       0      30     .12       0   109.9    .045       0
   151.2     .12       0     370      .1       0     510     .06       0
#XS Ineff= 2 , 0
                          422.03         2951.26
Permanent Ineff=
       F       F
Bank Sta=109.9,151.2
XS Rating Curve= 0 ,0
Exp/Cntr=0.3,0.1

Type RM Length L Ch R = 1 ,6675    ,302.8,301.1,299.6
XS GIS Cut Line= 3
2314140.37274872591233.5828873972314117.09406697591314.138281781
2313840.96574374591900.510174344
#Sta/Elev= 30
       0  2970.9    32.9 2965.54    45.1 2962.23    67.7 2952.72    82.9 2944.43
    92.8 2941.97   149.1 2940.65     192 2941.89     242 2939.62   264.2 2935.92
   282.2 2937.47   300.32936.294   308.3 2934.83     326 2934.72   343.6 2936.36
   351.3 2938.58   369.4 2937.75   383.4 2939.48   436.5 2938.74   449.8 2936.53
   468.6  2935.7   516.7 2938.82   552.7 2937.09   633.9 2936.16   649.3 2938.96
   688.5 2941.75   697.4 2943.22   706.2 2946.76   724.1 2946.86     732 2950.34
#Mann= 7 ,-1,0
       0      .1       0      30     .12       0  133.85      .1       0
  243.85     .12       0   300.3    .045       0   343.6      .1       0
  673.85     .06       0
#XS Ineff= 2 , 0
          189.37 2958.73
Permanent Ineff=
       F       F
Bank Sta=300.3,343.6
XS Rating Curve= 0 ,0
Exp/Cntr=0.3,0.1

Type RM Length L Ch R = 1 ,6374    ,324.9,306.8,293.5
XS GIS Cut Line= 3
2313866.51106701591118.2230718752313659.01933626591610.406356929
2313675.16907698591842.325216565
#Sta/Elev= 30
       0 2957.36      51  2948.3      64 2944.85    74.3 2945.29     103 2941.53
   160.5 2937.41   202.9 2936.13   246.3 2936.24   257.5 2935.24   263.6 2933.79
   271.3  2933.5   297.2 2933.63   304.6 2935.14   337.5 2937.01   354.8 2935.99
   469.4 2934.69   489.4 2933.02   502.4 2934.44   515.4 2937.23   528.5  2935.4
   613.1 2937.37   629.1 2936.07   665.3 2936.25   693.3 2934.72   705.3 2939.25
   725.5 2941.75   737.4 2942.27   745.4 2944.02   753.4 2947.45   766.6 2948.21
#Mann= 7 ,-1,0
       0      .1       0      40     .12       0     150      .1       0
   257.5    .045       0   304.6      .1       0     360     .12       0
  674.13      .1       0
#XS Ineff= 2 , 0
          198.65 2944.13
Permanent Ineff=
       F       F
Bank Sta=257.5,304.6
XS Rating Curve= 0 ,0
Exp/Cntr(USF)=0,0
Exp/Cntr=0.3,0.1

Type RM Length L Ch R = 1 ,6067    ,336.1,352.6,363.7
XS GIS Cut Line= 3
2313625.52472314591053.7835642942313508.89453005 591221.40814075
2313481.76925656591829.457307608
#Sta/Elev= 30
       0 2957.59    20.7 2954.35    60.9 2940.48    77.2 2936.98     216 2935.88
     244 2931.58     268 2931.64   288.1 2934.46   308.1 2934.25   324.1 2931.27
   336.1 2933.09   372.1 2930.82   396.2 2931.33   408.2 2932.74   428.2 2931.03
   440.2 2933.36   456.2 2933.12   472.2 2930.35   480.3 2930.96   488.2  2933.4
   500.3 2935.92   576.3 2935.29   592.4 2933.39   600.4 2934.11   612.4 2937.81
   616.4 2938.09   760.5    2939   792.6 2944.07   800.6 2948.01   812.9 2949.14
#Mann= 9 ,-1,0
       0      .1       0      10     .12       0     170      .1       0
  244.21     .12       0  344.21      .1       0   456.2    .045       0
   488.2      .1       0  534.21     .12       0  734.21      .1       0
#XS Ineff= 2 , 0
          132.37 2945.36
Permanent Ineff=
       F       F
Bank Sta=456.2,488.2
XS Rating Curve= 0 ,0
Exp/Cntr=0.3,0.1

Type RM Length L Ch R = 1 ,5715    ,361.2,343.6,324.3
XS GIS Cut Line= 4
2313524.23506853590924.520520648 2313366.2071929591113.724351944
 2313147.5878369591405.2406608892313144.68415099591699.430175843
#Sta/Elev= 30
       0 2976.36    16.5 2971.57    28.9 2964.58      50 2954.89    84.2 2938.88
    99.9 2935.66   145.3 2935.14   178.1 2936.37   190.8 2934.44   233.4 2934.75
   263.2  2933.8   321.9 2935.73   387.6 2932.77   423.2 2930.11   436.2 2929.25
   470.8 2930.03   489.9 2931.62     499 2933.57   510.4 2933.34   516.6 2931.82
   533.3 2933.79   555.8 2932.53   706.8 2930.44   718.8 2931.54   729.1 2935.51
   734.8 2936.55   760.9 2936.82   833.6 2938.67   866.9 2938.04   905.1 2939.44
#Mann= 8 ,-1,0
       0      .1       0      50     .12       0     150      .1       0
     180     .12       0   423.2    .045       0   470.8      .1       0
   660.9     .12       0   760.9      .1       0
#XS Ineff= 2 , 0
          154.59 2949.13
Permanent Ineff=
       F       F
Bank Sta=423.2,470.8
XS Rating Curve= 0 ,0
Exp/Cntr(USF)=0,0
Exp/Cntr=0.3,0.1

Type RM Length L Ch R = 1 ,5371    ,301.6,304.3,308.8
XS GIS Cut Line= 2
2313001.32877901590785.3583237092312888.13957899591667.986600361
#Sta/Elev= 30
       0  2964.1      24 2958.53    40.1 2953.26    60.3 2945.63    80.5 2934.08
    84.5 2932.76   132.9 2931.88   183.2 2933.77   245.8 2934.18   283.2 2930.97
   290.2 2929.14   294.2 2927.46   302.3 2927.23   329.7 2927.32   342.6 2928.91
   410.2 2931.68   427.3 2931.07   483.8 2932.09   532.1 2932.16   556.3 2930.52
   644.3 2929.55     680 2930.13   689.4 2931.01   701.5  2934.5   713.6 2935.29
   744.3 2931.85     766 2934.31   810.4 2934.17   838.6 2935.99   889.9 2936.57
#Mann= 10 ,-1,0
       0      .1       0      80     .12       0     280      .1       0
   290.2    .045       0   342.6      .1       0     380     .12       0
     470      .1       0     480     .12       0     680      .1       0
     870     .08       0
#XS Ineff= 2 , 0
          190.34 2945.21  709.18         2946.26
Permanent Ineff=
       F       F
Bank Sta=290.2,342.6
XS Rating Curve= 0 ,0
Exp/Cntr=0.3,0.1

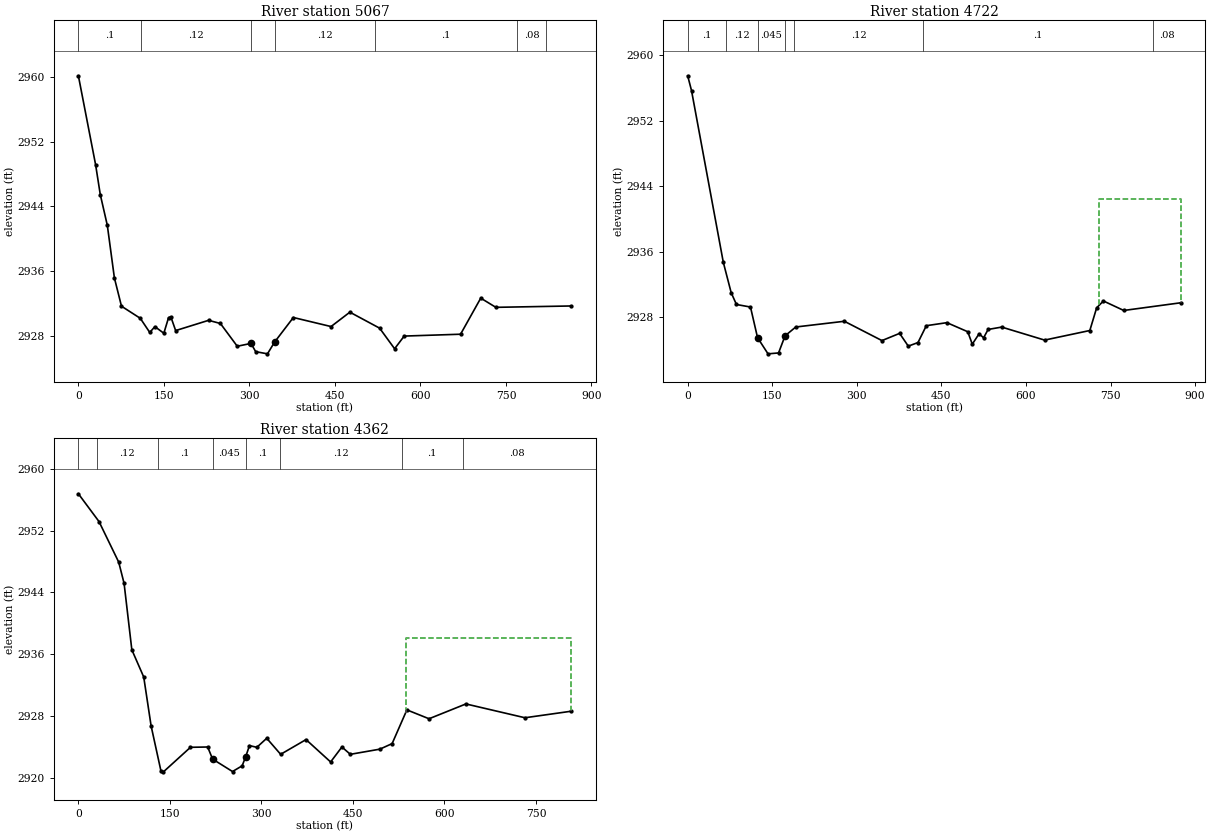
Type RM Length L Ch R = 1 ,5067    ,340.6,344.4,354.1
XS GIS Cut Line= 2
2312738.34125351590755.9663666062312522.77356087591593.600829421
#Sta/Elev= 30
       0 2960.18    30.2 2949.17    38.4 2945.47    50.8 2941.64    63.2 2935.13
    75.6 2931.64   108.6 2930.14   125.2 2928.39   134.2 2929.11   149.9 2928.29
   158.2 2930.23   162.3  2930.3   170.6 2928.62   228.4 2929.89   249.1  2929.5
   278.7 2926.68   302.8 2927.03     311 2926.01   331.7 2925.74   344.1 2927.19
   377.1 2930.24   443.2 2929.12   476.2  2930.9   528.4 2928.92   554.7 2926.37
   571.5 2927.94   670.4 2928.17   705.8 2932.64   732.3  2931.5   864.9 2931.67
#Mann= 7 ,-1,0
       0      .1       0     110     .12       0   302.8    .045       0
   344.1     .12       0     520      .1       0     770     .08       0
     820     .07       0
Bank Sta=302.8,344.1
XS Rating Curve= 0 ,0
Exp/Cntr(USF)=0,0
Exp/Cntr=0.3,0.1

Type RM Length L Ch R = 1 ,4722    ,376.9,360,350.1
XS GIS Cut Line= 4
2312535.57904284590703.4097459592312499.93623652590761.241197216
2312280.22371322591126.9078758362312253.61650087591506.060651798
#Sta/Elev= 30
       0  2957.5     6.8 2955.69    63.2  2934.7    77.2 2930.98    86.5 2929.55
   111.4 2929.24   123.9  2925.5   142.5 2923.52   161.2 2923.63   172.7 2925.72
   191.7  2926.8   277.9  2927.5   344.6 2925.14   375.9 2926.02   391.3 2924.46
   408.5  2924.9   423.3 2926.96   459.8 2927.33   496.8 2926.22   504.8  2924.7
   516.9 2925.97   524.9 2925.48   532.9  2926.5     557 2926.79   633.1  2925.2
   713.3 2926.37   725.4 2929.14   737.4 2929.98   773.5 2928.82   874.6 2929.76
#Mann= 7 ,-1,0
       0      .1       0   67.93     .12       0   123.9    .045       0
   172.7      .1       0  187.93     .12       0  417.93      .1       0
  824.53     .08       0
#XS Ineff= 2 , 0
                          730.43         2942.43
Permanent Ineff=
       F       F
Bank Sta=123.9,172.7
XS Rating Curve= 0 ,0
Exp/Cntr(USF)=0,0
Exp/Cntr=0.3,0.1

Type RM Length L Ch R = 1 ,4362    ,241.6,243,237.7
XS GIS Cut Line= 2
2312135.56441212590634.8577080712312036.34822811591436.857051411
#Sta/Elev= 30
       0 2956.79    33.8 2953.19    66.1 2947.93    74.9 2945.18    87.6 2936.57
   107.1 2933.04   119.2  2926.7   135.3 2920.87   139.4 2920.75   183.7 2923.93
   211.9 2923.97     220  2922.4   252.6 2920.79   268.4 2921.53   274.1 2922.69
   280.4 2924.15   292.5 2923.93   308.7  2925.1   331.5 2923.02   373.1 2924.93
   413.4 2922.03   431.9 2923.97   445.7 2923.02   494.1 2923.69   514.2 2924.41
   538.4 2928.78   574.7 2927.63   635.1 2929.55   731.9 2927.76   808.1 2928.61
#Mann= 8 ,-1,0
       0      .1       0      30     .12       0     130      .1       0
     220    .045       0   274.1      .1       0     330     .12       0
     530      .1       0     630     .08       0
#XS Ineff= 2 , 0
                          536.23         2938.06
Permanent Ineff=
       F       F
Bank Sta=220,274.1
XS Rating Curve= 0 ,0
Exp/Cntr=0.3,0.1