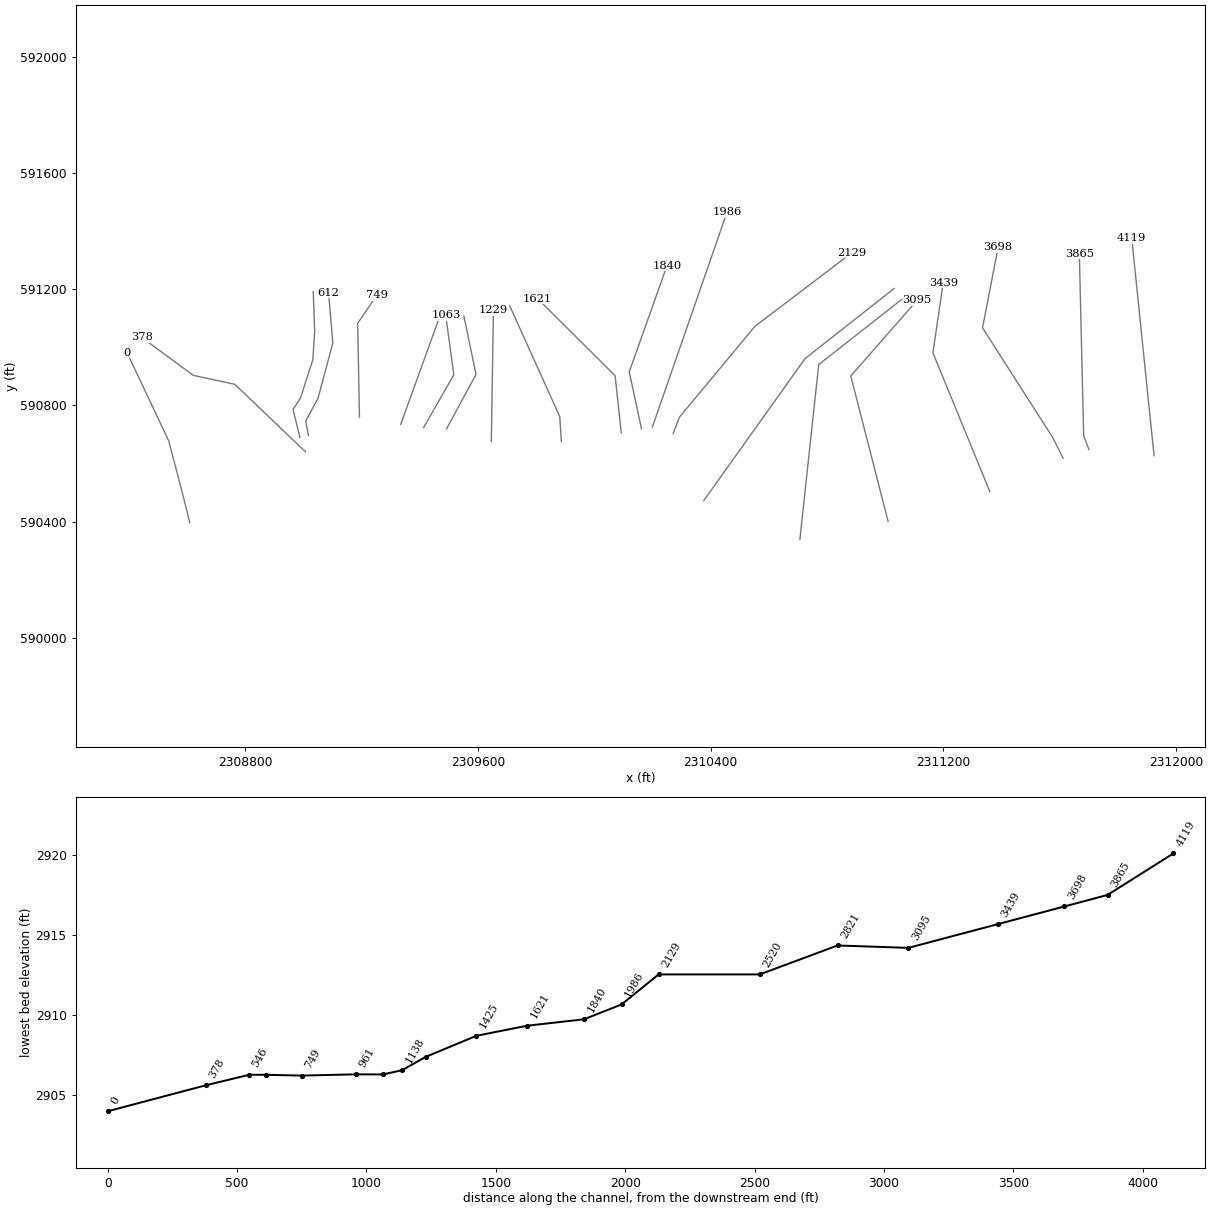
HEC-RAS study LTTLRV1.prj: LTTLRV1

--- LTTLRV1.g01 (geometry) --- (continued)

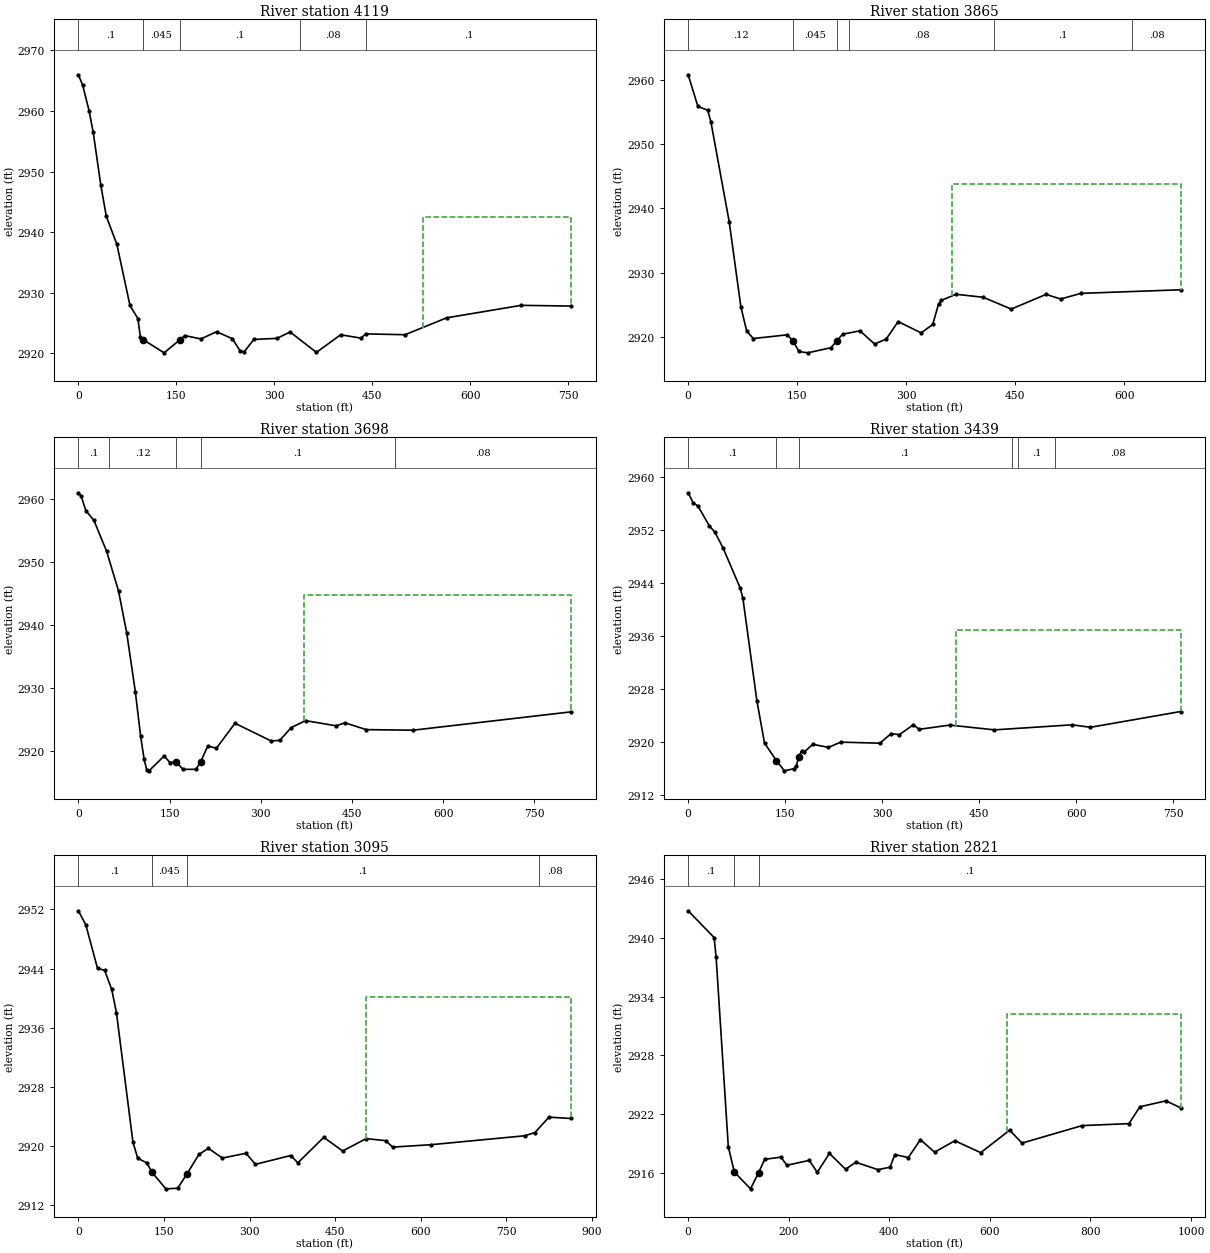
Type RM Length L Ch R = 1 ,4119    ,253.4,254.9,248
XS GIS Cut Line= 2
2311924.16751876590626.5829146172311847.29539523591376.998004646
#Sta/Elev= 30
       0 2965.99     6.6 2964.28    16.4 2960.06    22.7 2956.53    34.3 2947.82
    42.8 2942.63    58.9 2938.03      79 2927.93    91.1 2925.76    95.1 2922.64
    99.1 2922.28   131.3  2920.1   155.2 2922.23   162.8 2922.95   187.6  2922.4
   211.7 2923.58   235.8 2922.44   247.9 2920.38     254 2920.27   268.6 2922.31
   304.2 2922.49   324.3 2923.54   364.5 2920.17   401.6 2923.08   432.8 2922.53
     440 2923.23   500.2 2923.09     564 2925.88   678.1 2927.94   754.3 2927.82
#Mann= 5 ,-1,0
       0      .1       0    99.1    .045       0   155.2      .1       0
     340     .08       0     440      .1       0
#XS Ineff= 2 , 0
                          527.15         2942.57
Permanent Ineff=
       F       F
Bank Sta=99.1,155.2
XS Rating Curve= 0 ,0
Exp/Cntr(USF)=0,0
Exp/Cntr=0.3,0.1

Type RM Length L Ch R = 1 ,3865    ,148.5,166.9,186.2
XS GIS Cut Line= 3
 2311700.2331565590647.9811184682311682.24227404 590695.72710486
 2311667.3412437591322.488905897
#Sta/Elev= 30
       0 2960.84    13.4  2955.9    26.9 2955.32    31.2 2953.55    56.5  2937.9
    72.5  2924.7    80.5 2920.91    89.6 2919.73   136.5 2920.31   144.5  2919.3
   152.5 2917.71   164.5  2917.5   196.5  2918.3   204.5 2919.36   212.5  2920.4
   236.5 2920.93   256.5 2918.88   272.5 2919.64     289 2922.37   320.6 2920.61
   336.6 2921.92   344.6 2925.11   348.6 2925.68   368.6 2926.63   406.2 2926.16
   444.6 2924.32   492.6 2926.61   512.6 2925.89   540.6 2926.77     678 2927.33
#Mann= 6 ,-1,0
       0     .12       0   144.5    .045       0   204.5     .12       0
  221.02     .08       0  421.02      .1       0  611.02     .08       0
#XS Ineff= 2 , 0
                          362.51         2943.79
Permanent Ineff=
       F       F
Bank Sta=144.5,204.5
XS Rating Curve= 0 ,0
Exp/Cntr=0.3,0.1

Type RM Length L Ch R = 1 ,3698    ,262.1,258.2,252.4
XS GIS Cut Line= 4
2311611.58959422590618.1968543522311575.23705702590690.287365517
2311334.65677666 591067.309826452311388.07438816591344.255327568
#Sta/Elev= 30
       0 2961.05     4.8 2960.48    12.3 2958.21    25.6 2956.65    46.5 2951.72
    66.1  2945.4    79.5 2938.76    93.7 2929.36   102.4 2922.28   108.2 2918.59
   112.6 2916.87   116.2 2916.78   141.1 2919.15   150.6  2918.1   160.8 2918.24
   171.9 2917.02   193.3 2917.02   200.9 2918.18   212.8 2920.73     227 2920.38
   257.5 2924.35   316.9 2921.54   331.3 2921.64   349.9 2923.66   373.6 2924.77
     424 2923.95   438.4 2924.43   473.3 2923.34   550.3 2923.25     810 2926.17
#Mann= 5 ,-1,0
       0      .1       0      50     .12       0   160.8    .045       0
   200.9      .1       0  520.74     .08       0
#XS Ineff= 2 , 0
                          371.01         2944.81
Permanent Ineff=
       F       F
Bank Sta=160.8,200.9
XS Rating Curve= 0 ,0
Exp/Cntr=0.3,0.1

Type RM Length L Ch R = 1 ,3439    ,348.3,344.6,340.2
XS GIS Cut Line= 3
2311359.80001864590502.8842173952311164.14667475590981.239192482
2311199.52277023591223.376280734
#Sta/Elev= 30
       0 2957.61     7.6 2956.12    15.4 2955.57    32.7 2952.62    41.4 2951.65
    54.3 2949.21    80.3 2943.27    84.6 2941.69   106.2 2926.25     118 2919.86
   136.5 2917.21   148.7 2915.67     164    2916   167.1  2916.4     171 2917.83
   175.3 2918.65   179.7 2918.54   192.6 2919.67   216.9 2919.21   235.8    2920
   296.4 2919.84   313.6 2921.28   326.6 2921.13   348.2 2922.63   356.9 2921.93
   404.4 2922.57   473.5 2921.85   593.6 2922.61   621.9 2922.24   761.5 2924.62
#Mann= 6 ,-1,0
       0      .1       0   136.5    .045       0     171      .1       0
     500     .08       0     510      .1       0  566.82     .08       0
#XS Ineff= 2 , 0
                           414.3         2936.94
Permanent Ineff=
       F       F
Bank Sta=136.5,171
XS Rating Curve= 0 ,0
Exp/Cntr(USF)=0,0
Exp/Cntr=0.3,0.1

Type RM Length L Ch R = 1 ,3095    ,284.1,273.8,262.7
XS GIS Cut Line= 3
2311010.13166048590400.6104885122310881.81755772590901.343443121
2311109.70340422591162.077699928
#Sta/Elev= 30
       0 2951.82      13 2949.94    33.6 2944.02      46 2943.77    58.4 2941.19
    66.7 2938.05    95.6 2920.54     104 2918.33   120.3 2917.69   128.6 2916.46
   153.4 2914.19     174 2914.27   190.5 2916.23   211.2 2918.84   227.7 2919.67
   252.5 2918.36   293.8    2919   310.3 2917.51   372.2  2918.7   384.6 2917.71
     430 2921.16   463.1 2919.31   504.4 2920.99   538.3 2920.71   550.9 2919.84
   617.7 2920.16   781.9 2921.37   800.1 2921.81   824.6 2923.89   863.2 2923.71
#Mann= 4 ,-1,0
       0      .1       0   128.6    .045       0   190.5      .1       0
  806.91     .08       0
#XS Ineff= 2 , 0
                          503.38          2940.1
Permanent Ineff=
       F       F
Bank Sta=128.6,190.5
XS Rating Curve= 0 ,0
Exp/Cntr(USF)=0,0
Exp/Cntr=0.3,0.1

Type RM Length L Ch R = 1 ,2821    ,317.9,300.6,284
XS GIS Cut Line= 3
2310706.82388161590337.8695373072310771.70838841590940.875561177
2311065.10856435591171.475963808
#Sta/Elev= 30
       0 2942.78    51.6 2940.04    55.6 2938.02    79.8 2918.66    91.8 2916.06
     124 2914.34   140.1    2916   152.2 2917.36   184.4 2917.58   196.4 2916.75
   240.7 2917.25   256.8 2916.03   280.9 2917.96   313.1 2916.34   333.2 2917.06
   377.5  2916.3   401.6 2916.56     411 2917.85   437.8 2917.54   461.9 2919.37
   490.1 2918.09   530.4 2919.26   581.8 2918.04   639.3 2920.34     664 2919.02
   783.7 2920.81   876.7 2921.01   898.3 2922.73   950.1 2923.34   979.7 2922.62
#Mann= 3 ,-1,0
       0      .1       0    91.8    .045       0   140.1      .1       0
#XS Ineff= 2 , 0
                          634.78         2932.26
Permanent Ineff=
       F       F
Bank Sta=91.8,140.1
XS Rating Curve= 0 ,0
Exp/Cntr(USF)=0,0
Exp/Cntr=0.3,0.1

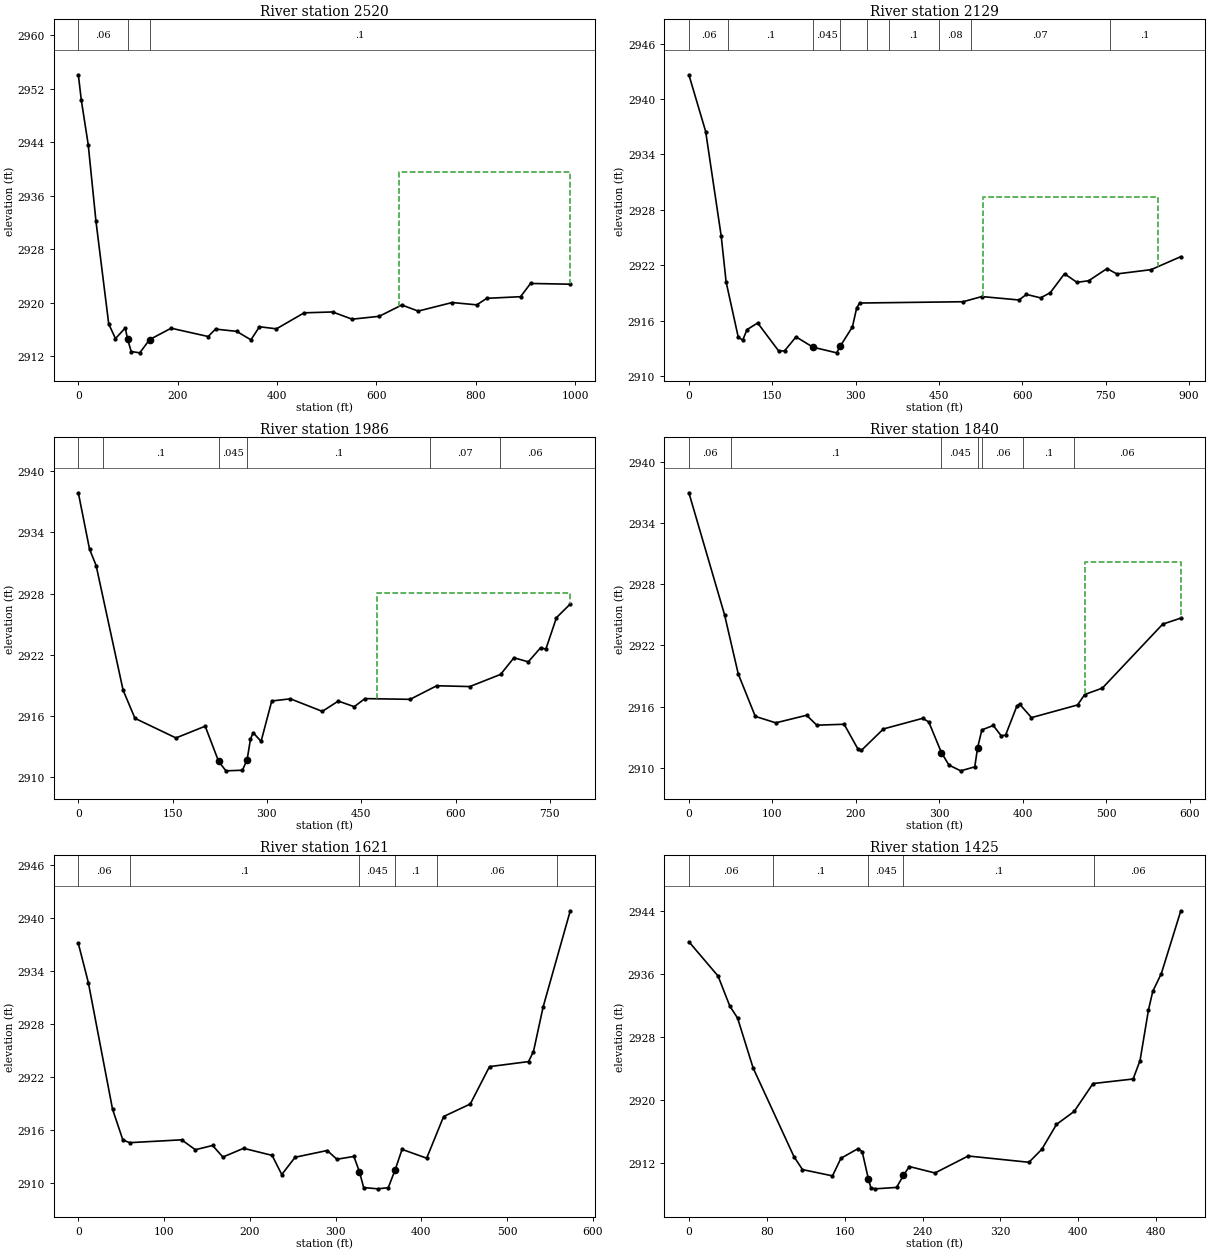
Type RM Length L Ch R = 1 ,2520    ,390.5,391.2,392.1
XS GIS Cut Line= 3
2310376.66332059590472.240538906 2310724.8680767590961.510597965
2311030.76368523591202.721712068
#Sta/Elev= 30
       0 2954.09     6.1 2950.25    19.9 2943.65    35.5  2932.2    61.2 2916.84
    74.8 2914.66    94.4 2916.25    99.3 2914.54   106.4 2912.73   123.7 2912.53
   143.5 2914.51   186.8 2916.21   261.3 2914.97   276.1 2916.08   318.7 2915.74
   347.4 2914.47   364.5 2916.43   398.8 2916.12   454.5 2918.51   511.7 2918.64
     551 2917.56   605.5 2917.99   651.1 2919.68     684 2918.77   752.5 2920.05
     802  2919.7     822 2920.68     890 2920.92   910.2  2922.9   990.1 2922.79
#Mann= 3 ,-1,0
       0     .06       0    99.3    .045       0   143.5      .1       0
#XS Ineff= 2 , 0
                          644.44         2939.61
Permanent Ineff=
       F       F
Bank Sta=99.3,143.5
XS Rating Curve= 0 ,0
Exp/Cntr(USF)=0,0
Exp/Cntr=0.3,0.1

Type RM Length L Ch R = 1 ,2129    ,131,143.1,155.5
XS GIS Cut Line= 4
2310271.27912359590702.8087926342310292.73118856590759.182823797
 2310552.5101726 591072.48723429 2310884.9666053591325.622602449
#Sta/Elev= 30
       0 2942.62    30.2 2936.48    58.2 2925.15      67  2920.2    88.9 2914.21
      97 2913.91   104.5 2915.04   123.8 2915.76   161.6 2912.73   172.1 2912.74
   192.8 2914.26   223.3 2913.14   265.9 2912.53   272.5 2913.26   294.3 2915.34
   301.9 2917.38   307.1 2917.92   493.3 2918.06   527.2 2918.62   593.9 2918.25
   607.4 2918.85   632.8 2918.48   650.2 2919.03   675.9 2921.09   698.2 2920.16
   719.4 2920.33   752.4 2921.65   770.1 2921.07   831.6 2921.53   885.2 2922.94
#Mann= 9 ,-1,0
       0     .06       0   70.32      .1       0   223.3    .045       0
   272.5      .1       0  320.32     .08       0  360.32      .1       0
  450.32     .08       0  507.31     .07       0  757.31      .1       0
#XS Ineff= 1 ,-1
   528.5   843.7 2929.37
Permanent Ineff=
       F
Bank Sta=223.3,272.5
XS Rating Curve= 0 ,0
Exp/Cntr(USF)=0,0
Exp/Cntr=0.3,0.1

Type RM Length L Ch R = 1 ,1986    ,143,145.8,142
XS GIS Cut Line= 2
 2310200.2705378590726.4605427912310456.49967797   591465.864633
#Sta/Elev= 30
       0 2937.87    17.8 2932.36    28.3 2930.75    71.2 2918.55    90.1 2915.79
   155.3 2913.87   201.8 2915.02     223  2911.6   234.7 2910.65   261.1 2910.71
   268.5 2911.75   273.8 2913.74     278 2914.39   290.7 2913.54   307.7 2917.49
   337.3  2917.7   388.1 2916.47   413.5 2917.48   438.9 2916.93   455.8 2917.72
   527.8 2917.65   570.1 2918.98   622.7  2918.9   671.7 2920.09   692.9 2921.72
   715.7 2921.32   735.2 2922.69   743.7 2922.57   760.6 2925.65   782.5 2926.98
#Mann= 6 ,-1,0
       0     .06       0      40      .1       0     223    .045       0
   268.5      .1       0     560     .07       0     670     .06       0
#XS Ineff= 2 , 0
                           475.5         2928.09
Permanent Ineff=
       F       F
Bank Sta=223,268.5
XS Rating Curve= 0 ,0
Exp/Cntr(USF)=0,0
Exp/Cntr=0.3,0.1

Type RM Length L Ch R = 1 ,1840    ,181,219.3,251.2
XS GIS Cut Line= 3
2310162.51183701590719.4267923752310120.50071166590915.525273282
2310250.21586071591281.637189292
#Sta/Elev= 30
       0 2936.94    42.7    2925    59.1 2919.21    79.5 2915.05   104.1 2914.42
   140.9 2915.16   153.2 2914.19   185.9 2914.28   202.3 2911.87   206.5 2911.72
   232.9 2913.82   279.9 2914.86   287.2 2914.51   302.4  2911.5   311.3 2910.29
   325.4 2909.72   342.3 2910.11   345.7 2911.99   350.8 2913.73   364.5 2914.16
   373.9 2913.15   379.2 2913.22   392.7 2916.06   395.9 2916.26   410.2 2914.93
   465.4 2916.17   473.9 2917.19   495.1 2917.82   567.3 2924.08     589 2924.67
#Mann= 7 ,-1,0
       0     .06       0      50      .1       0   302.4    .045       0
   345.7      .1       0  350.55     .06       0  400.55      .1       0
  460.55     .06       0
#XS Ineff= 2 , 0
                           474.2         2930.15
Permanent Ineff=
       F       F
Bank Sta=302.4,345.7
XS Rating Curve= 0 ,0
Exp/Cntr(USF)=0,0
Exp/Cntr=0.3,0.1

Type RM Length L Ch R = 1 ,1621    ,205.5,195.9,185.5
XS GIS Cut Line= 3
 2310093.1036642 590705.512500282310071.83736829590902.596662863
2309805.76486483591167.648972053
#Sta/Elev= 30
       0 2937.11    11.7 2932.67    39.9 2918.34      52 2914.84      60 2914.55
   120.5 2914.87   136.5 2913.75   156.6 2914.23   168.6 2912.92   192.8 2913.91
     226 2913.11   237.3 2910.94   252.9  2912.9   290.3 2913.66   301.6 2912.67
   321.4 2912.99   327.92911.249   332.8 2909.47   349.2 2909.32   361.5 2909.45
   369.5 2911.46   377.6 2913.79   406.3 2912.79   426.1 2917.51   457.2 2918.93
   479.6 2923.16   525.1 2923.73   530.9 2924.87   542.2 2929.94   573.8 2940.81
#Mann= 6 ,-1,0
       0     .06       0      60      .1       0   327.9    .045       0
   369.5      .1       0  418.23     .06       0  558.23      .1       0
Bank Sta=327.9,369.5
XS Rating Curve= 0 ,0
Exp/Cntr=0.3,0.1

Type RM Length L Ch R = 1 ,1425    ,206.8,196.2,182.2
XS GIS Cut Line= 3
2309887.29015838590675.2887529912309881.67936247590761.564301981
2309709.53402448591143.436002454
#Sta/Elev= 30
       0 2940.14      30 2935.77      42 2931.96      50 2930.43      66 2924.07
     108 2912.77   116.7 2911.14   147.5 2910.34   156.2 2912.58   173.8 2913.81
     178 2913.43   184.42909.939     187  2908.8   191.3 2908.69   213.3 2908.87
   220.4  2910.4   226.4 2911.53   252.8 2910.71   286.9 2912.87   349.3 2912.07
   362.5 2913.72   377.6 2916.89   395.8 2918.55   415.1 2922.09   456.3 2922.67
   463.4 2925.01   472.1 2931.48   476.5 2933.83   485.3 2936.09   505.3 2944.08
#Mann= 5 ,-1,0
       0     .06       0   86.46      .1       0   184.4    .045       0
   220.4      .1       0  416.46     .06       0
Bank Sta=184.4,220.4
XS Rating Curve= 0 ,0
Exp/Cntr(USF)=0,0
Exp/Cntr=0.3,0.1

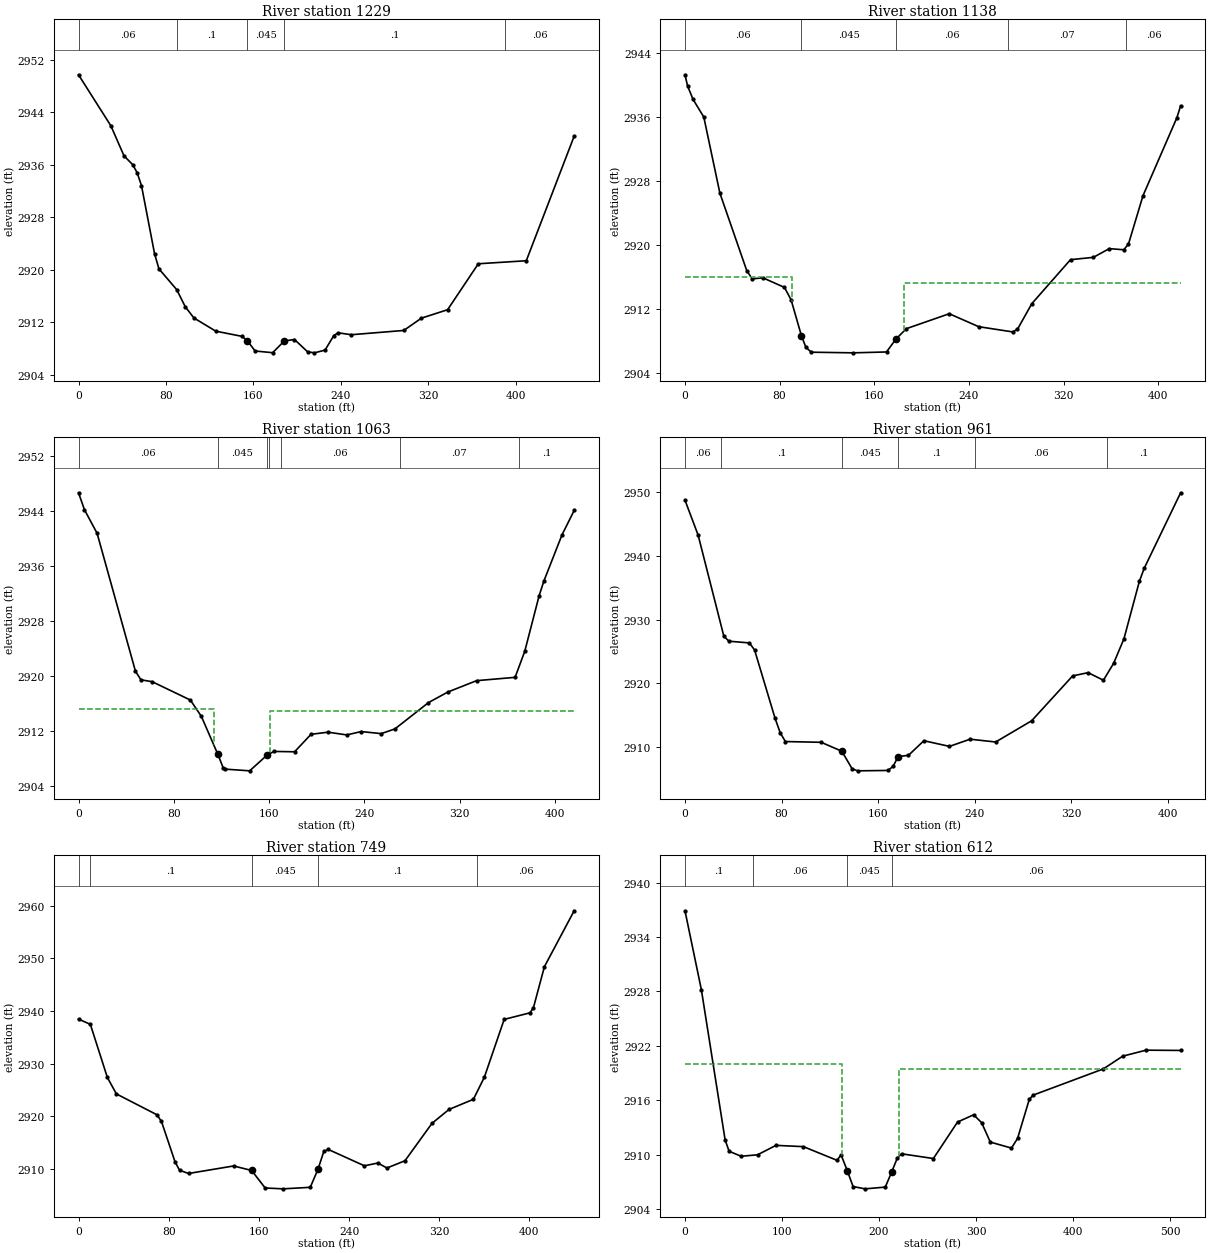
Type RM Length L Ch R = 1 ,1229    ,117.6,90.6,68.3
XS GIS Cut Line= 2
2309646.45932457590675.5690010482309653.73307125591128.965877163
#Sta/Elev= 30
       0 2949.73    29.6 2941.96    41.6 2937.39    49.6 2936.03    53.6 2934.83
    57.6 2932.86    69.6 2922.45    73.6 2920.16    89.9 2916.99    97.6 2914.41
   105.6 2912.68   125.6 2910.67   149.6 2909.88   154.4 2909.22   161.6 2907.65
   177.6 2907.39   188.3 2909.18   197.6  2909.4   209.6 2907.53   215.9 2907.37
   225.6 2907.79   233.6 2910.01   237.6 2910.42   249.6 2910.13   297.6 2910.78
   313.7 2912.65   337.7 2913.94   365.8 2920.94   409.7  2921.4   453.5 2940.38
#Mann= 5 ,-1,0
       0     .06       0      90      .1       0   154.4    .045       0
   188.3      .1       0     390     .06       0
Bank Sta=154.4,188.3
XS Rating Curve= 0 ,0
Exp/Cntr(USF)=0,0
Exp/Cntr=0.5,0.3

Type RM Length L Ch R = 1 ,1138    ,70.7,75.2,85.1
XS GIS Cut Line= 3
2309492.63305229590719.2114811022309593.92670969590906.847205531
 2309552.0353168591108.356928249
#Sta/Elev= 30
       0 2941.31     2.2 2939.91     6.8 2938.24    15.9 2936.03    29.5 2926.51
    52.2 2916.83    56.8 2915.79    65.9 2915.92    84.1 2914.72    89.7 2913.17
    98.5 2908.65   102.2 2907.23   106.8 2906.62   142.2 2906.54   170.4 2906.65
   178.2 2908.24   187.1 2909.56   223.4 2911.43   248.3 2909.81   276.9 2909.16
     281 2909.47   293.2 2912.69   325.9 2918.19   345.2 2918.48   358.7 2919.57
   370.9 2919.43   374.9 2920.14   387.2  2926.2   415.8 2935.93     419 2937.43
#Mann= 5 ,-1,0
       0     .06       0    98.5    .045       0   178.2     .06       0
  273.23     .07       0  373.23     .06       0
#XS Ineff= 2 , 0
           90.34    2916  185.02          2915.3
Permanent Ineff=
       F       F
Bank Sta=98.5,178.2
XS Rating Curve= 0 ,0
Exp/Cntr(USF)=0,0
Exp/Cntr=0.5,0.3

Type RM Length L Ch R = 1 ,1063    ,96.1,102.1,108.2
XS GIS Cut Line= 3
2309413.69943095590723.656548515 2309517.5523696590905.634914418
2309489.80437302591110.377413437
#Sta/Elev= 30
       0 2946.69       5 2944.22    15.6  2940.8    47.8 2920.75    52.4  2919.5
    61.8 2919.23    93.9 2916.56   103.1  2914.2   116.9  2908.7   121.5 2906.69
   123.1 2906.52   143.7 2906.27   158.3 2908.56   164.2 2909.09   181.4 2909.04
   195.2 2911.58   209.5 2911.89   225.2 2911.49   237.3 2911.98   254.1 2911.68
   265.6 2912.36   293.8 2916.19   310.1 2917.73   334.2 2919.38   366.5 2919.86
   374.6 2923.63   386.7 2931.74   390.7 2933.87   405.9 2940.58   416.1 2944.12
#Mann= 7 ,-1,0
       0     .06       0   116.9    .045       0   158.3     .06       0
     160      .1       0     170     .06       0  269.53     .07       0
  369.53      .1       0
#XS Ineff= 2 , 0
          113.53 2915.29  160.87         2914.92
Permanent Ineff=
       F       F
Bank Sta=116.9,158.3
XS Rating Curve= 0 ,0
Exp/Cntr(USF)=0,0
Exp/Cntr=0.5,0.3

Type RM Length L Ch R = 1 ,961     ,196.7,212.1,225.3
XS GIS Cut Line= 2
2309335.22844789590734.9338268062309474.58738454 591121.37646123
#Sta/Elev= 30
       0 2948.79    10.9  2943.3    32.2 2927.43    36.4 2926.64    53.4 2926.37
    57.7 2925.25    74.7 2914.51    78.9 2912.27    83.2 2910.88   112.9 2910.76
     130 2909.36   138.5 2906.61   143.1 2906.28   168.2 2906.34   172.5 2906.98
   176.7 2908.53   185.2 2908.71     198 2911.01   219.2 2910.12   236.3 2911.25
   257.5 2910.81   287.3 2914.14   321.3 2921.19   334.1  2921.7   346.8 2920.51
   355.3 2923.18   363.8 2927.01   376.6 2936.04   380.6 2938.09   410.8 2949.95
#Mann= 6 ,-1,0
       0     .06       0      30      .1       0     130    .045       0
   176.7      .1       0     240     .06       0     350      .1       0
Bank Sta=130,176.7
XS Rating Curve= 0 ,0
Exp/Cntr=0.3,0.1

Type RM Length L Ch R = 1 ,749     ,149.8,136.7,140.6
XS GIS Cut Line= 3
2309193.28041819590759.5981499082309187.21896263591083.279876974
2309252.68268271 591179.05087487
#Sta/Elev= 30
       0 2938.47    10.5 2937.48    25.6 2927.37    33.6 2924.25    69.6 2920.28
    73.6 2919.01    85.6 2911.35    89.6 2909.74    97.6 2909.12   137.6 2910.55
   153.6 2909.69   165.6 2906.36   181.6  2906.2   205.6 2906.49   212.5 2909.96
   217.6  2913.3   221.6 2913.69   253.6 2910.58   265.6 2911.11   273.6 2910.16
   289.6 2911.54   313.6 2918.66   328.7  2921.3   350.3 2923.22     360 2927.41
   377.6 2938.42   400.6 2939.67   403.6 2940.67   413.3 2948.44   439.7 2959.07
#Mann= 5 ,-1,0
       0     .06       0      10      .1       0   153.6    .045       0
   212.5      .1       0  353.74     .06       0
Bank Sta=153.6,212.5
XS Rating Curve= 0 ,0
Exp/Cntr(USF)=0,0
Exp/Cntr=0.5,0.3

Type RM Length L Ch R = 1 ,612     ,62,65.9,64
XS GIS Cut Line= 5
2309018.03296194590696.5509301112309008.52725263 590745.83864578
2309050.75135208590824.3951098772309101.81305374591014.894535312
2309087.08371673591188.700712126
#Sta/Elev= 30
       0 2936.89    16.9 2928.19    41.4 2911.63    45.5 2910.39    57.9 2909.84
    74.8    2910    93.8 2911.04   122.1  2910.9   156.8 2909.39   160.9    2910
   167.3 2908.26   173.3  2906.5   185.7 2906.25   206.5 2906.44     213 2908.08
   218.9 2909.64   223.3 2910.11   256.1 2909.59     281 2913.61   297.6 2914.41
   305.8 2913.54   314.8  2911.4   336.6 2910.74   342.9 2911.81     355 2916.12
     359 2916.58   431.2 2919.46   451.3 2920.87   475.4 2921.53     511  2921.5
#Mann= 4 ,-1,0
       0      .1       0    70.2     .06       0   167.3    .045       0
     213     .06       0
#XS Ineff= 2 , 0
          161.74    2920  220.29          2919.5
Permanent Ineff=
       F       F
Bank Sta=167.3,213
XS Rating Curve= 0 ,0
Exp/Cntr(USF)=0,0
Exp/Cntr=0.5,0.3

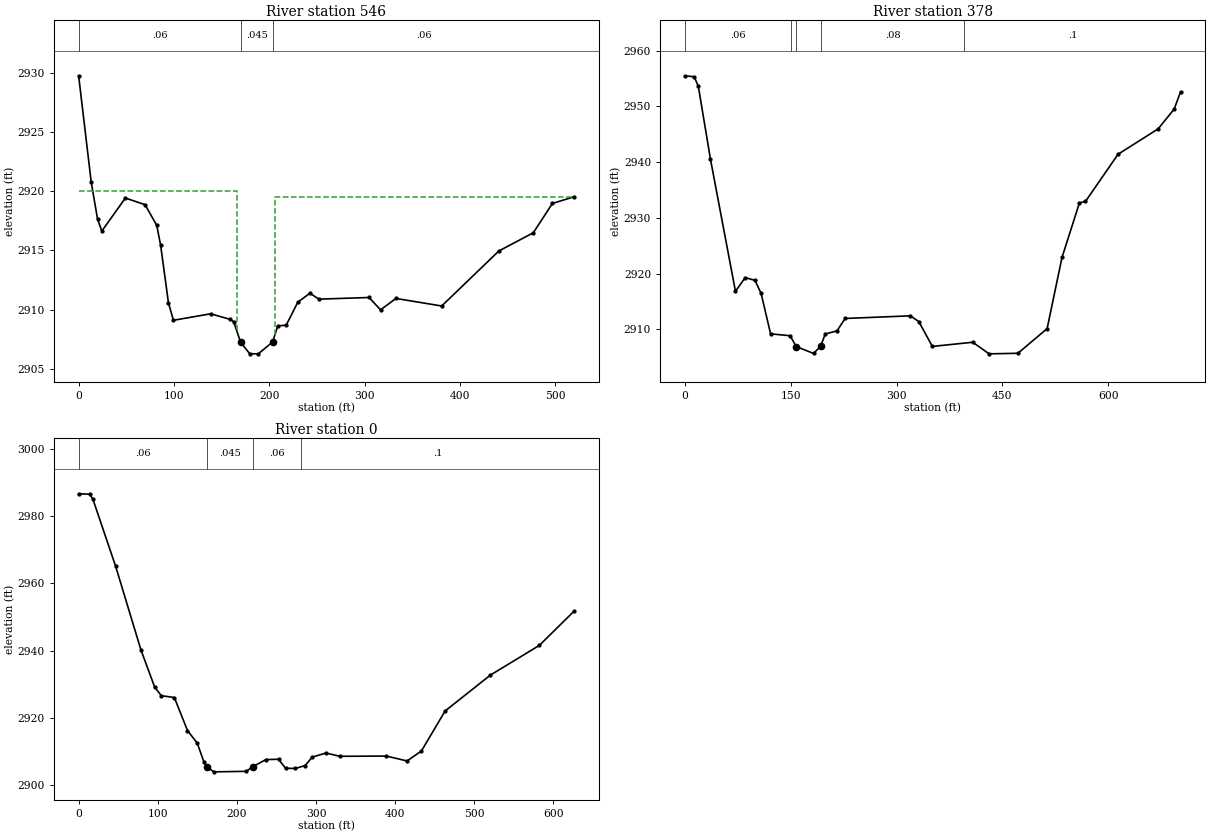
Type RM Length L Ch R = 1 ,546     ,133.6,168,191.7
XS GIS Cut Line= 6
2308988.48673355590689.5640923322308965.27973702590786.236913587
2308990.83483367 590825.987939172309033.26502261590958.127670444
2309039.32647818 591053.898668342309034.47731373591192.099855177
#Sta/Elev= 30
       0 2929.79    13.2 2920.78    19.8 2917.68    24.3 2916.64      49 2919.44
    69.6 2918.88    81.9 2917.13      86 2915.44    94.2 2910.56    99.4 2909.09
   138.4 2909.64   158.4 2909.18   162.6 2908.97   169.92907.221   179.4 2906.26
   188.4 2906.25   203.4 2907.25   208.8 2908.62   217.6 2908.67   229.8 2910.62
   242.5 2911.38     252 2910.88   304.6 2911.02   316.6 2909.97   332.7 2910.94
   380.7  2910.3   440.7 2914.96   476.8  2916.5   496.8 2918.98   519.7 2919.55
#Mann= 3 ,-1,0
       0     .06       0   169.9    .045       0   203.4     .06       0
#XS Ineff= 2 , 0
          166.38    2920   205.8          2919.5
Permanent Ineff=
       F       F
Bank Sta=169.9,203.4
XS Rating Curve= 0 ,0
Exp/Cntr(USF)=0,0
Exp/Cntr=0.5,0.3

Type RM Length L Ch R = 1 ,378     ,395.2,378.3,358.9
XS GIS Cut Line= 4
2309007.79745759590640.1932951462308765.03352561 590872.62684704
2308622.12993444590903.617987293  2308444.791743591034.469468359
#Sta/Elev= 30
       0 2955.49      13 2955.31    18.8 2953.63    36.1 2940.48    71.5 2916.81
    85.3 2919.27    99.2 2918.78   107.9 2916.42   121.3 2909.18     149 2908.84
   157.6  2906.9   182.2 2905.66   192.3 2906.96   198.8 2909.15   215.5 2909.72
     227 2911.94   319.5 2912.41   331.4 2911.39   350.7 2906.92   407.9 2907.67
   431.1 2905.59     472 2905.69   513.4 2910.12   534.5 2922.89   559.2 2932.68
   567.8 2932.95     614 2941.41   670.8 2945.96   693.5 2949.51   702.7 2952.62
#Mann= 5 ,-1,0
       0     .06       0     150      .1       0   157.6    .045       0
   192.3     .08       0  396.09      .1       0
Bank Sta=157.6,192.3
XS Rating Curve= 0 ,0
Exp/Cntr(USF)=0,0
Exp/Cntr=0.3,0.1

Type RM Length L Ch R = 1 ,0       ,116.5,,102.4
XS GIS Cut Line= 4
2308610.07782435590395.7076331532308585.97360415590493.846243953
2308537.76516376590678.0713554542308394.86157259590981.095837925
#Sta/Elev= 30
       0 2986.65    13.9 2986.53      18 2985.06    46.8 2965.08    78.8 2940.19
    96.2 2929.12   104.5 2926.62     121 2926.06   137.6 2916.26     150 2912.48
   158.3 2906.95   162.4 2905.47   170.7 2903.97     212 2904.12     220 2905.49
   236.8 2907.63   252.7  2907.7   261.6 2905.04     274 2904.97   286.4 2905.85
   295.2 2908.34   312.6 2909.56   330.3 2908.59     389 2908.66   415.2 2907.21
   433.3 2910.16   463.3 2922.07   520.3  2932.7   582.4 2941.57   626.5 2951.79
#Mann= 4 ,-1,0
       0     .06       0   162.4    .045       0     220     .06       0
  281.06      .1       0
Bank Sta=162.4,220
XS Rating Curve= 0 ,0
Exp/Cntr(USF)=0,0
Exp/Cntr=0.3,0.1
LCMann Table=0

Chan Stop Cuts=-1
Use User Specified Reach Order=0
Composite Channel Slope=5